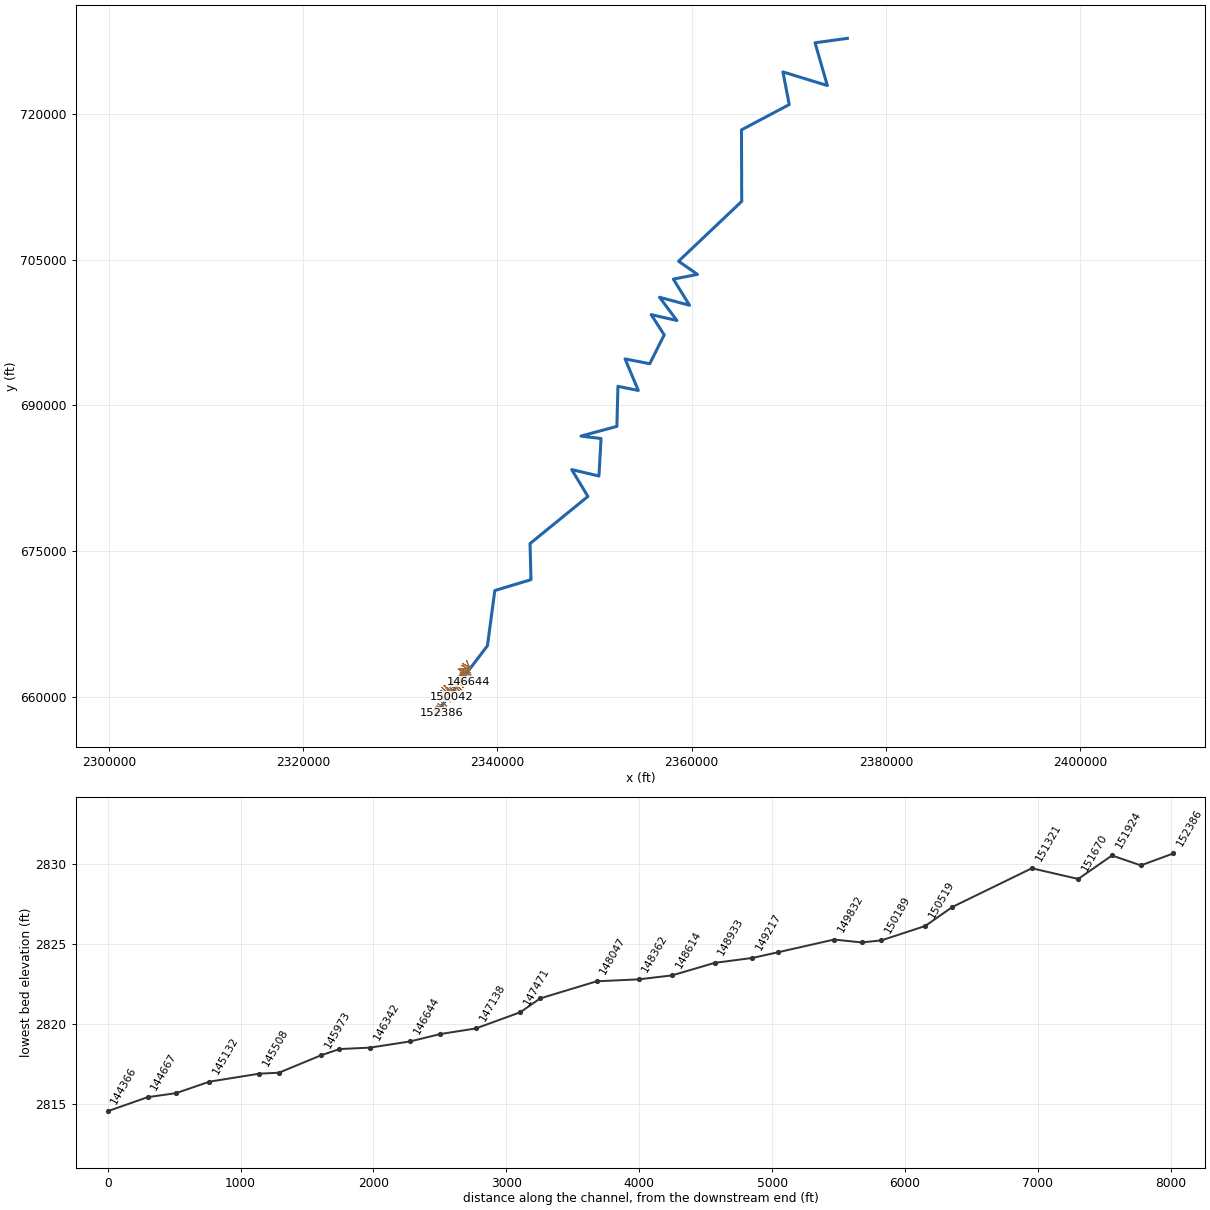
--- GLADYFK.prj (project) ---

Proj Title=GLADYFK
Current Plan=p01
Default Exp/Contr=0,0
English Units
Geom File=g01
Flow File=f01
Plan File=p01
BEGIN DESCRIPTION:
----------MODEL BY WOOD PLC 2022----------
AFH study
Randolph County, WV
HEC-RAS Version: RAS 6.2
Vertical Datum: NAVD88
Projection: NAD 1983 StatePlane West Virginia S FIPS 4702 (US Feet)
Terrain: 1-meter LIDAR (FEMA Region III 3DEP collected 2016-2018)
Land Use: 2019 NLCD
Hydrologic Method:
WV SIR2010-5033 regression equations
Additional Model Notes:
None
END DESCRIPTION:
DSS Export Rating Curves= 0
DSS Export Rating Curve Sorted= 0
DSS Export Volume Flow Curves= 0
DXF OffsetX= 0
DXF OffsetY= 0
DXF ScaleX= 0
DXF ScaleY= 0

--- GLADYFK.p01 (plan) ---

Plan Title=Floodplain
Program Version=6.20
Short Identifier=Floodplain
Geom File=g01
Flow File=f01
Subcritical Flow
K Sum by GR= 0
Std Step Tol= 0.01
Critical Tol= 0.01
Num of Std Step Trials= 20
Max Error Tol= 0.3
Flow Tol Ratio= 0.001
Split Flow NTrial= 30
Split Flow Tol= 0.02
Split Flow Ratio= 0.02
Log Output Level= 0
Friction Slope Method= 1
Unsteady Friction Slope Method= 2
Unsteady Bridges Friction Slope Method= 1
Parabolic Critical Depth
Global Vel Dist= 0 , 0 , 0
Global Log Level= 0
CheckData=True
Encroach Param=-1 ,0,0, 0
Mapping Interval=1HOUR
Computation Time Step Use Courant=        0
Computation Time Step Use Time Series=    0
Computation Time Step Count To Double=0
Computation Time Step Max Doubling=0
Computation Time Step Max Halving=0
Computation Time Step Residence Courant=0
Run HTab= 0
Run UNet= 0
Run Sediment= 0
Run PostProcess= 0
Run WQNet= 0
Run RASMapper=-1
UNET Theta= 0
UNET Theta Warmup= 0
UNET ZTol= 0
UNET ZSATol= 0
UNET MxIter= 0
UNET Max Iter WO Improvement= 0
UNET MaxInSteps= 0
UNET DtIC= 0
UNET DtMin= 0
UNET MaxCRTS= 0
UNET WFStab= 0
UNET SFStab= 0
UNET WFX= 1
UNET SFX= 1
UNET Gravity=32.174
UNET 1D Methodology=Finite Difference
UNET DSS MLevel= 1
UNET Pardiso=0
UNET DZMax Abort= 0
UNET Use Existing IB Tables= 0
UNET Froude Reduction=False
UNET Froude Limit= 0
UNET Froude Power= 0
UNET D1 Cores= 0
UNET WindReference=Eulerian
UNET WindDragFormulation=Hsu (1988)
UNET D2 Coriolis=0
UNET D2 Cores= 0
UNET D2 Theta= 1
UNET D2 Theta Warmup= 1
UNET D2 Z Tol= 0.01
UNET D2 Volume Tol= 0.01
UNET D2 Max Iterations= 20
UNET D2 Equation= 0
UNET D2 RampUpFraction=0.1
UNET D2 TimeSlices= 1
UNET D2 Turbulence Formulation=Non-Conservative (original)
UNET D2 Eddy Viscosity=0.3
UNET D2 Transverse Eddy Viscosity=0.1
UNET D2 Smagorinsky Mixing=0
UNET D2 BCVolumeCheck=0
UNET D2 Cores=0
UNET D2 SolverType=PARDISO (Direct)
UNET D2 Minimum Iterations= 2147483647
UNET D2 Maximum Iterations= 2147483647
UNET D2 Restart Number= 10
UNET D2 Relaxation Coeff=1.3
UNET D2 SOR Precondition Iterations= 10
UNET D2 ILUT Maximum Fill= 8
UNET D2 ILUT Tolerance=1E-08
UNET D1D2 MaxIter= 0
UNET D1D2 ZTol=0.01
UNET D1D2 QTol=0.1
UNET D1D2 MinQTol=1
Write IC File= 0
Write IC File at Fixed DateTime=0
Write IC File at Sim End=0
Echo Input=False
Echo Parameters=False
Echo Output=False
Write Detailed= 0
HDF Write Warmup=0
HDF Write Time Slices=0
HDF Flush=0
HDF Compression= 1
HDF Chunk Size= 1
HDF Spatial Parts= 1
HDF Use Max Rows=0
HDF Fixed Rows= 1
Calibration Method= 0
Calibration Iterations= 20
Calibration Max Change=0.05
Calibration Tolerance=0.2
Calibration Maximum=1.5
Calibration Minimum=0.5
Calibration Optimization Method= 1
WQ AD Non Conservative
WQ ULTIMATE=-1
WQ Max Comp Step=1HOUR
WQ Output Interval=15MIN
WQ Output Selected Increments= 0
WQ Output face flow=0
WQ Output face velocity=0
WQ Output face area=0
WQ Output face dispersion=0
WQ Output cell volume=0
WQ Output cell surface area=0
WQ Output cell continuity=0
WQ Output cumulative cell continuity=0
WQ Output face conc=0
WQ Output face dconc_dx=0
WQ Output face courant=0
WQ Output face peclet=0
WQ Output face adv mass=0
WQ Output face disp mass=0
WQ Output cell mass=0
WQ Output cell source sink temp=0
WQ Output nsm pathways=0
WQ Output nsm derived pathways=0
WQ Create Restart=0
WQ Fixed Restart=0
WQ System Summary=0
WQ Write To DSS=0
Sorting and Armoring Iterations= 10
XS Update Threshold= 0.02
Bed Roughness Predictor= 0
Hydraulics Update Threshold= 0.02
Energy Slope Method= 1
Volume Change Method= 1
Sediment Retention Method= 0
Sediment TS Multiplier= 1
Warm Up Method= 0
XS Weighting Method= 0
Number of US Weighted Cross Sections= 1
Number of DS Weighted Cross Sections= 1
Upstream XS Weight=0
Main XS Weight=1
Downstream XS Weight=0
Number of DS XS's Weighted with US Boundary= 1
Upstream Boundary Weight= 1
Weight of XSs Associated with US Boundary= 0
Number of US XS's Weighted with DS Boundary= 1
Downstream Boundary Weight= 0.5
Weight of XSs Associated with DS Boundary= 0.5
Percentile Method= 0
Sediment Output Level= 3
Mass or Volume Output= 0
Output Increment Type= 1
Profile and TS Output Increment= 1
Transport Output Increment 1
XS Output Flag= 0
XS Output Increment= 10
Read HDF5 Sediment Hotstart= 0
Sediment Hotstart Type= 0
Write Gradation File= 0
Read Gradation Hotstart= 0
Write HDF5 File= 1
Write Binary Output= 1
Write DSS Sediment File= 0
DSS Sediment Output Type= 1
SV Curve= 0
Specific Gage Flag= 0
Subcell Erosion Methods= 0
Subcell Deposition Methods= 0
Advection Scheme= 1
Matrix Solver= 0
Implicit Weighting Factor= 1
Maximum Outer Loop Convergence Iterations= 5
Convergence Maximum Absolute= 0.001
Convergence RMSE= 0.0001
Grain Fractions Max Abs Error= 0.001
Max Subgrid Regions= 1
Max Subgrid Length Scale= 3.402823E+38
Initial Layer Thickness= 3.402823E+38
Min Layer Thickness= 3.402823E+38
Max Layer Thickness= 3.402823E+38
Number of Layers= 5

--- GLADYFK.f01 (steady flow) ---

Flow Title=Flow
Program Version=6.20
Number of Profiles= 1
Profile Names=P100yr
River Rch & RM=GLADYFK,Main            ,152386
    3560
River Rch & RM=GLADYFK,Main            ,135552
    4400
River Rch & RM=GLADYFK,Main            ,119853
    4920
River Rch & RM=GLADYFK,Main            ,112997
    5470
River Rch & RM=GLADYFK,Main            ,85373
    6200
River Rch & RM=GLADYFK,Main            ,60824
    6990
River Rch & RM=GLADYFK,Main            ,30359
    7930
Boundary for River Rch & Prof#=GLADYFK,Main            , 1
Up Type= 0
Dn Type= 3
Dn Slope=0.008741
DSS Import GetInterval= 0
DSS Import GetPeak= 0
DSS Import FillOption= 0

--- GLADYFK.g01 (geometry) ---

Geom Title=Geometry
Program Version=6.20

River Reach=GLADYFK         ,Main
Reach XY= 30
     2333658.361      658269.856     2338971.694      665229.447
     2339731.895      670924.119     2343453.105      672042.838
     2343357.884      675761.7812349314.40045894680617.078870025
     2347647.136      683384.517     2350447.581       682720.98
     2350666.461      686583.812     2348595.588      686833.968
2352294.73504422 687834.69695578     2352406.352      691962.006
     2354500.536      691533.403     2353137.607      694783.735
     2355678.084      694288.723     2357167.137      697261.529
     2355824.574      699347.257     2358470.125      698745.359
     2356679.981      701136.065     2359773.122      700312.062
     2358107.859      703003.249     2360593.623      703490.923
     2358645.012       704849.43     2365142.827       711013.27
     2365119.957      718378.921     2370032.495      720985.804
     2369388.678      724349.855     2373955.764      722946.697
     2372690.425      727349.224     2376022.465      727809.501

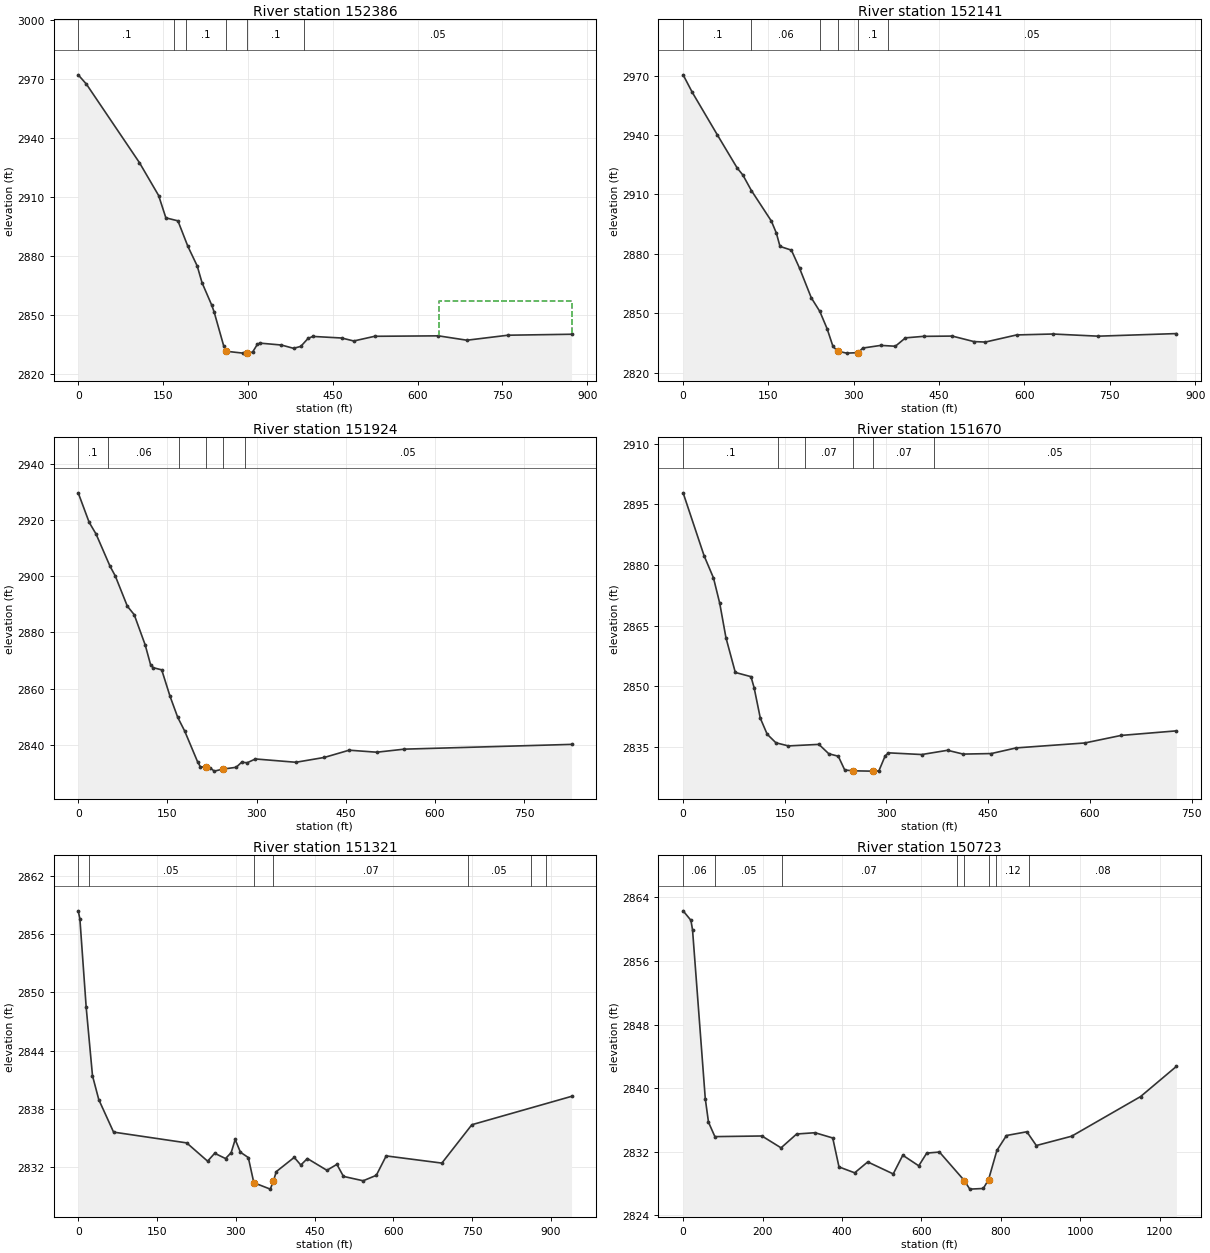
Type RM Length L Ch R = 1 ,152386  ,253.6,245.3,242.7
XS GIS Cut Line= 2
2333438.58642161658631.7211917232334257.86126192658332.419547275
#Sta/Elev= 30
       0 2972.05    14.5 2967.33   108.2 2927.46   142.2 2910.73     155 2899.38
   176.3 2897.87   193.9 2884.91   210.4 2874.95   218.9 2866.47   235.9 2855.15
   240.2 2851.69   257.2 2834.39   261.5 2831.61   291.3 2830.66   298.8 2830.75
   308.3 2831.17   316.8 2835.14   321.1 2835.75   359.4 2834.77   380.7  2833.1
   393.5 2834.08   406.3  2838.1   414.8 2839.15   465.9 2838.34   487.2 2836.83
   524.1 2839.21   636.9 2839.44   687.3 2837.22   759.7 2839.76   872.2 2840.25
#Mann= 6 ,-1,0
       0      .1       0     170     .06       0     190      .1       0
   261.5    .045       0   298.8      .1       0     400     .05       0
#XS Ineff= 2 , 0
                          638.21         2857.39
Permanent Ineff=
       F       F
Bank Sta=261.5,298.8
XS Rating Curve= 0 ,0
Exp/Cntr(USF)=0,0
Exp/Cntr=0.3,0.1

Type RM Length L Ch R = 1 ,152141  ,214.4,217.2,218.6
XS GIS Cut Line= 3
2333620.45150887658908.0095525752334141.12499224658514.412771243
2334339.36044342658432.696723652
#Sta/Elev= 30
       0 2970.41    16.1 2961.57    59.8 2940.27    94.9 2923.43     105 2919.83
     120    2912   155.1 2896.59   163.9  2890.5   170.3 2883.78   190.3 2881.91
   204.6 2872.83   225.3 2857.83   240.3 2850.96   253.1 2842.23   263.4  2833.3
   271.7  2830.9   287.4 2829.91   307.4 2830.14   315.9 2832.47   347.4 2833.81
   373.1 2833.39   390.8 2837.62   422.6 2838.38     473 2838.52   511.1 2835.74
   531.2  2835.5   586.3  2839.1     650 2839.56   729.7 2838.47   867.1 2839.78
#Mann= 6 ,-1,0
       0      .1       0     120     .06       0     240      .1       0
   271.7    .045       0   307.4      .1       0     360     .05       0
Bank Sta=271.7,307.4
XS Rating Curve= 0 ,0
Exp/Cntr=0.3,0.1

Type RM Length L Ch R = 1 ,151924  ,253.1,254.1,253.7
XS GIS Cut Line= 2
2333766.95481918659033.1893087832334482.87284601658613.184066377
#Sta/Elev= 30
       0 2929.82    18.4 2919.31    30.1 2915.09    53.5 2903.65    62.3  2900.2
    82.7 2889.36    94.2 2886.36   112.7 2875.56     122 2868.33   126.5 2867.42
   140.5 2866.66   154.5 2857.23   167.5 2849.69   179.2 2844.81   200.8 2833.89
   205.5 2832.09   214.7 2831.89   221.4 2831.79   228.9 2830.53   243.5 2831.25
   265.8  2831.9     275 2833.71   284.3 2833.52   298.2 2834.87   366.3 2833.69
   414.2 2835.42   455.9    2838   502.3 2837.28   548.6 2838.37     830 2840.07
#Mann= 6 ,-1,0
       0      .1       0      50     .06       0     170      .1       0
   214.7    .045       0   243.5      .1       0     280     .05       0
Bank Sta=214.7,243.5
XS Rating Curve= 0 ,0
Exp/Cntr(USF)=0,0
Exp/Cntr=0.3,0.1

Type RM Length L Ch R = 1 ,151670  ,352.2,348.8,346.1
XS GIS Cut Line= 2
2333885.24087088659251.409457983     2334517.581      658891.181
#Sta/Elev= 30
       0 2897.82      31 2882.25    44.8 2876.79      54 2870.54    63.2 2862.01
      77 2853.44   100.1  2852.4   104.7 2849.69   113.9 2842.13     124 2838.18
   136.9 2836.06   155.3 2835.29   200.3 2835.67   214.9 2833.35   228.9 2832.74
   238.4 2829.34   250.1 2829.14   276.5 2829.06     280 2829.09   288.8 2829.13
     298 2832.81   302.9 2833.58     352 2833.16   390.1 2834.21   413.1 2833.27
   454.5  2833.4   491.4  2834.8   592.6 2836.02   646.1 2837.88   727.7 2839.01
#Mann= 6 ,-1,0
       0      .1       0     140     .06       0     180     .07       0
   250.1    .045       0     280     .07       0     370     .05       0
Bank Sta=250.1,280
XS Rating Curve= 0 ,0
Exp/Cntr=0.3,0.1

Type RM Length L Ch R = 1 ,151321  ,575.6,597.9,618.1
XS GIS Cut Line= 3
2333992.92977116659529.4338893412334163.98170685659526.952574886
2334753.83260395659035.277918492
#Sta/Elev= 30
       0 2858.38     3.2 2857.55    15.2 2848.44    27.2  2841.4    39.2 2838.94
    67.3  2835.6   206.5 2834.49   246.3 2832.61   259.8 2833.42   280.4 2832.88
   291.1 2833.48   298.8 2834.84   308.8 2833.53   323.8 2832.98   334.3 2830.39
   365.6 2829.73   371.3 2830.52     377 2831.53   411.2    2833   423.7 2832.21
   436.2 2832.88   473.4 2831.67   492.4 2832.28   504.9 2831.04   542.4 2830.59
   567.4 2831.15   586.2 2833.15   692.2 2832.41   749.3 2836.36     939 2839.28
#Mann= 7 ,-1,0
       0     .06       0      20     .05       0   334.3    .045       0
   371.3     .07       0  741.07     .05       0  861.07     .07       0
  891.07     .05       0
Bank Sta=334.3,371.3
XS Rating Curve= 0 ,0
Exp/Cntr(USF)=0,0
Exp/Cntr=0.3,0.1

Type RM Length L Ch R = 1 ,150723  ,199.3,204.4,215
XS GIS Cut Line= 5
2334024.65461939659819.3570497272334152.49694175659805.538172135
2334316.39497527659731.668635899 2334826.5564599659685.500175751
2335180.01160712 659455.90941778
#Sta/Elev= 30
       0 2862.29    19.6  2861.1    23.7 2859.91    55.8 2838.68    63.9 2835.72
      80 2833.91   198.4 2833.99   246.6  2832.5   285.9 2834.24   332.2  2834.4
   376.7 2833.74   392.5  2830.1     432 2829.36   464.8 2830.73     529 2829.22
   553.1 2831.57   593.3 2830.24   613.4 2831.84   645.4 2831.97   708.2 2828.38
   721.8 2827.31   755.8 2827.39     769  2828.5   790.1 2832.18   814.2 2834.05
   865.5 2834.52   889.3 2832.79   978.2 2833.96  1151.7 2838.94  1242.1 2842.74
#Mann= 8 ,-1,0
       0     .06       0      80     .05       0  248.59     .07       0
  688.36     .08       0   708.2    .045       0     769     .08       0
  788.36     .12       0  870.61     .08       0
Bank Sta=708.2,769
XS Rating Curve= 0 ,0
Exp/Cntr(USF)=0,0
Exp/Cntr=0.3,0.1

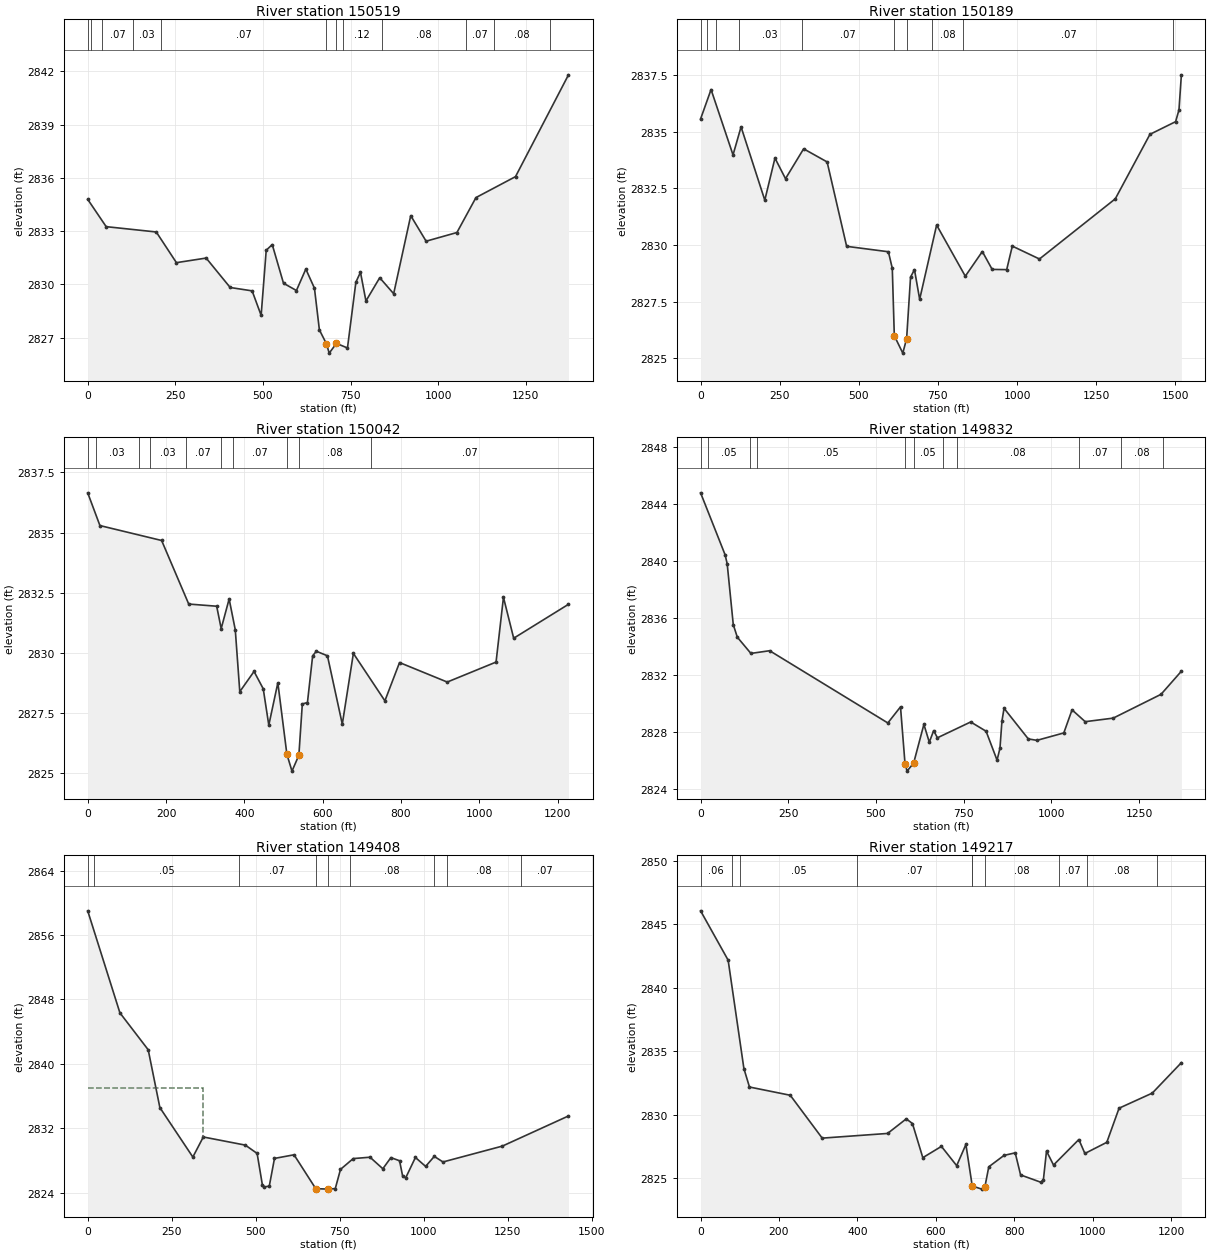
Type RM Length L Ch R = 1 ,150519  ,334,329.6,324.2
XS GIS Cut Line= 4
2334096.61479153 660267.657688872334633.75039555659886.562848696
2334743.35378282659882.1829828722335235.45672453659532.982454324
#Sta/Elev= 30
       0 2834.79    52.7 2833.25   195.6 2832.95   253.1 2831.22   337.9 2831.48
   406.5 2829.82   469.1 2829.63   494.8 2828.25   509.3 2831.92   526.5 2832.24
   558.6 2830.06   595.5 2829.65   622.3 2830.86   646.9 2829.78     661 2827.43
     681 2826.65     689 2826.12   709.7 2826.67   741.1 2826.41   765.1 2830.12
   778.2 2830.68   793.8 2829.06   833.1 2830.37   872.9 2829.47   921.6 2833.87
   965.5 2832.43  1053.4 2832.92  1107.7 2834.89  1220.5 2836.07  1371.7 2841.81
#Mann= 12 ,-1,0
       0      .1       0      10     .03       0      40     .07       0
     130     .03       0     210     .07       0     681    .045       0
   709.7     .07       0   728.6     .12       0  838.29     .08       0
 1078.29     .07       0 1158.29     .08       0 1318.29     .07       0
Bank Sta=681,709.7
XS Rating Curve= 0 ,0
Exp/Cntr(USF)=0,0
Exp/Cntr=0.3,0.1

Type RM Length L Ch R = 1 ,150189  ,147.6,147.5,142.5
XS GIS Cut Line= 3
2333992.00245796660357.6755887772334860.07616587660144.023728978
2335412.25483643659850.931081784
#Sta/Elev= 30
       0 2835.57    33.1 2836.87   102.5 2833.98   127.9 2835.22   202.9 2831.98
     235 2833.84   268.3 2832.93   325.6 2834.25   399.8 2833.67   461.5 2829.94
   593.4  2829.7   605.7 2828.97   612.1 2825.99   638.9 2825.22     651 2825.86
   663.4 2828.58   675.8 2828.91   692.2  2827.6   745.8 2830.88   836.4 2828.62
   890.2 2829.71   921.3 2828.92   967.2 2828.91   984.9 2829.95  1070.7 2829.38
  1310.3 2832.04  1419.8 2834.89  1500.9 2835.45  1511.5 2835.97  1519.1 2837.52
#Mann= 10 ,-1,0
       0      .1       0      20     .06       0      50      .1       0
     120     .03       0     320     .07       0   612.1    .045       0
     651     .07       0     730     .08       0     830     .07       0
 1493.98      .1       0
Bank Sta=612.1,651
XS Rating Curve= 0 ,0
Exp/Cntr=0.3,0.1

Type RM Length L Ch R = 1 ,150042  ,212.5,209.4,203.6
XS GIS Cut Line= 4
2334191.17804494660627.3179674922334604.96100623660361.132992322
2334678.56844412660328.4185754832335232.59319964659978.454988311
#Sta/Elev= 30
       0 2836.65    31.2 2835.29   188.8 2834.67     258 2832.03   329.4 2831.94
   340.9 2831.01   361.2 2832.24   376.9 2830.96   388.4 2828.39   424.8 2829.23
   448.3 2828.51   462.5    2827   485.6 2828.76   508.7 2825.79   521.7 2825.09
   539.3 2825.75   548.1 2827.88   561.2 2827.94   574.5 2829.88   583.9 2830.07
   612.3 2829.88   650.2 2827.04   678.5 2829.98     759 2828.01   796.4  2829.6
   918.2 2828.79  1042.9 2829.62  1061.8 2832.31  1087.9 2830.61  1227.9 2832.02
#Mann= 10 ,-1,0
       0     .06       0      20     .03       0     130     .05       0
     160     .03       0     250     .07       0     340     .03       0
     370     .07       0   508.7    .045       0   539.3     .08       0
  722.56     .07       0
Bank Sta=508.7,539.3
XS Rating Curve= 0 ,0
Exp/Cntr(USF)=0,0
Exp/Cntr=0.3,0.1

Type RM Length L Ch R = 1 ,149832  ,395.6,424.2,409.5
XS GIS Cut Line= 3
2334297.94020818660945.8773515722334994.42528064660274.046617968
2335337.53149627660062.430209524
#Sta/Elev= 30
       0  2844.8    70.1 2840.44    75.9 2839.81    93.2 2835.55   104.7 2834.67
   143.5 2833.53   196.9 2833.72   533.9 2828.65     570 2829.78   582.9 2825.78
   588.7 2825.27   607.5 2825.84   636.7 2828.55   652.1  2827.3   664.5 2828.11
   675.3 2827.61   770.1 2828.72     814 2828.07   845.3 2826.04   853.6 2826.88
   859.2 2828.78   865.2 2829.68   934.4 2827.53     959 2827.43  1035.6 2827.95
  1059.1 2829.57  1096.6 2828.74  1176.5 2828.99  1312.8 2830.66  1370.8 2832.28
#Mann= 11 ,-1,0
       0     .07       0      20     .05       0     140     .06       0
     160     .05       0   582.9    .045       0   607.5     .05       0
     690     .07       0     730     .08       0  1077.7     .07       0
  1197.7     .08       0  1317.7     .07       0
Bank Sta=582.9,607.5
XS Rating Curve= 0 ,0
Exp/Cntr(USF)=0,0
Exp/Cntr=0.3,0.1

Type RM Length L Ch R = 1 ,149408  ,206,190.5,186.5
XS GIS Cut Line= 2
2334510.08049752661143.3720206782335416.90999817660036.085472517
#Sta/Elev= 30
       0    2859    95.9 2846.34   180.1 2841.76   214.8 2834.59     313 2828.45
   344.1 2830.94   469.2 2829.93   504.3  2828.9   519.9 2825.01     526 2824.75
   540.5 2824.84     556 2828.28   614.2 2828.73   678.8 2824.53   716.3 2824.47
     737 2824.54   752.5 2826.92   790.4 2828.26   840.4 2828.43   878.5    2827
   902.5 2828.38   928.3 2827.99   937.6 2826.07   946.7 2825.88   975.5  2828.4
  1005.9 2827.29  1031.7 2828.53  1057.6 2827.84  1234.4 2829.81  1431.2 2833.55
#Mann= 9 ,-1,0
       0     .07       0      20     .05       0     450     .07       0
   678.8    .045       0   716.3     .07       0     780     .08       0
    1030     .07       0    1070     .08       0    1290     .07       0
#XS Ineff= 2 , 0
           343.7 2837.04
Permanent Ineff=
       F       F
Bank Sta=678.8,716.3
XS Rating Curve= 0 ,0
Exp/Cntr(USF)=0,0
Exp/Cntr=0.3,0.1

Type RM Length L Ch R = 1 ,149217  ,263.1,284.5,290
XS GIS Cut Line= 4
2334634.96296562 661099.783095932335136.87027433660666.943581847
2335147.72844851 660595.447184132335533.40952173660291.170504855
#Sta/Elev= 30
       0 2846.06    70.3 2842.17   110.5 2833.62   124.7 2832.17   228.7 2831.52
   310.2 2828.14     477 2828.51   524.6 2829.66   540.4 2829.29   566.8  2826.6
   614.3 2827.49   653.2 2825.97   676.7 2827.64   692.9 2824.37   717.1 2824.12
   725.2 2824.31   735.1 2825.88     774 2826.78   802.5 2826.98   816.2 2825.24
   868.1 2824.66   874.4 2824.87   882.3 2827.12   900.2 2826.02   964.8 2828.03
   980.2 2826.93  1036.1 2827.81  1067.4  2830.5  1152.1 2831.69  1226.3 2834.09
#Mann= 10 ,-1,0
       0     .06       0      80     .08       0     100     .05       0
     400     .07       0  692.77     .08       0   692.9    .045       0
   725.2     .08       0  915.08     .07       0  985.08     .08       0
 1165.08      .1       0
Bank Sta=692.9,725.2
XS Rating Curve= 0 ,0
Exp/Cntr=0.3,0.1

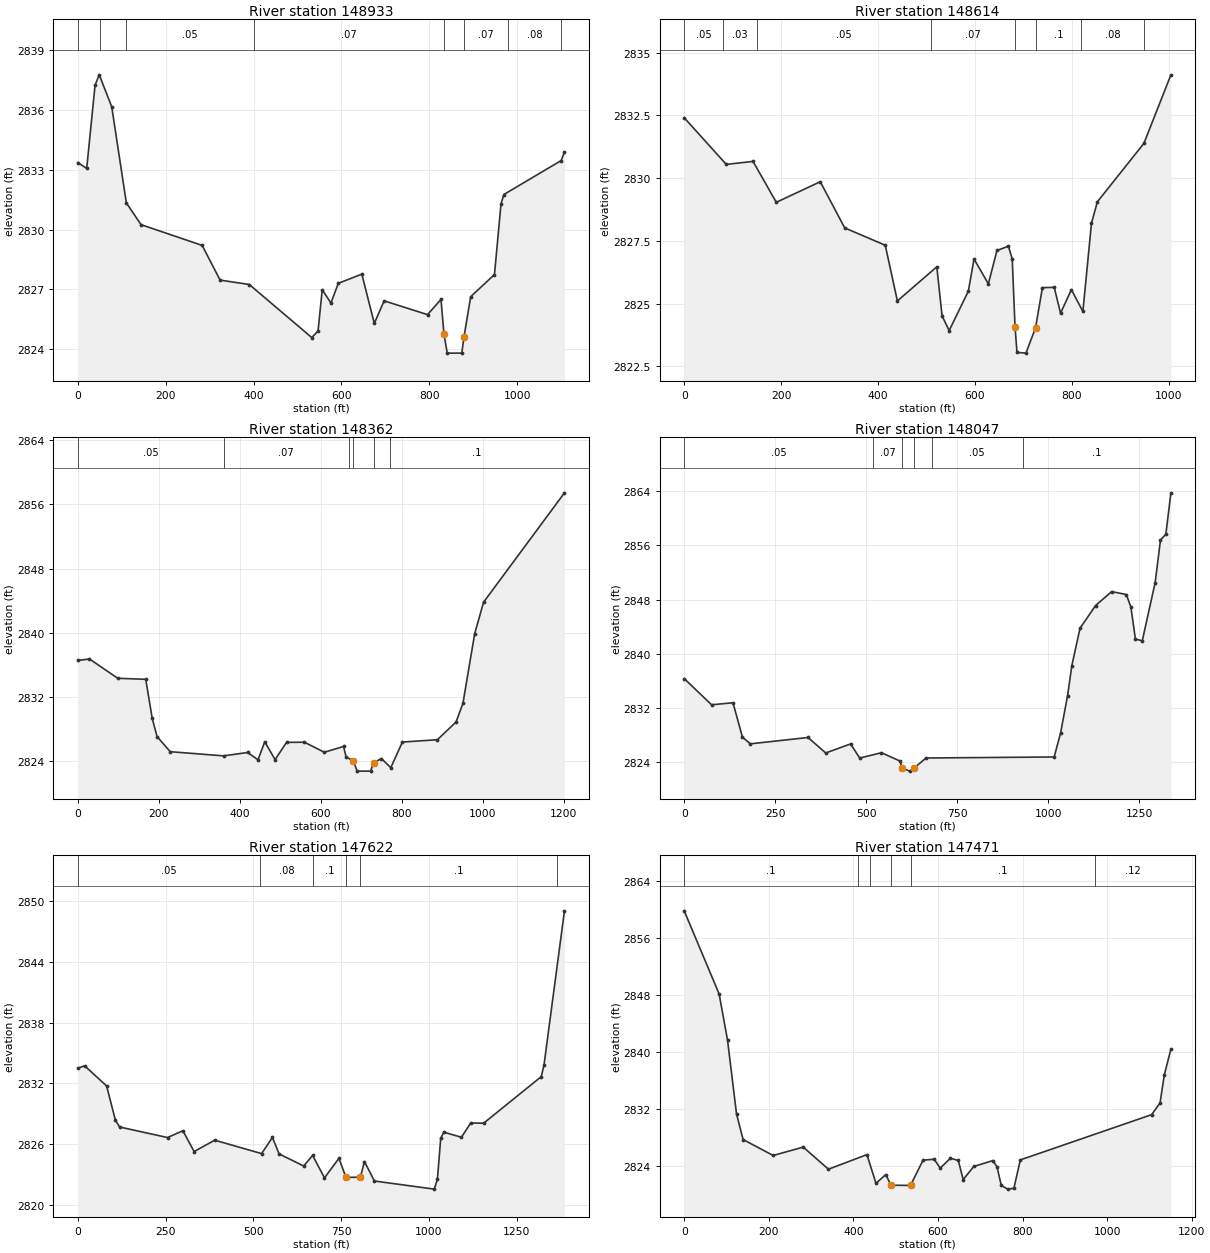
Type RM Length L Ch R = 1 ,148933  ,308.2,318.8,318.4
XS GIS Cut Line= 2
2334934.61177664661270.4211315272335529.74616433660336.172923399
#Sta/Elev= 30
       0 2833.36    20.4 2833.07    39.4 2837.24    48.9 2837.76    77.3 2836.16
   110.6 2831.34     144 2830.25   283.1 2829.21     324 2827.47   390.4 2827.25
   532.6 2824.59   546.9 2824.92   556.4 2826.99   576.2 2826.32     593 2827.31
   646.5 2827.77   674.9  2825.3   697.3 2826.43     796 2825.74   826.7  2826.5
   833.5 2824.75   840.9 2823.81     874 2823.81   878.9 2824.61   894.3 2826.64
   948.4 2827.75   963.3 2831.29   969.7 2831.76    1100 2833.46  1107.7 2833.88
#Mann= 8 ,-1,0
       0     .05       0      50     .08       0     110     .05       0
     400     .07       0   833.5    .045       0   878.9     .07       0
     980     .08       0    1100      .1       0
Bank Sta=833.5,878.9
XS Rating Curve= 0 ,0
Exp/Cntr(USF)=0,0
Exp/Cntr=0.3,0.1

Type RM Length L Ch R = 1 ,148614  ,250.5,251.8,252.2
XS GIS Cut Line= 2
2335039.40180143661341.1370115862335719.12864129660601.393285819
#Sta/Elev= 30
       0 2832.41    86.9 2830.55   142.1 2830.67   190.1 2829.04   280.8 2829.86
   331.3 2828.02     415 2827.33     440 2825.11   521.4 2826.47   532.3 2824.51
   546.9 2823.93   586.5  2825.5   598.2 2826.78   627.8 2825.79   645.5 2827.12
   669.2 2827.29   677.1 2826.78   682.8 2824.09   686.9 2823.06   705.4 2823.03
   725.2 2824.04   739.4 2825.64   763.8 2825.65   776.8 2824.62   799.2 2825.56
   822.9 2824.69   840.6  2828.2   852.8 2829.06   948.9 2831.39  1004.6 2834.12
#Mann= 8 ,-1,0
       0     .05       0      80     .03       0     150     .05       0
     510     .07       0   682.8    .045       0   725.2      .1       0
     820     .08       0     950      .1       0
Bank Sta=682.8,725.2
XS Rating Curve= 0 ,0
Exp/Cntr=0.3,0.1

Type RM Length L Ch R = 1 ,148362  ,296.8,315.7,312.4
XS GIS Cut Line= 2
 2335219.5631792661489.549663357 2336054.0567472660624.618639992
#Sta/Elev= 30
       0 2836.56      29 2836.74    98.8 2834.34   167.9 2834.21   183.9 2829.34
   195.9 2827.08   228.4  2825.2     360 2824.68   419.4  2825.1   445.2 2824.19
   461.8 2826.44   487.3 2824.21   515.6 2826.36   559.7 2826.38   608.9 2825.13
   656.4 2825.85   662.7 2824.53   680.7 2824.07   689.7 2822.78   723.1 2822.78
   730.5 2823.81   749.8 2824.35     773 2823.21   801.7  2826.4   888.1 2826.69
   934.2  2828.9   951.2 2831.22   980.2 2839.89  1002.1 2843.81  1201.9 2857.43
#Mann= 6 ,-1,0
       0     .05       0     360     .07       0     670     .05       0
   680.7    .045       0   730.5     .05       0     770      .1       0
Bank Sta=680.7,730.5
XS Rating Curve= 0 ,0
Exp/Cntr(USF)=0,0
Exp/Cntr=0.3,0.1

Type RM Length L Ch R = 1 ,148047  ,411.9,424.9,437
XS GIS Cut Line= 2
2335261.12380175661565.2720989862336289.46845549660710.895525769
#Sta/Elev= 30
       0 2836.33    75.3 2832.46     134 2832.76     160 2827.68   181.7 2826.69
   340.2 2827.63   388.8 2825.34   457.1 2826.68   482.1 2824.59   541.9 2825.38
   593.1 2824.14   598.7  2823.1   619.8 2822.66   632.3 2823.15   664.4  2824.6
  1016.3 2824.75  1033.7 2828.24  1053.2 2833.83  1064.9 2838.26  1087.3 2843.76
  1129.9 2847.11  1174.1 2849.18  1214.5 2848.75    1227 2846.91  1239.5 2842.17
  1258.3 2841.91  1293.7  2850.5  1308.3 2856.79  1323.1 2857.66    1337 2863.77
#Mann= 6 ,-1,0
       0     .05       0     520     .07       0   598.7    .045       0
   632.3     .07       0     680     .05       0     930      .1       0
Bank Sta=598.7,632.3
XS Rating Curve= 0 ,0
Exp/Cntr(USF)=0,0
Exp/Cntr=0.3,0.1

Type RM Length L Ch R = 1 ,147622  ,176,151,143.7
XS GIS Cut Line= 4
 2335376.7353895661749.3140179732335923.49936377 661307.95638174
2336064.32455437661286.6616273282336483.34823264660944.275705679
#Sta/Elev= 30
       0 2833.51    19.8 2833.73    82.2 2831.75   107.2 2828.38   119.2 2827.71
   255.7 2826.67   299.5 2827.34   331.4 2825.29     390 2826.41   523.6 2825.09
   554.5 2826.68   573.4 2825.06   643.4 2823.87   668.9 2824.91   702.7  2822.7
   743.8 2824.62     764 2822.74     805 2822.77   816.6  2824.3   844.9 2822.39
  1015.4 2821.59  1024.4 2822.58  1033.7 2826.58  1042.2  2827.2  1092.8  2826.7
  1119.3 2828.11  1155.9 2828.08  1320.1 2832.67  1327.9 2833.81  1386.2    2849
#Mann= 6 ,-1,0
       0     .05       0     520     .08       0     670      .1       0
     764    .045       0     805      .1       0  1365.1     .12       0
Bank Sta=764,805
XS Rating Curve= 0 ,0
Exp/Cntr=0.3,0.1

Type RM Length L Ch R = 1 ,147471  ,317.7,333.2,328.2
XS GIS Cut Line= 3
2335699.32944824661840.5728750882336101.10385909 661354.33452559
2336516.57512486661041.589671687
#Sta/Elev= 30
       0 2859.85    82.6 2848.16   102.5 2841.65   123.7 2831.29   139.3 2827.69
   210.4 2825.45   281.4 2826.63   341.1 2823.52     432 2825.57   453.5 2821.53
   476.6 2822.77   488.9 2821.27   535.1 2821.24   564.8  2824.8   591.1 2824.92
   605.3 2823.67   629.3 2825.06   648.1 2824.75   659.6 2822.06   684.7 2823.91
   729.7 2824.73   739.5 2823.87   749.7 2821.24   764.8 2820.72   779.5 2820.84
   794.8 2824.83  1105.2 2831.19  1125.1 2832.84  1135.3 2836.81  1150.8 2840.41
#Mann= 6 ,-1,0
       0      .1       0     410     .08       0     440      .1       0
   488.9    .045       0   535.1      .1       0  970.75     .12       0
Bank Sta=488.9,535.1
XS Rating Curve= 0 ,0
Exp/Cntr(USF)=0,0
Exp/Cntr=0.3,0.1

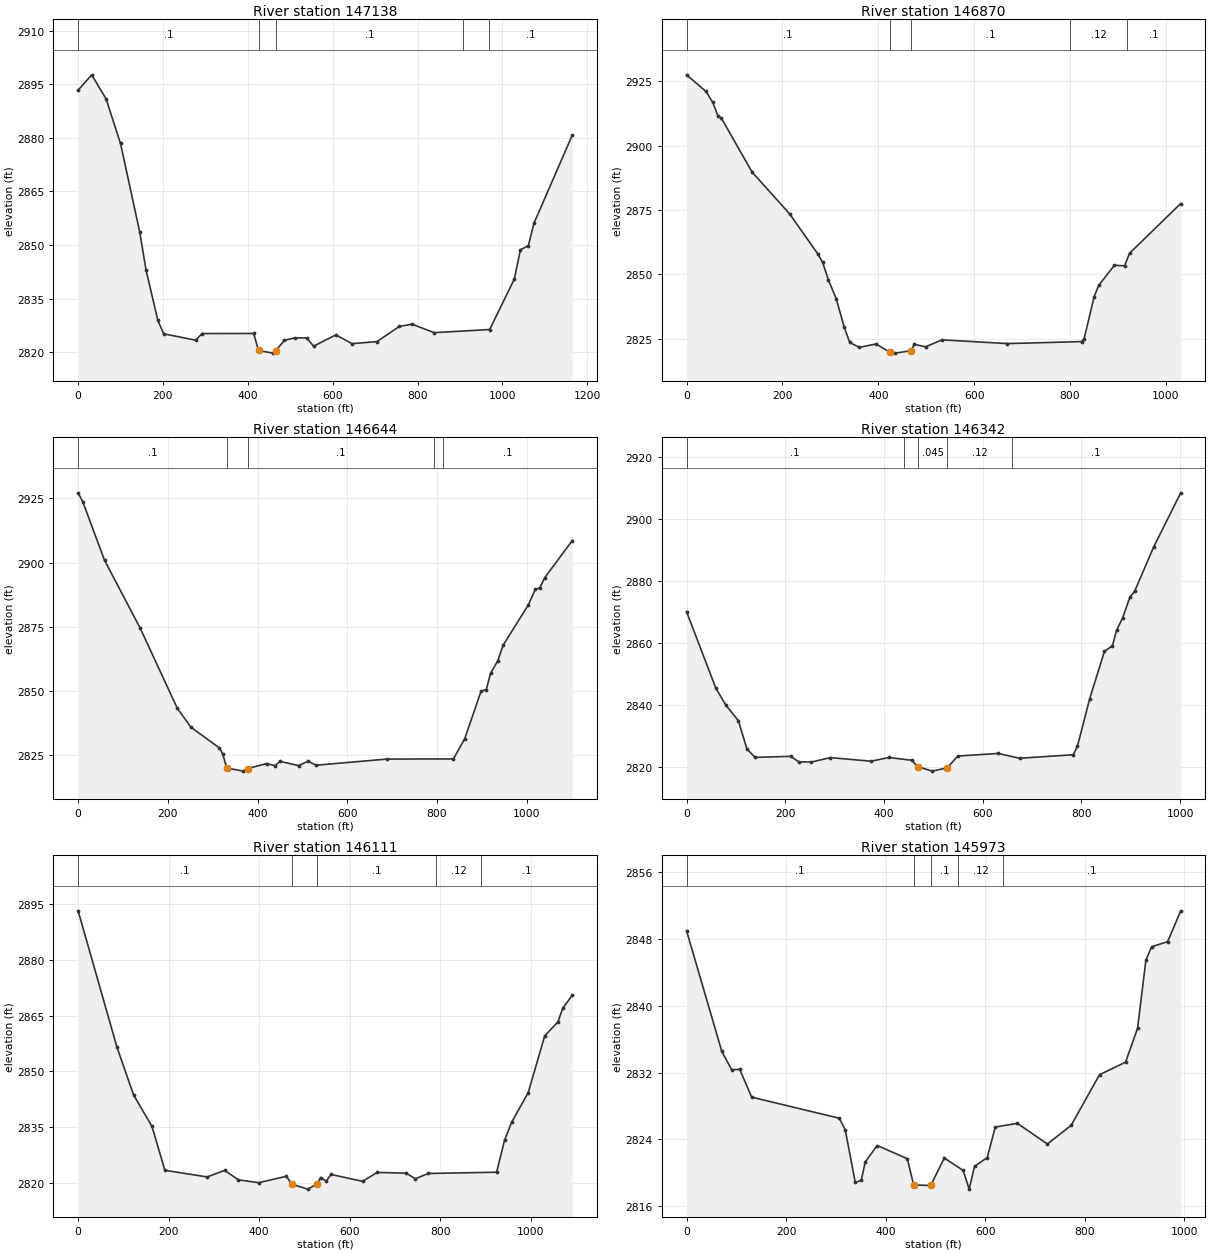
Type RM Length L Ch R = 1 ,147138  ,263.5,267.7,272.4
XS GIS Cut Line= 3
     2335885.939      661948.1472336274.22633803661546.936065564
2336787.90325061661224.289854781
#Sta/Elev= 30
       0 2893.32      32 2897.62    65.9 2890.88    99.9 2878.41   145.1 2853.66
     160 2843.04   187.8 2828.92   201.7 2825.12   276.9 2823.34   292.2 2825.19
   413.9 2825.21   425.2 2820.45   459.1 2819.71   466.1 2820.42   486.4  2823.3
   510.7 2823.98   538.5 2823.96   555.2 2821.66   607.4 2824.81   645.7 2822.36
   704.5 2822.94   757.2 2827.19   787.2 2827.81   839.3 2825.44   970.1 2826.32
  1028.3 2840.47  1042.6 2848.65  1061.3 2849.78  1074.5 2856.07  1164.9 2880.76
#Mann= 5 ,-1,0
       0      .1       0   425.2    .045       0   466.1      .1       0
  908.33     .12       0  968.33      .1       0
Bank Sta=425.2,466.1
XS Rating Curve= 0 ,0
Exp/Cntr=0.3,0.1

Type RM Length L Ch R = 1 ,146870  ,230.7,225.5,223.2
XS GIS Cut Line= 4
2336069.31784079662107.7618689642336316.35251512661857.247833016
2336479.88251081661745.908261484 2336845.2154799 661432.76571655
#Sta/Elev= 30
       0  2927.5    40.6 2921.04    54.8 2916.75    65.4 2911.57    72.4 2910.74
   136.8 2889.69   214.9  2873.5   273.3 2858.06   283.9 2854.62   295.7 2847.92
   312.2 2840.51   328.8 2829.54   340.4 2823.52   360.4  2821.6   395.2 2822.92
   424.2  2819.7   435.2 2819.36   467.8  2820.3   475.5 2822.76   498.6 2821.81
   533.1 2824.52   669.5 2823.07     824 2823.84   829.3 2824.94   850.3 2841.32
   859.6 2845.64   892.5 2853.49   913.6 2853.28   924.1 2858.16  1030.8 2877.49
#Mann= 5 ,-1,0
       0      .1       0   424.2    .045       0   467.8      .1       0
  799.66     .12       0  919.66      .1       0
Bank Sta=424.2,467.8
XS Rating Curve= 0 ,0
Exp/Cntr(USF)=0,0
Exp/Cntr=0.3,0.1

Type RM Length L Ch R = 1 ,146644  ,297.7,302.8,316.9
XS GIS Cut Line= 3
2336122.42135551662198.4531906262336327.22766416662106.421618749
2336994.74067169661537.165381251
#Sta/Elev= 30
       0  2927.1    10.7  2923.5    58.9 2900.86   137.9 2874.67   221.2 2843.32
   251.6 2835.97   315.1  2827.9   322.6 2825.52   331.1 2820.14     368  2818.9
   378.2 2819.92   420.3 2821.84   438.9 2821.02   450.2 2822.69   491.5 2821.05
   512.7 2822.76   530.7  2821.2   688.6 2823.59   836.7 2823.64   861.7 2831.38
   898.5 2850.01   909.9 2850.58   919.7    2857   935.4  2861.7   947.7 2867.88
  1003.8 2883.54  1019.6 2889.68  1029.1 2890.08  1040.6 2894.17  1101.8 2908.56
#Mann= 5 ,-1,0
       0      .1       0   331.1    .045       0   378.2      .1       0
  794.53     .12       0  814.53      .1       0
Bank Sta=331.1,378.2
XS Rating Curve= 0 ,0
Exp/Cntr=0.3,0.1

Type RM Length L Ch R = 1 ,146342  ,219.3,230.6,239.9
XS GIS Cut Line= 4
2336249.00460005662257.6117106722336598.27440039662136.622825586
2336753.50542277662070.4213601612337196.63100255661937.273150055
#Sta/Elev= 30
       0 2870.01    59.4 2845.26    79.6 2839.84     105 2834.79   122.3 2825.69
   138.8 2822.94   210.8 2823.29   227.7 2821.51   253.1 2821.45   291.2 2822.87
   373.7 2821.72   410.3 2822.91     456 2822.01   468.2 2819.98   497.8 2818.51
   528.2 2819.58   549.5 2823.38   631.5 2824.22   674.8 2822.66   783.4 2823.81
   791.8 2826.47   816.8 2841.92   846.6  2857.2   862.8 2858.97   871.1 2863.93
   883.7 2868.07     898 2874.58   907.7 2876.56   946.5 2890.94  1001.1 2908.36
#Mann= 5 ,-1,0
       0      .1       0  439.63     .12       0   468.2    .045       0
   528.2     .12       0  658.39      .1       0
Bank Sta=468.2,528.2
XS Rating Curve= 0 ,0
Exp/Cntr(USF)=0,0
Exp/Cntr=0.3,0.1

Type RM Length L Ch R = 1 ,146111  ,150.2,138.4,122.6
XS GIS Cut Line= 4
2336183.76387203662353.6295545172336622.50194413662272.682177774
2336766.90627486662280.5855307932337265.14310424662231.459445483
#Sta/Elev= 30
       0 2893.13    85.8 2856.52   122.4 2843.73   163.1 2835.25   191.6 2823.48
   285.1 2821.69   323.5 2823.44   354.1 2820.91     399 2820.15   459.8 2821.87
   472.8 2819.72   506.7 2818.42   527.9 2819.77   527.9 2819.78   535.6 2821.54
     548 2820.55   558.3 2822.37   628.2 2820.51   660.4  2822.9   724.7 2822.71
   744.8 2821.19   772.9 2822.62   924.3 2822.96   941.7 2831.52   957.8 2836.48
     994 2844.29  1030.4 2859.55  1059.7 2863.32  1070.3 2866.99  1091.4 2870.45
#Mann= 5 ,-1,0
       0      .1       0   472.8    .045       0   527.9      .1       0
  790.76     .12       0  890.76      .1       0
Bank Sta=472.8,527.9
XS Rating Curve= 0 ,0
Exp/Cntr=0.3,0.1

Type RM Length L Ch R = 1 ,145973  ,290.4,317.3,323.9
XS GIS Cut Line= 4
2336241.42112107662453.6892189452336646.36863664662440.745691049
2336720.33165319662388.9715794692337214.22326911 662445.81280714
#Sta/Elev= 30
       0 2849.02    70.8 2834.55    90.8 2832.34   106.8 2832.39   130.8 2829.06
   306.9 2826.53   318.9 2825.11   338.9 2818.83   350.9 2819.08   358.9 2821.28
   382.9 2823.26   443.5 2821.68   456.2 2818.53   490.4 2818.47   517.8 2821.76
   555.7 2820.27   567.7 2818.03   578.5 2820.77     604 2821.81   620.1 2825.47
   664.4 2825.92   724.8 2823.44   772.6 2825.68   829.5 2831.75   881.8 2833.25
     906 2837.33   922.7  2845.5   934.2 2847.09   966.4 2847.71   992.6  2851.4
#Mann= 5 ,-1,0
       0      .1       0   456.2    .045       0   490.4      .1       0
  545.44     .12       0  635.44      .1       0
Bank Sta=456.2,490.4
XS Rating Curve= 0 ,0
Exp/Cntr(USF)=0,0
Exp/Cntr=0.3,0.1

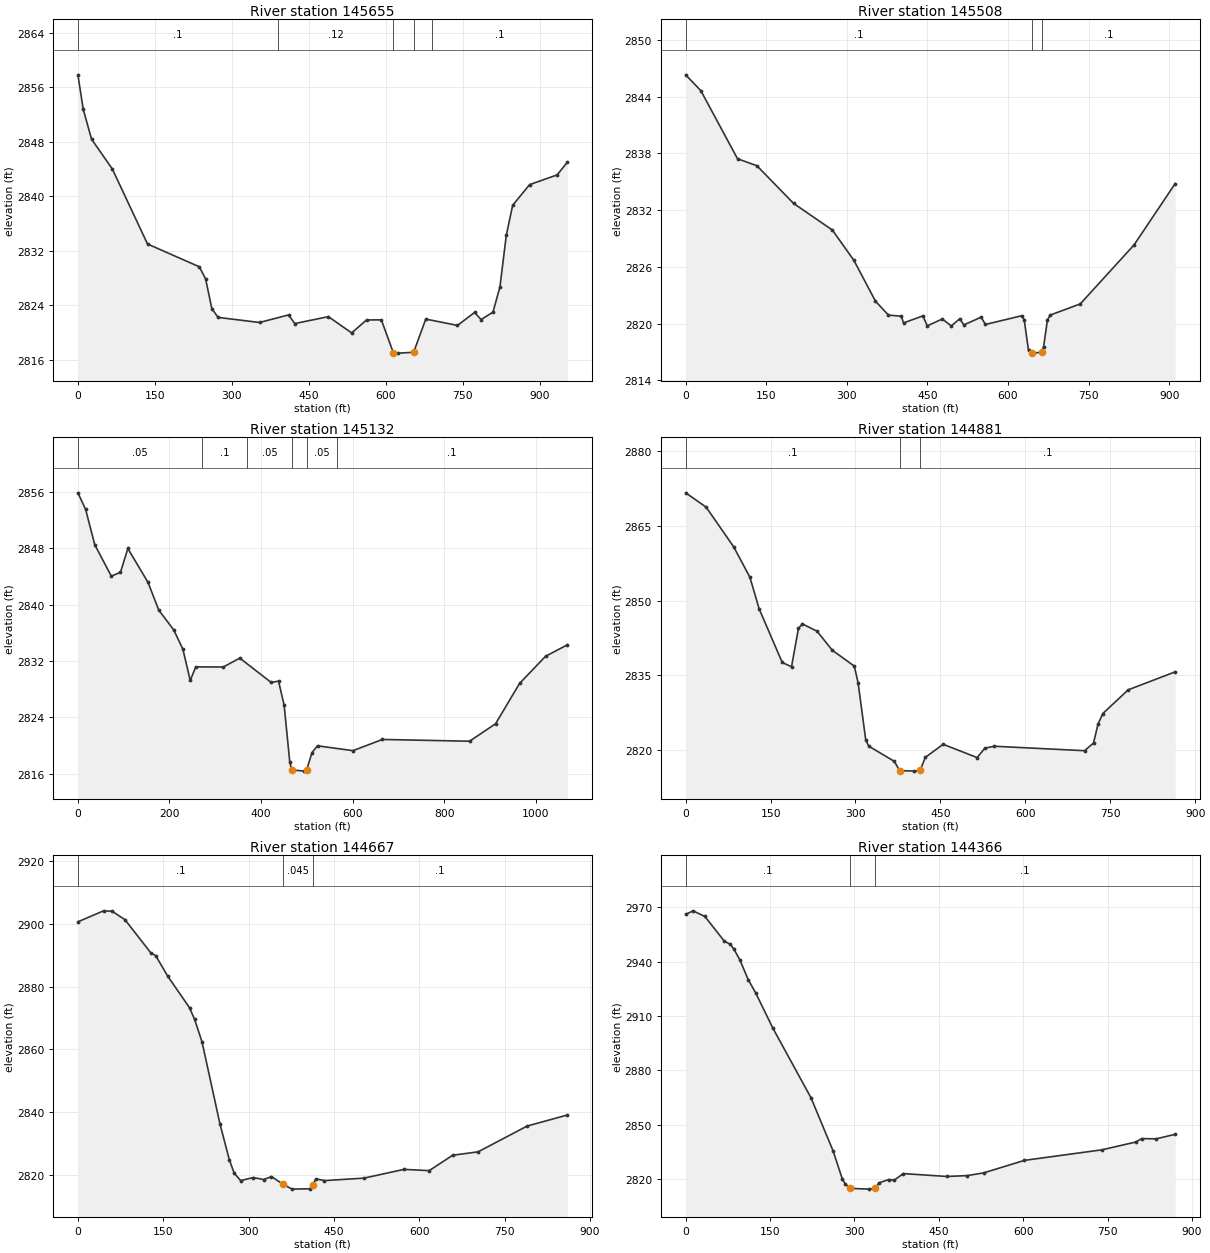
Type RM Length L Ch R = 1 ,145655  ,148.9,146.9,145.6
XS GIS Cut Line= 3
      2336185.84      662509.939 2336632.1030901662574.048511862
2337119.72019434662698.227597172
#Sta/Elev= 30
       0 2857.82    10.4 2852.76    26.6 2848.37      67    2844   135.7 2832.97
   236.7 2829.62   248.9 2827.83     261 2823.49   273.1 2822.19   353.9 2821.44
   410.5 2822.55   422.6 2821.28   488.1  2822.3   533.5 2819.91   562.4 2821.81
   591.3 2821.83   614.7    2817   624.3 2816.94   654.2 2817.06   677.9 2821.94
   739.7 2821.01   772.9 2822.91   785.8 2821.87   808.8 2822.96   822.4 2826.66
   834.8 2834.24   847.2 2838.65   880.2 2841.69   933.9 2843.12     954    2845
#Mann= 5 ,-1,0
       0      .1       0     390     .12       0   614.7    .045       0
   654.2     .12       0  690.84      .1       0
Bank Sta=614.7,654.2
XS Rating Curve= 0 ,0
Exp/Cntr=0.3,0.1

Type RM Length L Ch R = 1 ,145508  ,375.6,375.8,357.3
XS GIS Cut Line= 2
2336123.92719239662710.3097801052337032.47270941662780.456841596
#Sta/Elev= 30
       0  2846.3    28.3 2844.62    96.5 2837.43   132.6 2836.69   200.8 2832.71
   273.1 2829.89   313.2 2826.68   353.3 2822.37   377.4  2820.9   401.4 2820.78
   405.5 2820.07   441.6 2820.82   449.6 2819.76   477.7 2820.49   494.5 2819.75
   510.2 2820.52   517.8 2819.86   549.9 2820.68   557.9 2819.91   626.1 2820.84
   630.1 2820.42   638.1 2817.17   644.9 2816.88   662.3 2816.97   666.2 2817.55
   673.3 2820.37   678.3  2820.9   734.4 2822.08   834.7 2828.33   911.2 2834.81
#Mann= 3 ,-1,0
       0      .1       0   644.9    .045       0   662.3      .1       0
Bank Sta=644.9,662.3
XS Rating Curve= 0 ,0
Exp/Cntr(USF)=0,0
Exp/Cntr=0.3,0.1

Type RM Length L Ch R = 1 ,145132  ,260.1,251.9,233.4
XS GIS Cut Line= 4
2336003.32829598662838.176769311 2336388.4243123662863.547016322
2336673.04425101662909.2222341462337063.46923069662848.446032644
#Sta/Elev= 30
       0 2855.83    16.9 2853.48    36.9 2848.46      73 2844.02      93 2844.56
   109.1 2847.94   153.2 2843.13   176.6 2839.21   209.3  2836.4   229.3 2833.66
   245.4 2829.23   257.4 2831.16   317.5 2831.14   353.6  2832.4     422 2828.96
   438.3 2829.13   450.5 2825.71   462.7 2817.73   466.7 2816.56   494.6 2816.38
   499.5 2816.52   511.3 2819.01   523.4 2819.97   600.8 2819.28   665.2 2820.87
   855.5 2820.62   912.2 2823.09   964.8 2828.82  1021.5 2832.66  1069.3 2834.29
#Mann= 6 ,-1,0
       0     .05       0     270      .1       0     370     .05       0
   466.7    .045       0   499.5     .05       0  565.93      .1       0
Bank Sta=466.7,499.5
XS Rating Curve= 0 ,0
Exp/Cntr=0.3,0.1

Type RM Length L Ch R = 1 ,144881  ,209.4,213.2,216.8
XS GIS Cut Line= 4
2336292.84254398663200.4937256692336498.29536771663159.403160923
 2336710.5966189662995.0409019382337089.54293822662917.425390751
#Sta/Elev= 30
       0 2871.67    36.2 2868.79      85 2860.77   113.5 2854.67   129.9 2848.29
   170.6 2837.53     187 2836.66   199.2 2844.37   206.2 2845.28   232.1 2843.82
   258.9    2840   297.9 2836.79   304.6 2833.45   318.1 2821.93   323.6 2820.67
   368.7 2817.62   377.8 2815.78   404.1 2815.66   414.2 2815.82   423.4 2818.43
   454.8 2821.06   514.8 2818.39   528.6 2820.28     545 2820.67   704.6 2819.77
   720.5 2821.32   728.3 2825.08   736.9 2827.25   781.8 2832.03   864.8 2835.64
#Mann= 3 ,-1,0
       0      .1       0   377.8    .045       0   414.2      .1       0
Bank Sta=377.8,414.2
XS Rating Curve= 0 ,0
Exp/Cntr(USF)=0,0
Exp/Cntr=0.3,0.1

Type RM Length L Ch R = 1 ,144667  ,313.9,301,280
XS GIS Cut Line= 3
2336422.99308161663396.9304428742336902.78775299663145.029344942
 2337161.8983123662959.823048966
#Sta/Elev= 30
       0  2900.7    45.1 2904.21    60.1 2904.08    82.7 2901.39   127.8 2890.88
   136.9 2889.87   157.7 2883.41   196.2 2873.29   205.1 2869.58   218.2 2862.36
   249.5 2836.35   266.2 2824.73   274.8 2820.48     286 2818.15   308.5  2819.1
   326.6 2818.47   340.2 2819.42   360.9 2816.92   376.3 2815.41   407.9 2815.53
   412.4 2816.85   418.4  2818.7   433.2 2818.13   502.8 2818.92   573.1 2821.71
   617.4 2821.31   658.6 2826.21   703.4 2827.31   789.4 2835.53   860.4 2839.07
#Mann= 3 ,-1,0
       0      .1       0   360.9    .045       0   412.4      .1       0
Bank Sta=360.9,412.4
XS Rating Curve= 0 ,0
Exp/Cntr=0.3,0.1

Type RM Length L Ch R = 1 ,144366  ,257.1,259.1,257.3
XS GIS Cut Line= 3
2336851.05532895663677.0273441422337054.10118831663161.492322841
2337288.28361539662949.229873913
#Sta/Elev= 30
       0 2966.07    13.1 2968.05    34.2 2964.93    68.5  2951.4    79.5 2949.55
    85.8 2946.89    96.4 2940.94   111.2 2930.09   124.5 2922.75   154.6 2903.55
   222.8 2864.89   262.1 2835.56   278.3 2820.23   283.6 2817.41   292.2 2814.94
   326.6 2814.53   336.9 2815.08   343.8 2818.01     361 2819.81   370.9 2819.52
   386.8  2823.1   464.1 2821.52   500.4 2821.99   529.7  2823.5   602.2  2830.4
   739.8 2836.21   799.8 2840.51   810.6  2842.4   836.1 2842.27   870.1 2844.77
#Mann= 3 ,-1,0
       0      .1       0   292.2    .045       0   336.9      .1       0
Bank Sta=292.2,336.9
XS Rating Curve= 0 ,0
Exp/Cntr(USF)=0,0
Exp/Cntr=0.3,0.1