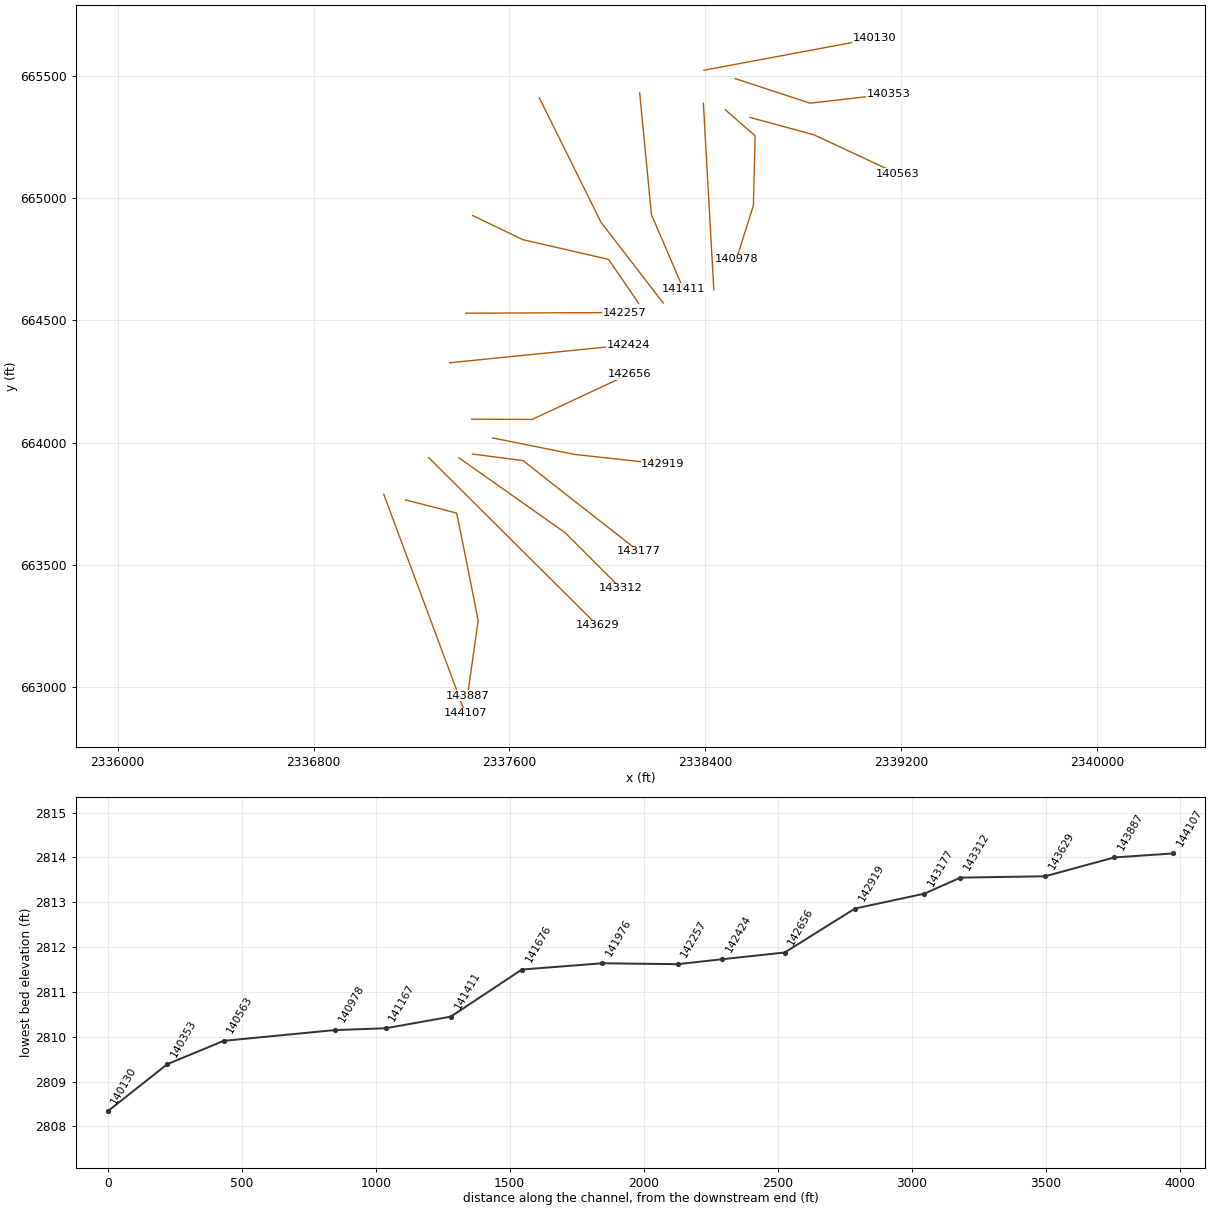
HEC-RAS study GLADYFK.prj: GLADYFK

--- GLADYFK.g01 (geometry) --- (continued)

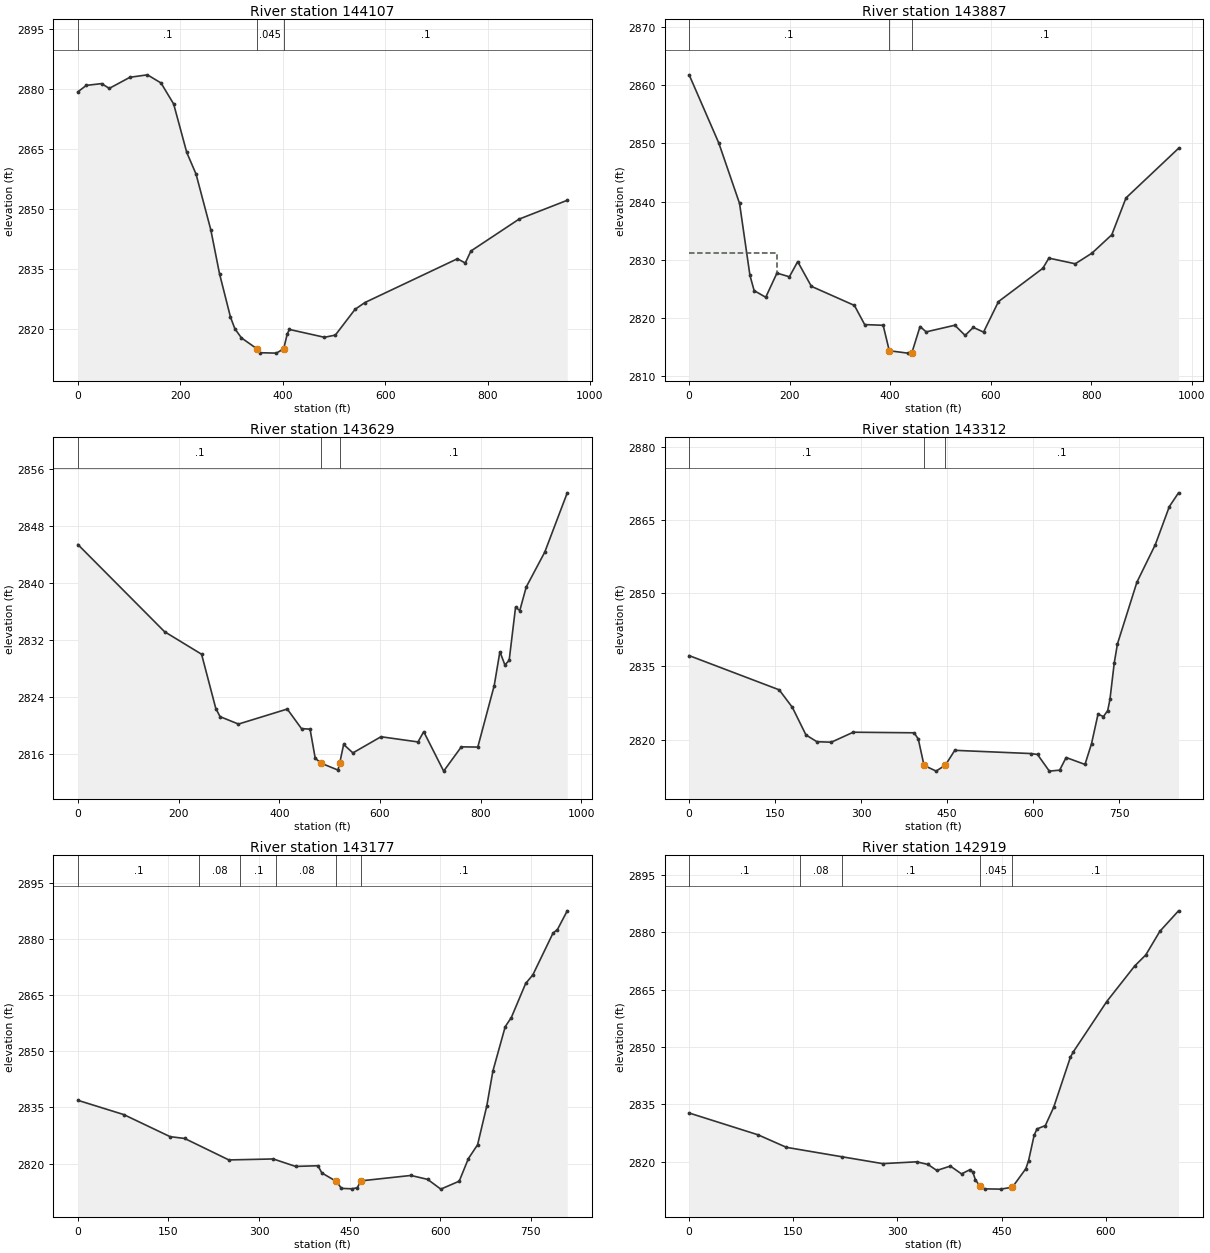
Type RM Length L Ch R = 1 ,144107  ,225.3,220.6,218.6
XS GIS Cut Line= 2
2337086.81604897663788.4943612642337419.70747333662892.776496206
#Sta/Elev= 30
       0 2879.25    16.3 2880.86    46.2 2881.31    61.3 2880.12   101.7 2882.89
   135.8  2883.5   162.3 2881.47     187 2876.23   212.6 2864.14   230.7 2858.76
   259.6 2844.82   276.6 2833.87     298 2823.06   306.5 2820.18   319.3  2817.9
   349.2 2815.21   356.5 2814.19   387.6 2814.09   401.9 2815.16   408.9 2818.93
   413.2 2819.99   481.5 2818.04   502.8 2818.59   541.2 2825.01   560.5 2826.71
     741 2837.62   756.5 2836.57   767.4 2839.55   861.3  2847.5   955.6 2852.21
#Mann= 3 ,-1,0
       0      .1       0   349.2    .045       0   401.9      .1       0
Bank Sta=349.2,401.9
XS Rating Curve= 0 ,0
Exp/Cntr=0.3,0.1

Type RM Length L Ch R = 1 ,143887  ,239.1,258.1,264.5
XS GIS Cut Line= 5
2337175.04551223663765.7259999892337384.46564746663711.501143546
2337418.54188145663544.2458724562337472.38433391663272.489305886
2337428.99676103662965.742025906
#Sta/Elev= 30
       0 2861.78      59 2850.07   100.3  2839.7     121 2827.34   129.3 2824.74
   152.4 2823.59   174.7 2827.74   199.5 2827.11     216 2829.71   243.2 2825.47
   328.9 2822.19   349.3  2818.9   386.1 2818.78   398.3 2814.41     435    2814
   443.2 2814.05   459.5 2818.57   471.7 2817.65   528.8 2818.79   549.2 2817.04
   565.5 2818.42   585.9 2817.61   615.6 2822.85   703.8 2828.56   715.9 2830.31
   768.4 2829.34   801.7 2831.17   841.1 2834.32   869.4 2840.65   973.9 2849.16
#Mann= 3 ,-1,0
       0      .1       0   398.3    .045       0   443.2      .1       0
#XS Ineff= 2 , 0
          175.24 2831.11
Permanent Ineff=
       F       F
Bank Sta=398.3,443.2
XS Rating Curve= 0 ,0
Exp/Cntr(USF)=0,0
Exp/Cntr=0.3,0.1

Type RM Length L Ch R = 1 ,143629  ,305.6,316.2,311.5
XS GIS Cut Line= 3
     2337270.078      663938.581 2337744.3742159663466.424948839
2337958.99123143663252.676446327
#Sta/Elev= 30
       0 2845.41   172.1 2833.17   245.7    2830     274 2822.37   282.5 2821.23
     319 2820.19   415.9  2822.3   444.2 2819.55   461.2 2819.48   471.4 2815.41
   482.7 2814.71   516.6 2813.73   520.1 2814.72   527.9 2817.33   546.3 2816.14
   602.1 2818.41   675.6 2817.68     687 2819.12   726.6 2813.58   761.7 2816.99
   794.4 2816.96     827 2825.59   838.3 2830.35   848.2  2828.5   856.7 2829.14
   869.4  2836.6   877.8 2836.13   890.6 2839.44   927.4 2844.34   972.1 2852.67
#Mann= 3 ,-1,0
       0      .1       0   482.7    .045       0   520.1      .1       0
Bank Sta=482.7,520.1
XS Rating Curve= 0 ,0
Exp/Cntr=0.3,0.1

Type RM Length L Ch R = 1 ,143312  ,136,135.9,136.6
XS GIS Cut Line= 3
2337393.78948048663937.6142141912337827.29493855663631.489506831
2338055.48285048663403.286564068
#Sta/Elev= 30
       0 2837.21     157  2830.2     180 2826.61   203.7 2820.96   222.7 2819.58
   247.8 2819.47   286.2 2821.52   392.4  2821.4   399.6 2820.11   409.6 2814.72
   430.7 2813.56   446.9 2814.78   463.2 2817.81   596.2 2817.15   607.5 2816.96
   628.1 2813.55   646.1 2813.75   657.4 2816.34   690.3 2814.92   701.7 2819.18
     713  2825.2   722.5 2824.73   729.9 2825.95   733.8 2828.23   741.3 2835.69
   746.9 2839.61   780.9 2852.27     813 2859.96   837.4 2867.74   853.4 2870.55
#Mann= 3 ,-1,0
       0      .1       0   409.6    .045       0   446.9      .1       0
Bank Sta=409.6,446.9
XS Rating Curve= 0 ,0
Exp/Cntr(USF)=0,0
Exp/Cntr=0.3,0.1

Type RM Length L Ch R = 1 ,143177  ,245.1,257.8,264.7
XS GIS Cut Line= 4
2337448.85517031663952.9937037692337655.81165228 663926.10896075
2337765.46201559663839.4022288142338129.08387051663554.645175255
#Sta/Elev= 30
       0 2836.89      76 2833.08   152.7 2827.19   176.8 2826.71     250 2820.98
   323.5 2821.24   360.5 2819.25   397.5 2819.43     404  2817.5   428.1 2815.24
   436.4 2813.39   453.5 2813.28   462.4 2813.54   468.8 2815.39   468.8  2815.4
   551.5 2816.84   579.2 2815.79   600.9 2813.19   631.4 2815.31   646.6 2821.34
   661.8 2825.02   677.1 2835.42   687.2 2844.73   707.6 2856.55   717.7 2858.98
   741.4 2868.06   753.3 2870.36   786.8 2881.53   793.9 2882.42   810.3 2887.45
#Mann= 6 ,-1,0
       0      .1       0     200     .08       0   268.7      .1       0
   328.7     .08       0   428.1    .045       0   468.8      .1       0
Bank Sta=428.1,468.8
XS Rating Curve= 0 ,0
Exp/Cntr=0.3,0.1

Type RM Length L Ch R = 1 ,142919  ,250.4,262.4,275.6
XS GIS Cut Line= 3
2337530.81760785664018.9617645932337866.19327347663951.322974887
2338226.93348523663911.867014225
#Sta/Elev= 30
       0 2832.75    99.3 2827.05   140.1 2823.78     220 2821.32   278.9 2819.52
   327.8    2820   344.1  2819.3   356.8 2817.74   376.3 2818.88   392.4 2816.84
   404.5 2817.94   408.5 2817.36   412.5 2815.26   418.8 2813.67   425.7 2812.93
   448.7 2812.86   465.6 2813.35     485 2818.19     489 2820.32     497 2826.94
   501.1 2828.59   513.1 2829.46   525.2 2834.27   549.3 2847.36   553.4 2848.72
   601.6 2861.88   641.9 2871.18   657.8 2874.05   678.1 2880.23     705 2885.58
#Mann= 5 ,-1,0
       0      .1       0     160     .08       0     220      .1       0
   418.8    .045       0   465.6      .1       0
Bank Sta=418.8,465.6
XS Rating Curve= 0 ,0
Exp/Cntr(USF)=0,0
Exp/Cntr=0.3,0.1

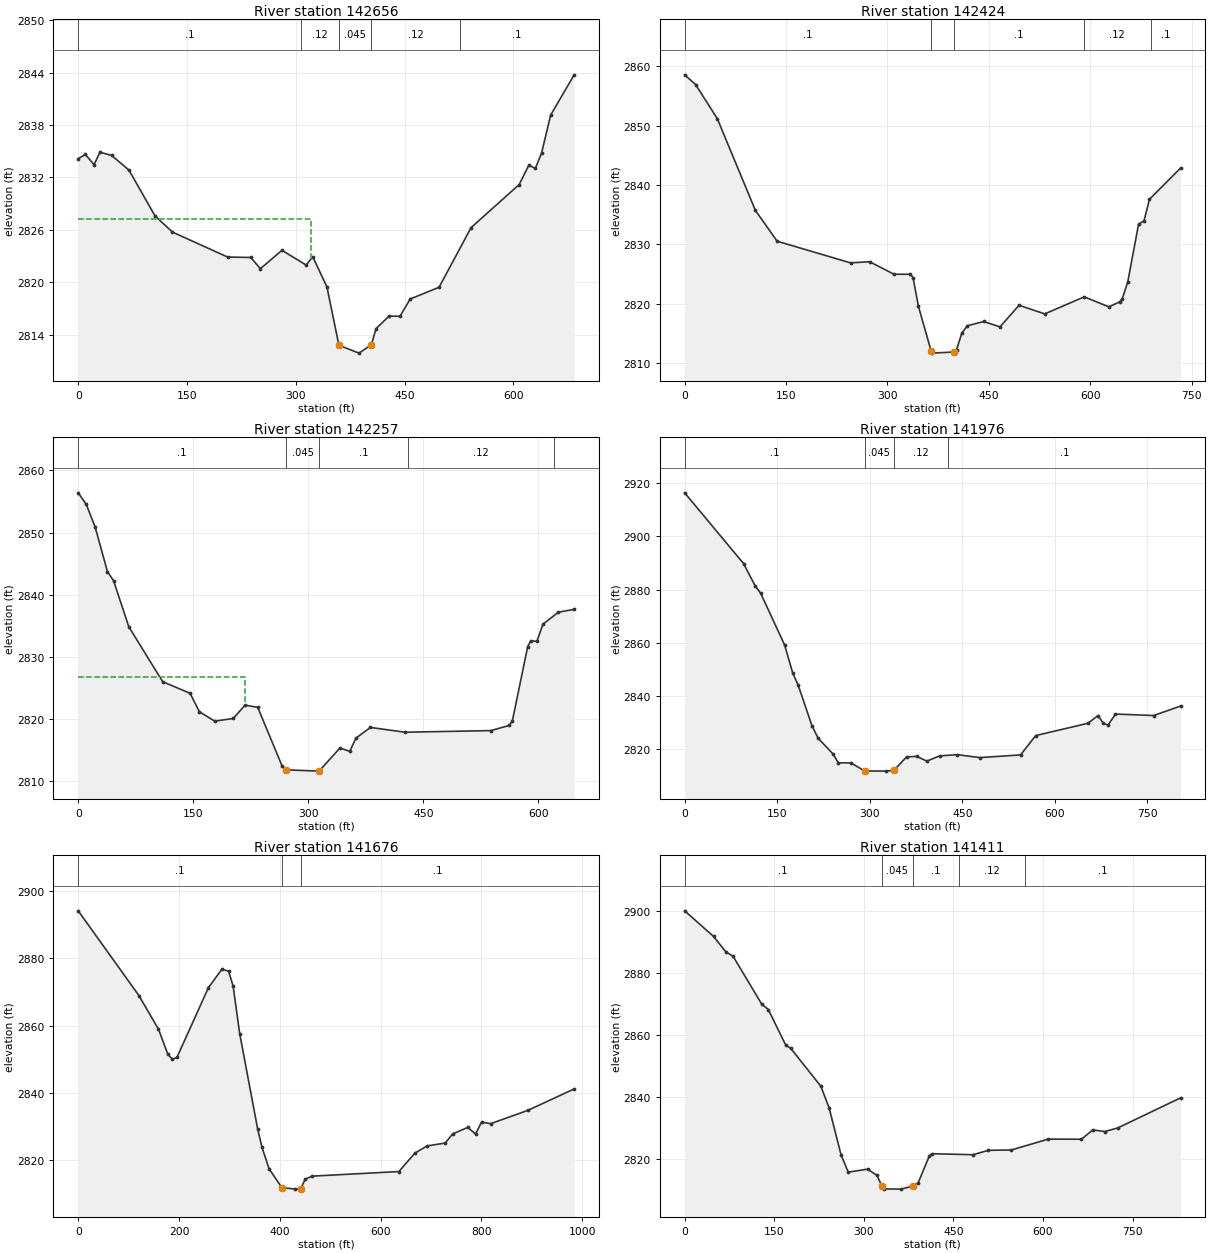
Type RM Length L Ch R = 1 ,142656  ,237,232.4,224.5
XS GIS Cut Line= 3
2337446.32193314664095.2981919482337692.95764881 664094.47902373
2338088.89600431664279.625852624
#Sta/Elev= 30
       0 2834.14     9.9 2834.62    21.9 2833.46    29.9 2834.88    45.9 2834.52
    69.9 2832.84   105.9 2827.59   129.9 2825.74   205.9 2822.88   237.9 2822.83
   251.1 2821.55   280.9 2823.65   314.3 2821.96   323.3 2822.92   342.9 2819.46
   359.4 2812.78   387.1 2811.88   404.1 2812.83   410.6 2814.69   428.6 2816.12
   443.6  2816.1   457.7 2818.08   497.5 2819.42   541.6 2826.25   607.9 2831.18
   621.1 2833.37   630.2 2833.04   638.8 2834.79   651.3 2839.13   683.7 2843.74
#Mann= 5 ,-1,0
       0      .1       0  306.64     .12       0   359.4    .045       0
   404.1     .12       0  526.64      .1       0
#XS Ineff= 2 , 0
          321.31 2827.24
Permanent Ineff=
       F       F
Bank Sta=359.4,404.1
XS Rating Curve= 0 ,0
Exp/Cntr=0.3,0.1

Type RM Length L Ch R = 1 ,142424  ,169.9,167.4,165.4
XS GIS Cut Line= 2
2337356.08406777664326.1546011732338086.01934001664399.429956688
#Sta/Elev= 30
       0 2858.53    16.2 2856.89    48.3 2851.15   104.6 2835.73   136.8 2830.55
   245.3 2826.91   273.5  2827.1   309.6    2825   333.8 2824.99   337.8 2824.44
   345.8 2819.59   364.5  2812.1   365.9 2811.73   398.1 2811.92   402.1 2812.29
   410.1 2815.14   418.2 2816.33   442.3 2817.05   466.4 2816.14   494.6 2819.78
   532.6 2818.33     591 2821.19   627.6 2819.51   643.3 2820.35   647.3 2820.87
   655.4  2823.7   671.4 2833.41   679.5 2833.98   687.5  2837.6   733.6 2842.86
#Mann= 5 ,-1,0
       0      .1       0   364.5    .045       0   398.1      .1       0
     590     .12       0     690      .1       0
Bank Sta=364.5,398.1
XS Rating Curve= 0 ,0
Exp/Cntr(USF)=0,0
Exp/Cntr=0.3,0.1

Type RM Length L Ch R = 1 ,142257  ,286,280.3,275.5
XS GIS Cut Line= 2
 2337422.0463788664528.8008200252338068.74799709664531.367428254
#Sta/Elev= 30
       0 2856.39    10.5 2854.53    22.1 2850.88    38.1 2843.73    46.1 2842.26
      66 2834.84   110.1 2826.01   145.9 2824.14   158.1 2821.16   178.1 2819.66
   202.1 2820.09   217.6 2822.24   234.1 2821.88   266.1 2812.38   270.8 2811.83
   314.1 2811.62   341.2 2815.33   354.1 2814.81   362.1 2816.92     381 2818.65
   426.1 2817.88   538.1 2818.14   562.1 2818.97   566.1 2819.69   586.1 2831.65
   590.1 2832.59   598.1  2832.5   606.1 2835.27   626.1 2837.18   646.7 2837.65
#Mann= 5 ,-1,0
       0      .1       0   270.8    .045       0   314.1      .1       0
     430     .12       0     620      .1       0
#XS Ineff= 2 , 0
          217.64 2826.77
Permanent Ineff=
       F       F
Bank Sta=270.8,314.1
XS Rating Curve= 0 ,0
Exp/Cntr=0.3,0.1

Type RM Length L Ch R = 1 ,141976  ,318.3,300.5,280.9
XS GIS Cut Line= 4
2337450.19504196664927.7953657442337655.19424076 664829.18094725
2338004.85915582664748.8290019762338127.83816237664569.101686643
#Sta/Elev= 30
       0  2916.4    95.4 2889.79   114.3 2881.36   123.3 2878.55     162 2859.13
   175.3  2848.5   184.2  2843.9   206.4 2828.69   216.2 2824.09   240.8 2818.02
     249 2814.77   269.5 2814.73   291.7 2811.71     327 2811.64   339.3 2811.98
   359.8 2817.02   376.2 2817.18   392.7 2815.41   413.2 2817.37   441.8 2817.84
   478.6 2816.73   544.5 2817.75   569.1 2825.03   653.7 2829.65   670.1 2832.55
   677.9 2829.91   686.2 2828.92   698.4 2833.13   760.3 2832.57     804 2836.15
#Mann= 4 ,-1,0
       0      .1       0   291.7    .045       0   339.3     .12       0
  427.49      .1       0
Bank Sta=291.7,339.3
XS Rating Curve= 0 ,0
Exp/Cntr(USF)=0,0
Exp/Cntr=0.3,0.1

Type RM Length L Ch R = 1 ,141676  ,271.6,265,257
XS GIS Cut Line= 3
2337722.31190847665408.6269084742337974.16763766664900.068996233
 2338228.3588162664570.161817702
#Sta/Elev= 30
       0 2893.99   120.4 2868.88   159.2 2858.94   177.9 2851.45   186.9 2850.01
   195.8 2850.52   258.3 2871.19   285.1  2876.7   298.4  2876.1   307.4 2871.67
   320.4 2857.59   356.2 2829.22   364.7 2823.86   378.8  2817.5     404 2811.97
   430.9  2811.5   441.3 2811.53   450.2 2814.42   463.9 2815.35   636.3 2816.71
     668 2822.18   692.3 2824.31   728.1 2825.15   742.8 2827.85   773.1  2829.8
   788.3 2827.81   800.2 2831.36   818.6 2830.91   891.9 2834.83     984  2841.2
#Mann= 3 ,-1,0
       0      .1       0     404    .045       0   441.3      .1       0
Bank Sta=404,441.3
XS Rating Curve= 0 ,0
Exp/Cntr=0.3,0.1

Type RM Length L Ch R = 1 ,141411  ,245.1,243.6,243.1
XS GIS Cut Line= 3
2338132.05258277665429.8378031292338179.99157498664932.185407869
2338310.11169667664628.571790577
#Sta/Elev= 30
       0 2900.14    48.4 2891.88      69  2886.9      81  2885.5     129 2870.08
     140 2868.32   169.4 2856.78   177.5 2855.84     228 2843.61   241.8 2836.64
   261.9 2821.43   273.9 2815.92   306.1 2816.89   322.1 2814.87   329.7 2811.57
   334.2 2810.53   362.3 2810.45   381.9 2811.43   390.5 2812.29   409.7 2821.21
   414.6 2821.86   482.9 2821.54   508.5 2822.96   546.7 2823.06     609 2826.58
   664.2 2826.53   683.2 2829.53   703.4 2829.01   724.8 2830.15   830.3 2839.87
#Mann= 5 ,-1,0
       0      .1       0   329.7    .045       0   381.9      .1       0
     460     .12       0  569.96      .1       0
Bank Sta=329.7,381.9
XS Rating Curve= 0 ,0
Exp/Cntr(USF)=0,0
Exp/Cntr=0.3,0.1

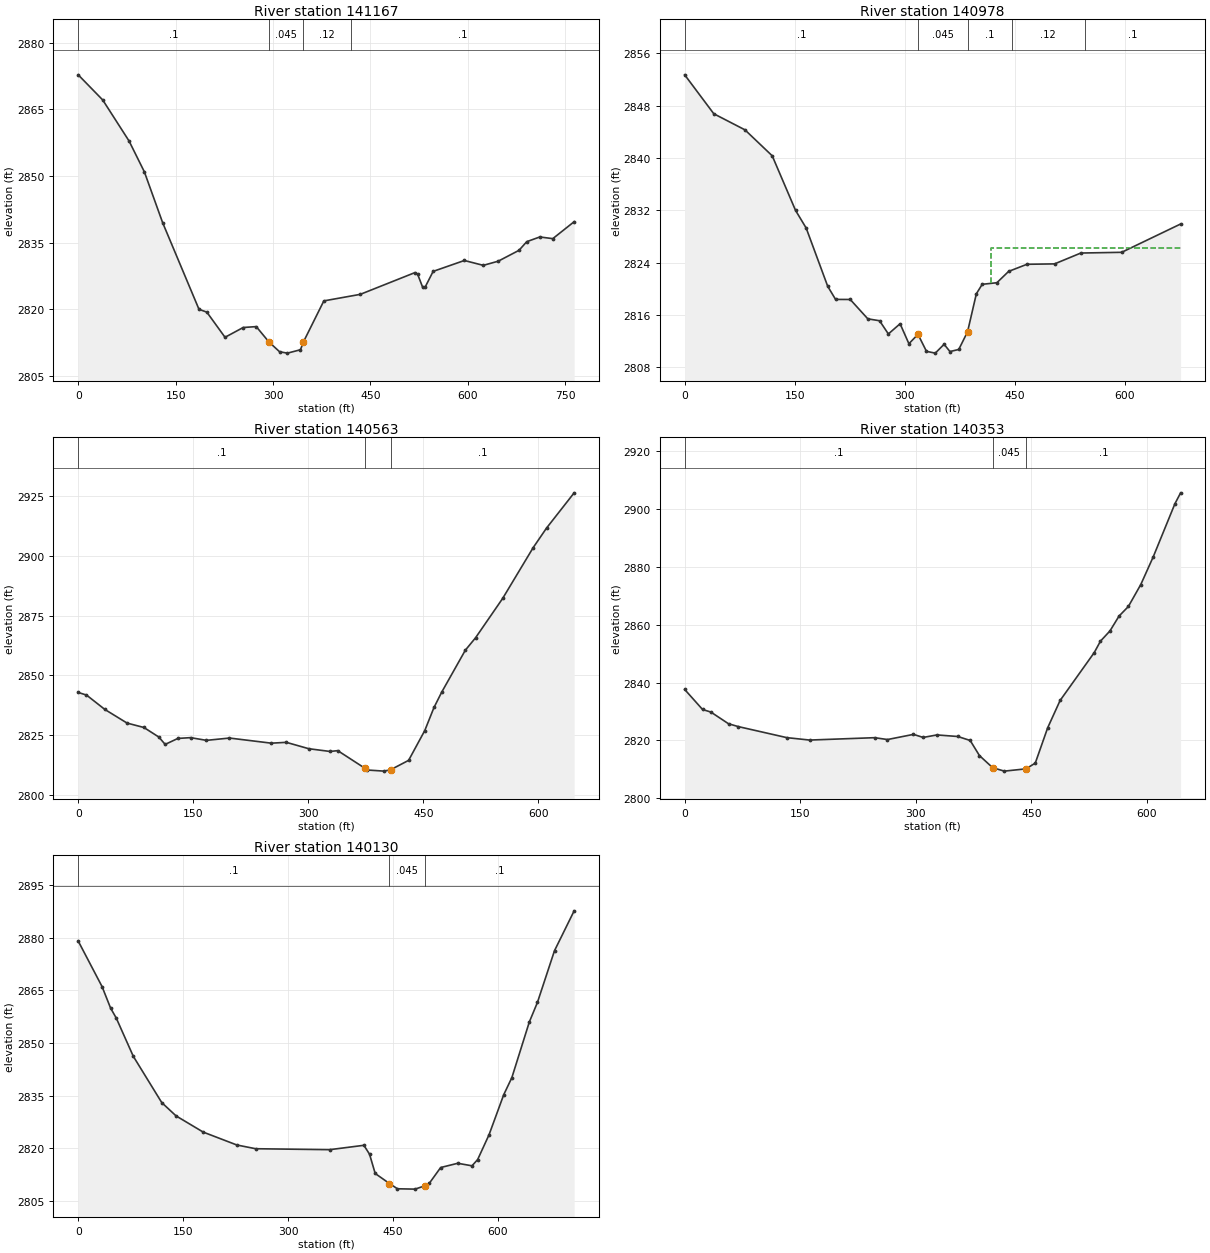
Type RM Length L Ch R = 1 ,141167  ,191.2,189.2,186.8
XS GIS Cut Line= 2
2338392.17910712665386.931906541     2338434.847      664624.319
#Sta/Elev= 30
       0 2872.74    37.8 2867.08    78.3 2857.87   101.9 2850.93     130 2839.52
     186 2820.04   198.1  2819.4   226.1 2813.75   254.1 2815.95   274.2 2816.15
   293.8 2812.69   310.2 2810.49   322.3 2810.19   342.3 2810.95   346.9 2812.72
   378.3 2821.93   434.4  2823.4   518.6 2828.29   522.6 2827.97   530.6 2824.95
   534.6 2825.11   546.6 2828.56   594.7 2831.01   623.9 2829.92   646.8 2830.85
   678.8 2833.29   690.8 2835.24   710.9  2836.3   730.9 2835.92   763.8 2839.73
#Mann= 4 ,-1,0
       0      .1       0   293.8    .045       0   346.9     .12       0
     420      .1       0
Bank Sta=293.8,346.9
XS Rating Curve= 0 ,0
Exp/Cntr=0.3,0.1

Type RM Length L Ch R = 1 ,140978  ,386.4,414.8,438.6
XS GIS Cut Line= 4
 2338482.2568926665359.7417730872338603.65152188665253.800810464
2338596.52383146 664969.156600242338527.29553608664749.274691499
#Sta/Elev= 30
       0 2852.69    39.7 2846.74    82.2 2844.28   119.4 2840.31   151.2 2831.97
   165.7 2829.27   195.1 2820.36   205.8 2818.36   225.8 2818.35   249.8 2815.39
   265.8  2815.1   277.8 2813.08   293.8 2814.64   305.8 2811.59   318.2 2813.02
   329.8 2810.42   341.8 2810.15   353.8  2811.5   361.8 2810.39   373.8 2810.71
   385.8 2813.41   397.8 2819.22   405.8 2820.67   425.8 2820.91   441.8 2822.64
   466.8 2823.73   504.5 2823.79   540.3 2825.45     596 2825.56   676.4 2829.89
#Mann= 5 ,-1,0
       0      .1       0   318.2    .045       0   385.8      .1       0
  445.85     .12       0  545.85      .1       0
#XS Ineff= 2 , 0
                          417.47         2826.21
Permanent Ineff=
       F       F
Bank Sta=318.2,385.8
XS Rating Curve= 0 ,0
Exp/Cntr(USF)=0,0
Exp/Cntr=0.3,0.1

Type RM Length L Ch R = 1 ,140563  ,197.2,210.5,215.5
XS GIS Cut Line= 3
 2338582.7380124665328.9847292552338843.75593555665257.940318462
2339184.76238785665098.867982134
#Sta/Elev= 30
       0 2842.87    10.8 2841.78    34.7 2835.76    63.7 2830.04    85.7 2828.19
   105.1  2824.2   113.4 2821.11     130 2823.61   146.6 2823.94   167.2  2822.8
   197.3 2823.77   251.9 2821.62   271.4 2821.97   300.7  2819.3   328.4 2818.15
   338.5 2818.49   373.7 2811.16   376.9 2810.38     399 2809.91   407.8 2810.55
   430.9 2814.42     452 2826.92     464 2836.57     474 2842.96   504.9 2860.58
   518.2 2865.77   553.5 2882.23   593.4 2903.56   610.8 2911.74   646.8  2926.5
#Mann= 3 ,-1,0
       0      .1       0   373.7    .045       0   407.8      .1       0
Bank Sta=373.7,407.8
XS Rating Curve= 0 ,0
Exp/Cntr=0.3,0.1

Type RM Length L Ch R = 1 ,140353  ,220.5,222.3,222.6
XS GIS Cut Line= 3
2338522.08607772665487.7775297132338827.98250417   665387.333927
2339147.57578553665423.858873441
#Sta/Elev= 30
       0  2837.6    23.2 2830.68      34 2829.79    56.9 2825.75    69.6 2824.77
   132.7 2820.95   162.2 2820.12   246.4 2820.94   263.2  2820.3   296.9 2822.08
   309.5 2821.03   327.4 2821.89   354.4 2821.35   370.5 2819.98   382.5 2814.77
   399.7 2810.57   414.8 2809.39     443 2810.18     455 2812.17   471.1 2824.37
   487.2 2833.79   531.5 2850.33   539.6 2854.29   551.9 2857.81   563.7 2862.95
   575.8 2866.25   591.9 2873.83     608 2883.36   636.2 2901.74   643.6 2905.51
#Mann= 3 ,-1,0
       0      .1       0   399.7    .045       0     443      .1       0
Bank Sta=399.7,443
XS Rating Curve= 0 ,0
Exp/Cntr(USF)=0,0
Exp/Cntr=0.3,0.1

Type RM Length L Ch R = 1 ,140130  ,196.9,198.6,201.1
XS GIS Cut Line= 2
2338394.67380719665522.0158766362339091.78087911665652.339396667
#Sta/Elev= 30
       0 2879.09    34.1  2866.1    46.3 2859.97    54.4 2857.13    78.8 2846.21
   119.5 2833.01   139.9 2829.23   178.8  2824.6   226.8 2820.93   253.8 2819.86
   359.6 2819.59   408.5 2820.84   416.6  2818.3   424.7  2812.8   445.1 2809.94
   456.5 2808.44   481.7 2808.34   496.1 2809.31   502.1 2810.01   518.3  2814.5
   542.7 2815.71   563.1 2814.99   571.2 2816.77   587.5 2823.85   608.5 2835.27
   620.1 2840.13   645.1 2856.01   656.7 2861.59   681.1 2876.34   709.2 2887.71
#Mann= 3 ,-1,0
       0      .1       0   445.1    .045       0   496.1      .1       0
Bank Sta=445.1,496.1
XS Rating Curve= 0 ,0
Exp/Cntr=0.3,0.1