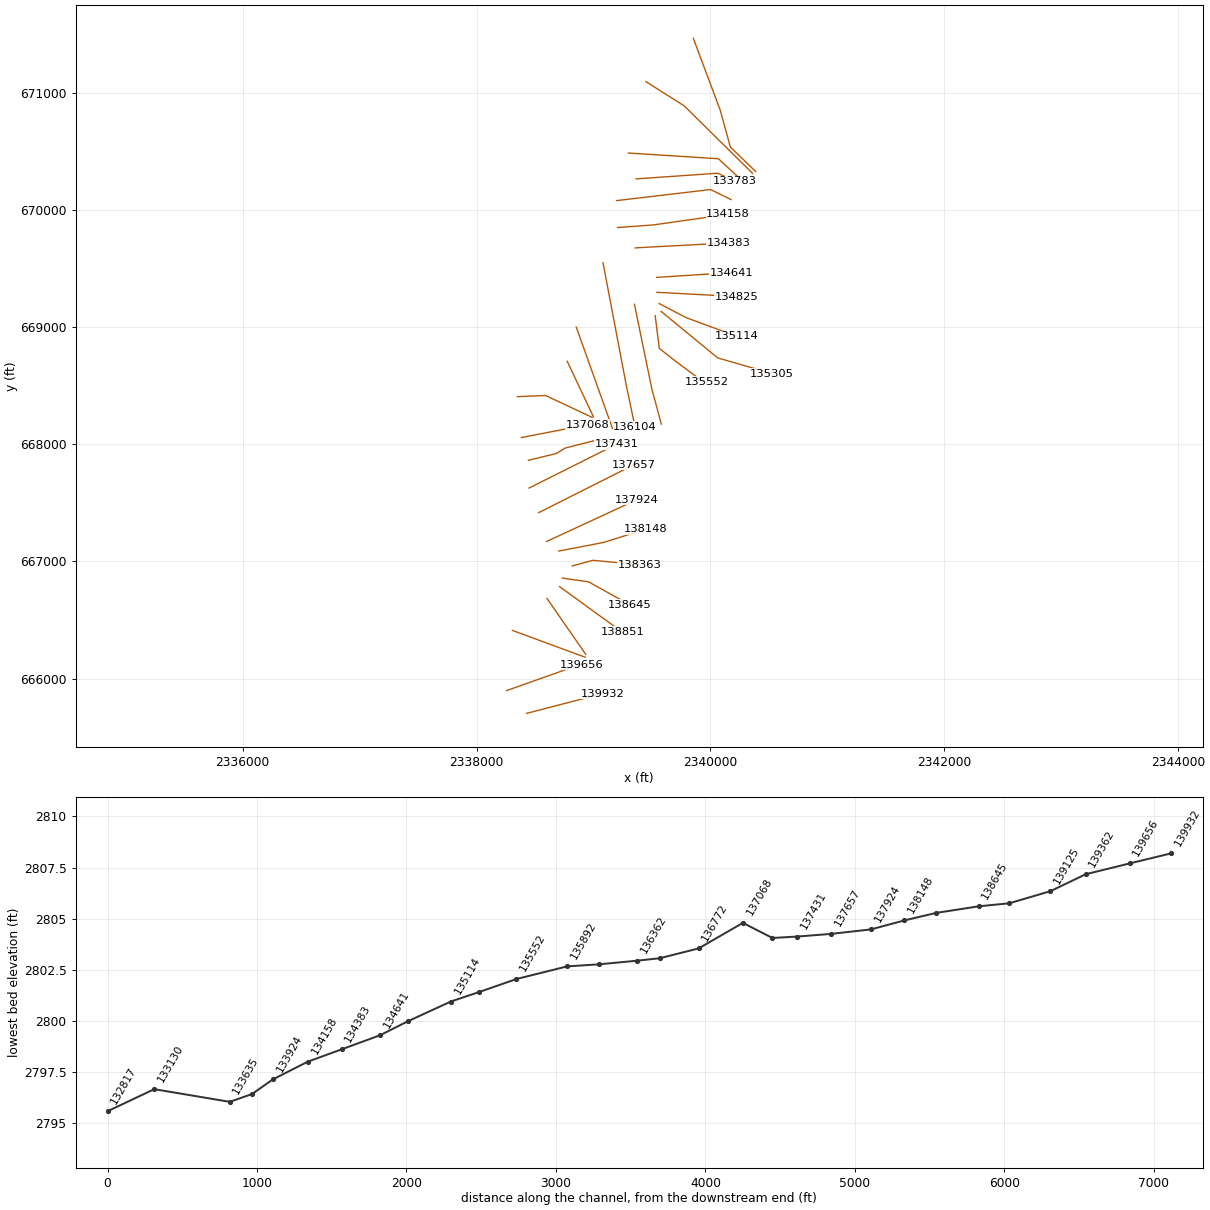
HEC-RAS study GLADYFK.prj: GLADYFK

--- GLADYFK.g01 (geometry) --- (continued)

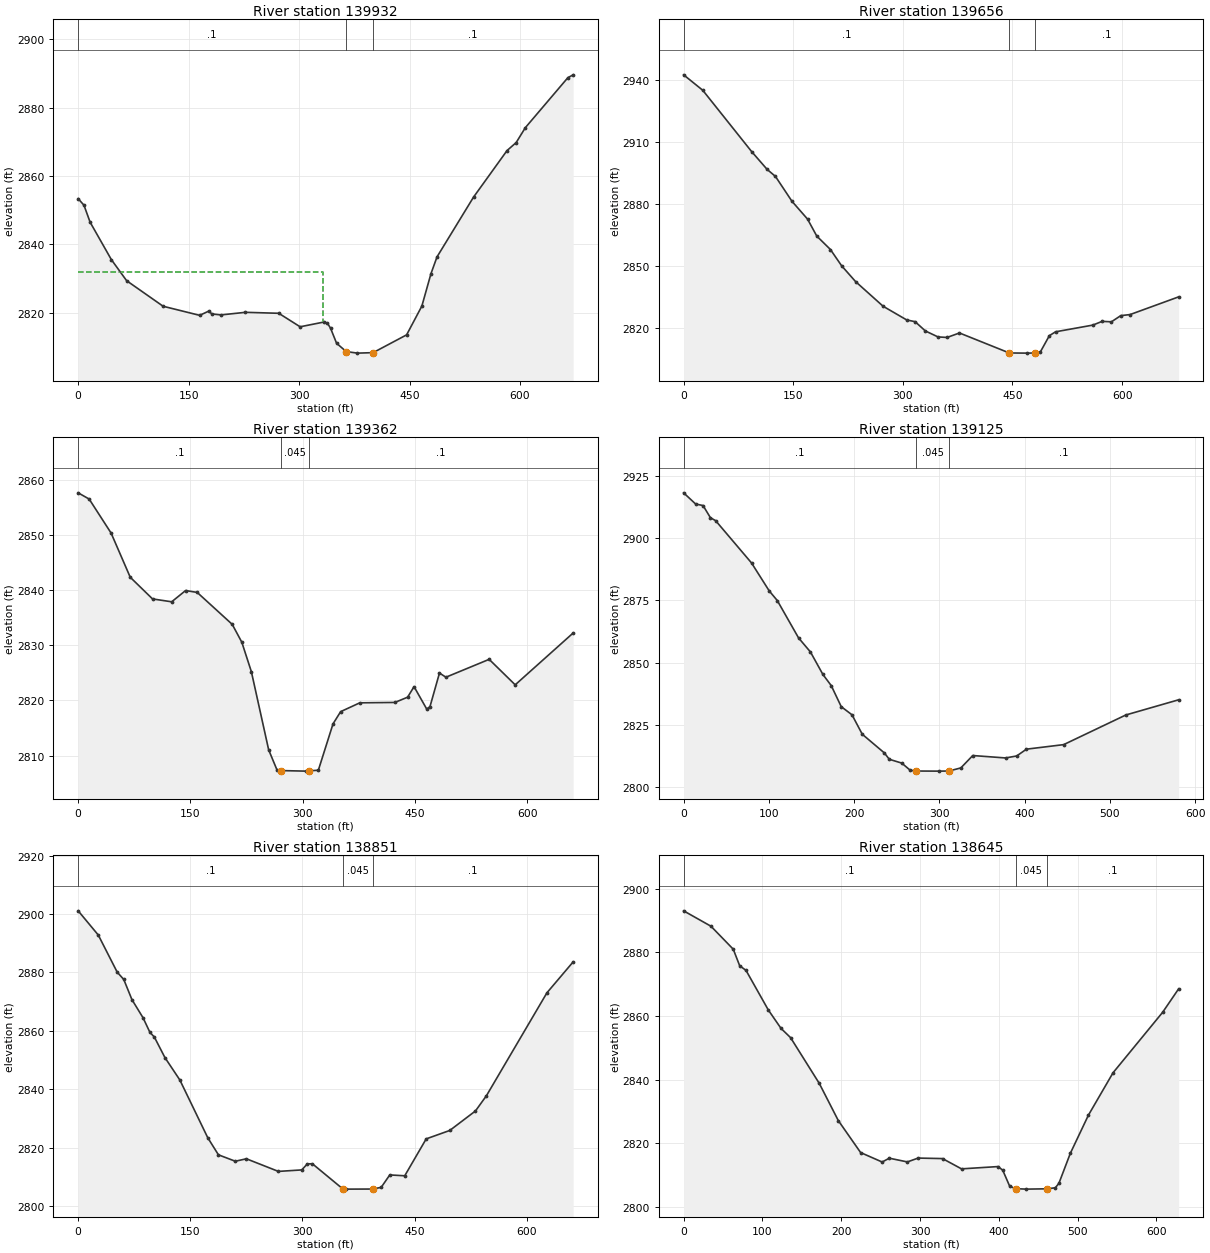
Type RM Length L Ch R = 1 ,139932  ,274.2,276,277.4
XS GIS Cut Line= 2
2338428.49090247665702.3615900542339079.09151095665871.289467345
#Sta/Elev= 30
       0 2853.36     7.9 2851.43    16.2 2846.48    45.1 2835.52    65.8 2829.37
   115.4 2821.89     165 2819.24   177.4 2820.48   181.5 2819.65   193.9 2819.36
     227 2820.12   272.4 2819.84   301.4 2815.89   334.4 2817.31   338.5 2816.92
   342.7 2815.49   350.9 2811.08     364 2808.64   379.3 2808.19   400.5 2808.33
     446 2813.53   466.7 2821.94   479.1 2831.43   487.3 2836.33   536.9 2853.81
   582.4 2867.42   594.8 2869.76   607.2  2874.1     665 2888.73   672.2 2889.56
#Mann= 3 ,-1,0
       0      .1       0     364    .045       0   400.5      .1       0
#XS Ineff= 2 , 0
          332.79 2832.04
Permanent Ineff=
       F       F
Bank Sta=364,400.5
XS Rating Curve= 0 ,0
Exp/Cntr(USF)=0,0
Exp/Cntr=0.3,0.1

Type RM Length L Ch R = 1 ,139656  ,302.9,294,277.2
XS GIS Cut Line= 3
2338256.44191646665896.4263598852338840.93071977666103.806807189
2338895.99030597666119.401359885
#Sta/Elev= 30
       0 2942.61    26.2 2935.12    93.1 2905.39   114.3 2896.76   125.7 2893.35
   148.3 2881.29   169.6 2872.67   182.2 2864.45   200.9 2857.93   216.2 2850.05
   235.3 2842.39   272.9 2830.45   305.3 2823.78   316.8 2822.95   330.8 2818.45
   348.1 2815.56   360.5  2815.3   377.5 2817.47   445.7 2807.78   470.3  2807.7
   480.7 2807.76   487.8 2808.05   500.5 2816.17     509 2818.04     560 2821.29
   572.7  2823.1   585.4 2822.88   598.2 2825.88   610.9 2826.39   677.4 2834.97
#Mann= 3 ,-1,0
       0      .1       0   445.7    .045       0   480.7      .1       0
Bank Sta=445.7,480.7
XS Rating Curve= 0 ,0
Exp/Cntr=0.3,0.1

Type RM Length L Ch R = 1 ,139362  ,246.6,237,223.7
XS GIS Cut Line= 2
2338306.89237738666410.7226692162338927.81646688666182.441753959
#Sta/Elev= 30
       0 2857.61    14.7 2856.48      44 2850.32    69.6 2842.31    99.4 2838.38
     125 2837.86   143.6  2839.9   159.1 2839.56   205.9 2833.77   218.7 2830.54
   231.5 2825.19   254.6 2811.03   265.6 2807.43   271.1 2807.27     304 2807.17
   308.2 2807.22     321 2807.33   340.6 2815.73   350.8 2817.95   376.4 2819.55
   423.3 2819.62   440.3 2820.57   448.9 2822.48   465.9 2818.41   470.2 2818.86
   482.9 2824.95   491.5 2824.19   549.3 2827.43   584.1 2822.81   661.6 2832.21
#Mann= 3 ,-1,0
       0      .1       0   271.1    .045       0   308.2      .1       0
Bank Sta=271.1,308.2
XS Rating Curve= 0 ,0
Exp/Cntr(USF)=0,0
Exp/Cntr=0.3,0.1

Type RM Length L Ch R = 1 ,139125  ,266.6,273.7,279.5
XS GIS Cut Line= 2
2338602.76218955666683.4334929312338933.81782459666206.370516655
#Sta/Elev= 30
       0 2918.23    14.1 2913.73    22.8 2913.12    31.4 2908.25    37.6 2907.02
    79.7 2890.02   100.4 2878.81   109.9 2874.92   134.8 2859.92   148.8 2854.24
   163.4  2845.2   173.2 2840.71   184.9 2832.26   197.5 2828.99   209.6 2821.16
   235.4 2813.68   241.3  2811.1   255.9 2809.57   265.7 2806.72   272.8 2806.38
   299.7 2806.34   311.2 2806.38   325.2 2807.63   339.2 2812.61   377.6 2811.64
   390.7 2812.43   402.2 2815.17   445.8 2816.99   518.8 2828.92   580.7 2835.02
#Mann= 3 ,-1,0
       0      .1       0   272.8    .045       0   311.2      .1       0
Bank Sta=272.8,311.2
XS Rating Curve= 0 ,0
Exp/Cntr=0.3,0.1

Type RM Length L Ch R = 1 ,138851  ,203.9,206.1,208.3
XS GIS Cut Line= 2
 2338709.9020312666784.9294021572339246.13390113666396.623565305
#Sta/Elev= 30
       0 2901.06    26.9 2892.77    52.2 2880.06      61 2877.55    71.9 2870.66
    86.8 2864.42      96 2859.43   101.9 2857.83     116 2850.82     136 2843.13
   173.3 2823.37   187.6  2817.5   210.2  2815.3     225 2816.14   267.8 2811.82
   299.1 2812.33   306.5  2814.4   313.3 2814.43   354.2 2805.78   358.4 2805.75
   393.9 2805.78   405.3 2806.36   416.8 2810.61   436.8 2810.32   465.5 2822.96
     497 2825.84   531.4 2832.52   546.1 2837.75     627 2872.99   662.1 2883.59
#Mann= 3 ,-1,0
       0      .1       0   354.2    .045       0   393.9      .1       0
Bank Sta=354.2,393.9
XS Rating Curve= 0 ,0
Exp/Cntr(USF)=0,0
Exp/Cntr=0.3,0.1

Type RM Length L Ch R = 1 ,138645  ,274,282.3,289.5
XS GIS Cut Line= 3
2338733.78732315666857.6319508872338957.93991817666825.744479144
2339308.86794322 666630.37022873
#Sta/Elev= 30
       0 2893.06    34.7 2888.22      63 2880.99    71.1 2875.82    79.2 2874.33
   107.5 2861.89   123.6 2856.11   135.7 2853.21   172.1 2838.84   196.3 2827.13
   224.6 2817.09   251.9 2814.12     261 2815.32   283.9 2814.15   297.6 2815.36
   328.5  2815.2   352.6 2811.97     399 2812.69   404.9 2811.55   413.7 2806.53
   421.2 2805.74     435  2805.6   460.8  2805.7   471.6 2806.02   476.2 2807.43
   490.7 2816.87   513.7 2828.88   544.9 2842.18   607.8 2861.17   628.1 2868.55
#Mann= 3 ,-1,0
       0      .1       0   421.2    .045       0   460.8      .1       0
Bank Sta=421.2,460.8
XS Rating Curve= 0 ,0
Exp/Cntr=0.3,0.1

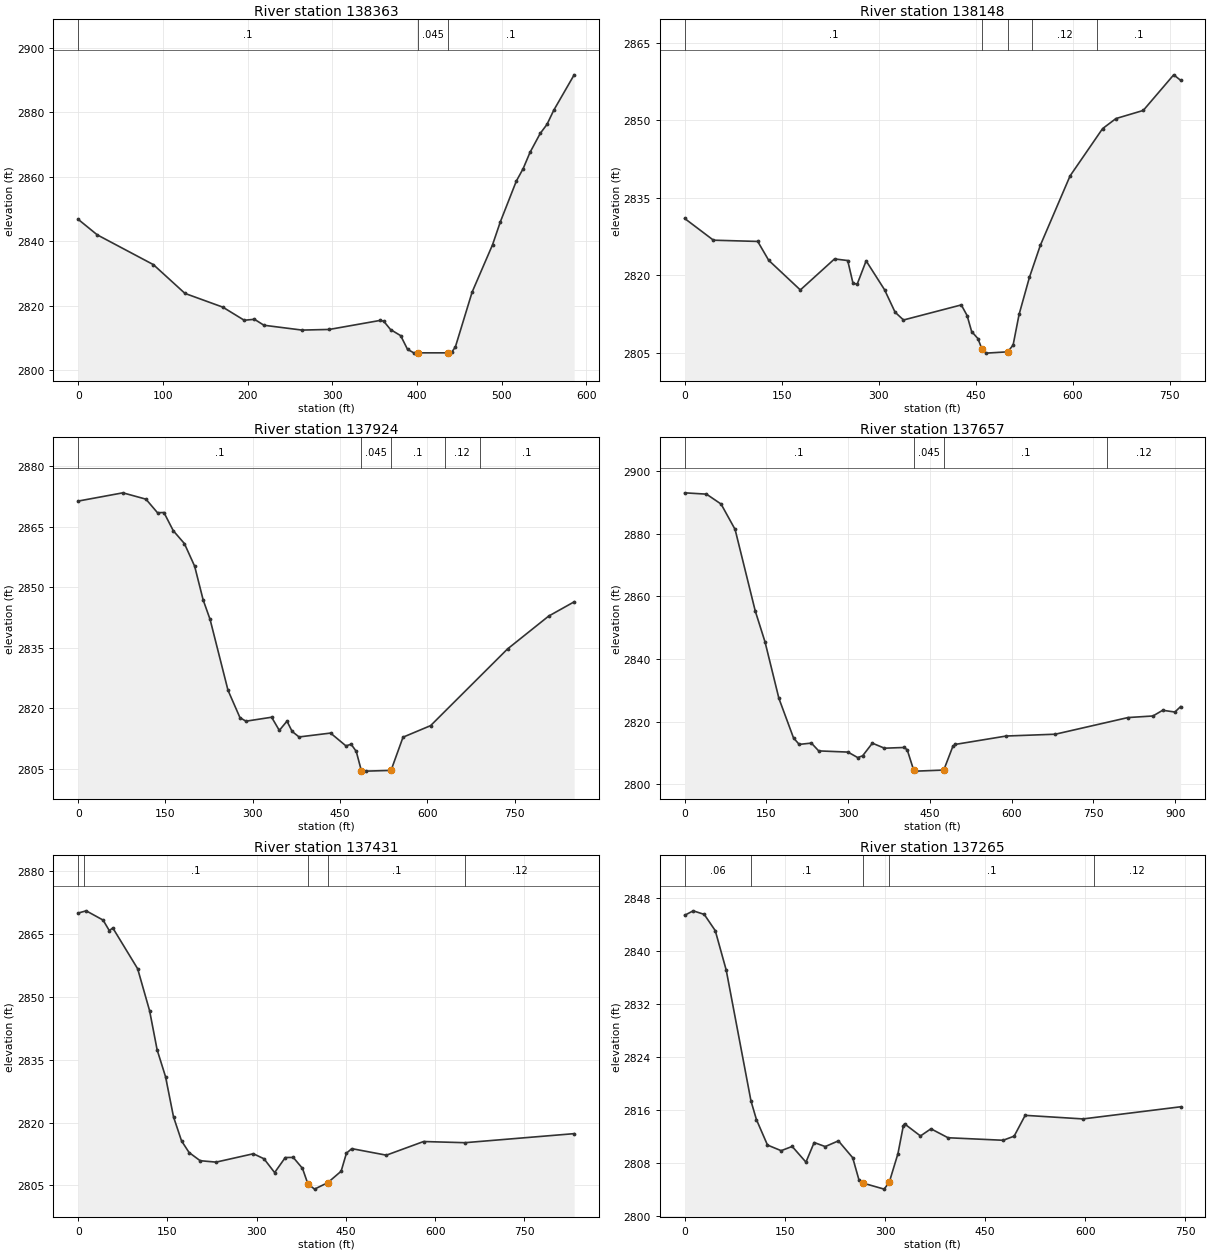
Type RM Length L Ch R = 1 ,138363  ,206.1,214.3,220.1
XS GIS Cut Line= 3
2338818.46131982666961.3817617332338995.50084603 667009.33232213
2339396.11446246666971.891471752
#Sta/Elev= 30
       0 2846.79    22.5 2841.98    88.8 2832.74   126.1 2823.81   170.8 2819.55
   196.1 2815.48   208.2 2815.78   219.4 2813.93   264.4 2812.43   296.6 2812.63
   356.9 2815.44   360.9 2815.17   368.9  2812.6   380.9  2810.7     389 2806.45
     397 2805.28     401 2805.37   436.6 2805.37   441.2 2805.58   445.5  2807.2
   465.3 2824.23   489.4 2838.91   498.6 2846.01   517.5 2858.67   525.6 2862.55
   533.6 2867.54   545.7 2873.45   553.7 2876.25   561.7 2880.65   585.8 2891.64
#Mann= 3 ,-1,0
       0      .1       0     401    .045       0   436.6      .1       0
Bank Sta=401,436.6
XS Rating Curve= 0 ,0
Exp/Cntr(USF)=0,0
Exp/Cntr=0.3,0.1

Type RM Length L Ch R = 1 ,138148  ,222.4,224.1,226.5
XS GIS Cut Line= 3
     2338704.509      667088.6082339085.37522932667161.685170451
2339447.27627966667275.417535586
#Sta/Elev= 30
       0    2831    44.5 2826.79     113 2826.55     130 2822.89   178.9 2817.15
   231.8 2823.16   252.2 2822.85   260.3 2818.49   266.8 2818.25   280.7 2822.79
   309.2 2817.19   325.5 2812.84   338.5 2811.33   427.9 2814.25   436.9 2812.19
   443.9  2809.1   453.6 2807.73   460.1 2805.63   466.2 2804.91   499.8 2805.16
   508.1 2806.49   517.3  2812.4   533.3 2819.59   550.1 2825.77   596.2 2839.25
   646.5 2848.41   667.2 2850.36   709.4 2851.93   756.5 2858.83   767.2 2857.77
#Mann= 5 ,-1,0
       0      .1       0   460.1    .045       0   499.8      .1       0
  537.81     .12       0  637.81      .1       0
Bank Sta=460.1,499.8
XS Rating Curve= 0 ,0
Exp/Cntr=0.3,0.1

Type RM Length L Ch R = 1 ,137924  ,266.6,267.3,268
XS GIS Cut Line= 2
2338598.50005366 667169.913333452339372.11871092667527.553434019
#Sta/Elev= 30
       0 2871.31    76.8 2873.35   116.4 2871.78   136.3 2868.42   147.3 2868.48
   163.4 2863.97   182.5 2860.79   200.1 2855.19   214.7 2846.85   226.6 2842.03
   257.4 2824.49     278  2817.7   288.3 2816.83   332.4 2817.81   345.6 2814.55
   358.8 2816.84   367.6  2814.3   379.5 2812.93   433.7 2813.89   460.1 2810.72
     469 2811.13   477.8 2809.36   486.6 2804.58   494.9 2804.47   537.6 2804.65
   558.2 2812.87   605.6 2815.73   737.8 2834.71   808.5 2842.84   852.3 2846.37
#Mann= 5 ,-1,0
       0      .1       0   486.6    .045       0   537.6      .1       0
     630     .12       0     690      .1       0
Bank Sta=486.6,537.6
XS Rating Curve= 0 ,0
Exp/Cntr(USF)=0,0
Exp/Cntr=0.3,0.1

Type RM Length L Ch R = 1 ,137657  ,224.9,225.8,227.9
XS GIS Cut Line= 3
     2338532.471      667416.751     2338939.009      667621.084
     2339345.548      667825.416
#Sta/Elev= 30
       0 2892.97      40 2892.55    66.8 2889.39    92.5  2881.3   129.5  2855.3
   147.4 2845.46   172.9 2827.44   199.7 2814.84   210.1 2812.77   232.5 2813.19
   245.9  2810.7   299.6 2810.32   317.5 2808.57   326.5 2809.13   344.4 2813.16
   366.6 2811.56   402.6 2811.79   408.3 2811.07   420.2 2804.55     425 2804.25
   475.4 2804.59   492.1 2812.16   496.6 2812.77     590 2815.44   680.1 2816.02
   813.5 2821.33   859.2 2821.83   877.1 2823.65   899.5 2823.09     910 2824.83
#Mann= 4 ,-1,0
       0      .1       0   420.2    .045       0   475.4      .1       0
     775     .12       0
Bank Sta=420.2,475.4
XS Rating Curve= 0 ,0
Exp/Cntr=0.3,0.1

Type RM Length L Ch R = 1 ,137431  ,163.4,166.2,166.1
XS GIS Cut Line= 2
2338448.84923144667626.4751639642339194.56688794667999.333992217
#Sta/Elev= 30
       0 2870.06    13.4 2870.59    41.8 2868.38    52.2 2865.88    58.2 2866.49
    99.9 2856.76     120 2846.73   132.7 2837.37   146.8 2830.97   160.2 2821.38
   173.7 2815.64   186.4 2812.86     205 2810.91   231.8 2810.57   294.4 2812.57
   312.3 2811.37   330.2 2808.07   348.1 2811.67   361.5 2811.69     377 2809.08
     386  2805.4   397.3 2804.12   419.6 2805.67     442  2808.4   450.9 2812.71
   459.9 2813.79     518 2812.23   580.6 2815.49     650 2815.21   833.7 2817.37
#Mann= 5 ,-1,0
       0     .06       0      10      .1       0     386    .045       0
   419.6      .1       0     650     .12       0
Bank Sta=386,419.6
XS Rating Curve= 0 ,0
Exp/Cntr(USF)=0,0
Exp/Cntr=0.3,0.1

Type RM Length L Ch R = 1 ,137265  ,203.8,197.3,193
XS GIS Cut Line= 5
2338443.71253332667863.6047001512338682.82415452667921.638250125
 2338758.4487204667968.1081682032339028.03974806668036.263203284
2339156.37102689 668016.66187638
#Sta/Elev= 30
       0 2845.36    12.8 2846.03    29.3 2845.49    45.8 2843.04    62.2 2837.09
    99.3 2817.34   107.5 2814.53     124  2810.7   144.5 2809.85     161 2810.49
   181.6 2808.12   193.9 2811.08   210.5 2810.47   230.2 2811.33   251.6 2808.79
   261.2 2805.37   266.4 2804.98   298.7 2804.05   306.3 2805.07   319.4 2809.41
   327.5 2813.64   329.2  2813.9   353.1 2812.07   368.8 2813.15   394.4  2811.8
   476.9 2811.42   493.4 2812.04   509.9 2815.18   596.5 2814.64   742.7 2816.47
#Mann= 5 ,-1,0
       0     .06       0     100      .1       0   266.4    .045       0
   306.3      .1       0  612.89     .12       0
Bank Sta=266.4,306.3
XS Rating Curve= 0 ,0
Exp/Cntr=0.3,0.1

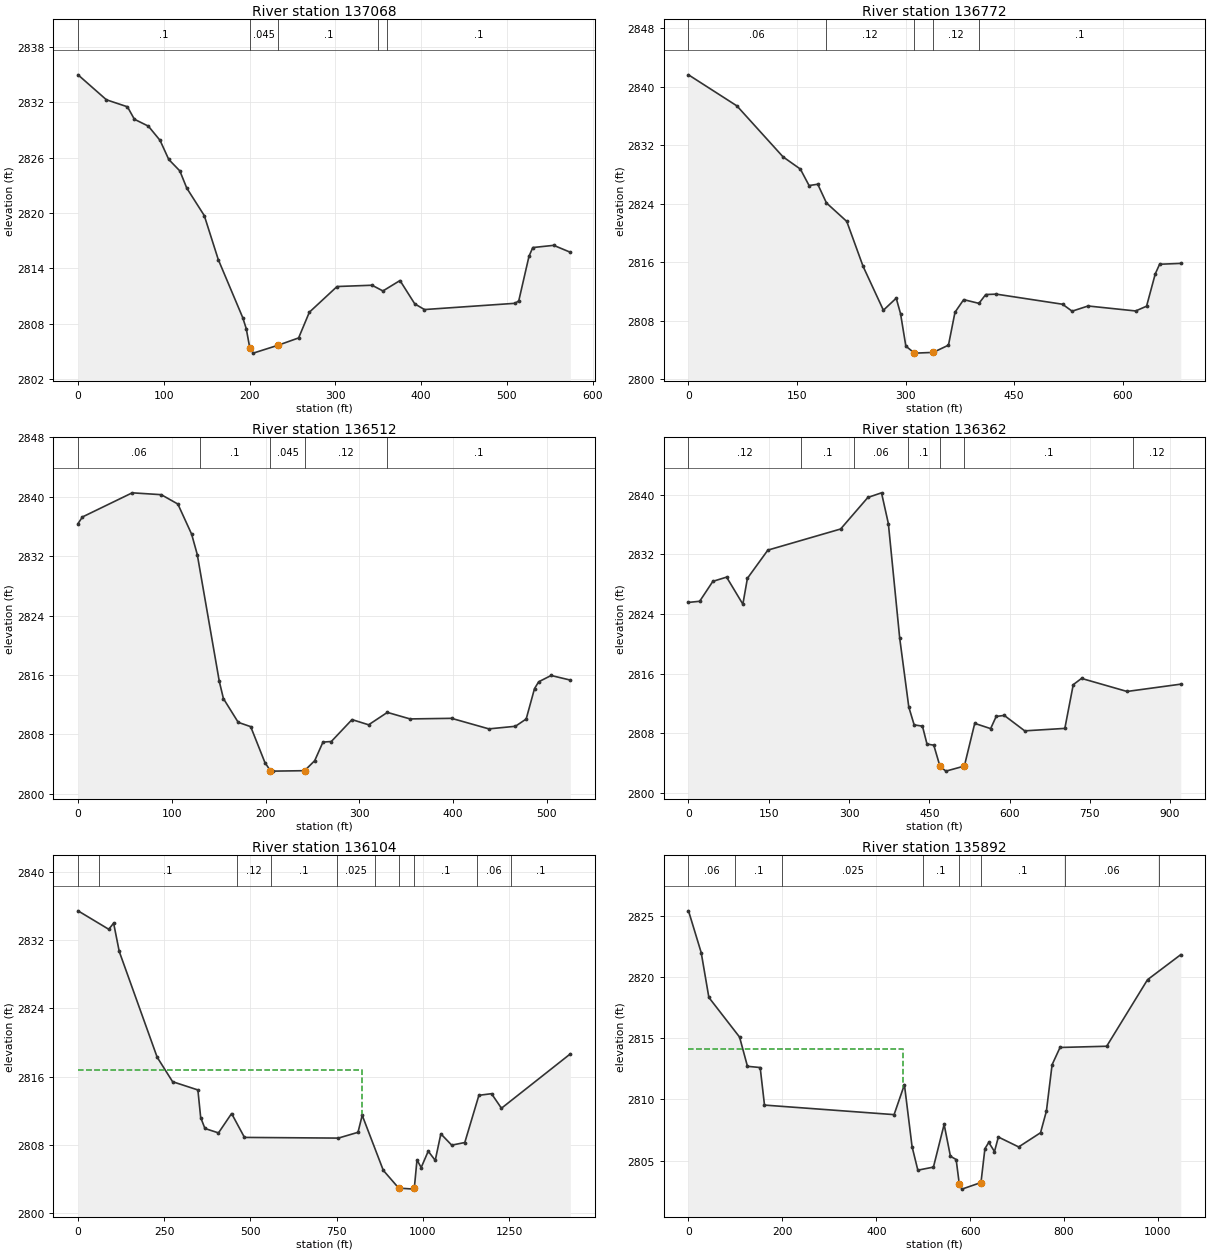
Type RM Length L Ch R = 1 ,137068  ,307.5,295.9,288.3
XS GIS Cut Line= 2
2338383.63065242 668057.711432882338947.16256272 668166.63025024
#Sta/Elev= 30
       0    2835    33.1 2832.29    57.6 2831.53    65.7 2830.18      82 2829.43
    95.6 2827.89   105.8 2825.81   118.7 2824.57   126.8  2822.7   147.2 2819.72
   163.5 2814.95     192 2808.65   196.1 2807.46   200.2 2805.39   204.3 2804.79
   233.7 2805.66   257.2 2806.44   269.7 2809.23     302 2812.02   342.8 2812.16
   355.5 2811.54   375.4 2812.67   392.6 2810.14   403.9 2809.52   509.8  2810.2
   513.9 2810.48   525.8  2815.3   530.2 2816.25   554.6 2816.49     574 2815.74
#Mann= 5 ,-1,0
       0      .1       0   200.2    .045       0   233.7      .1       0
     350     .12       0     360      .1       0
Bank Sta=200.2,233.7
XS Rating Curve= 0 ,0
Exp/Cntr(USF)=0,0
Exp/Cntr=0.3,0.1

Type RM Length L Ch R = 1 ,136772  ,271.1,259.9,252.9
XS GIS Cut Line= 3
2338349.70139518668406.8362167652338590.74411644 668416.62916029
2338988.16693529668230.155806292
#Sta/Elev= 30
       0 2841.62    66.9 2837.37   130.6  2830.4   154.6 2828.72   166.6 2826.47
   178.6 2826.65   190.6 2824.09   218.7 2821.56   241.2 2815.42   269.3 2809.41
     287 2811.06     293 2808.93   300.3  2804.5     312 2803.56   313.5 2803.54
   338.1 2803.64   359.2 2804.63   368.2 2809.13   380.2 2810.86   401.3 2810.35
   410.7 2811.56   425.4 2811.61   516.8 2810.23     530 2809.28   552.1 2809.99
   617.8 2809.31   632.9 2809.96   644.9 2814.38   650.9  2815.7   680.2 2815.82
#Mann= 5 ,-1,0
       0     .06       0     190     .12       0     312    .045       0
   338.1     .12       0  401.24      .1       0
Bank Sta=312,338.1
XS Rating Curve= 0 ,0
Exp/Cntr=0.3,0.1

Type RM Length L Ch R = 1 ,136512  ,152.3,150,150.2
XS GIS Cut Line= 2
2338775.10370062668709.4217685332338999.60638618668234.653794159
#Sta/Elev= 30
       0  2836.4     4.7 2837.29    57.8 2840.54    88.8 2840.29   106.5 2839.03
   121.2 2834.97   127.2 2832.23   150.7 2815.15   155.1 2812.83   170.9 2809.63
   184.2 2809.05   199.4 2804.21   205.3  2803.1   208.2 2803.06   241.7 2803.12
   252.5 2804.47   261.3 2806.97   270.2 2807.05   292.3    2810     310  2809.3
     330 2810.97   354.2 2810.09   398.5 2810.17   438.3 2808.75   466.6  2809.1
   478.1 2810.08     487 2814.18   491.4 2815.09   504.7 2815.94   525.2 2815.32
#Mann= 5 ,-1,0
       0     .06       0     130      .1       0   205.3    .045       0
   241.7     .12       0     330      .1       0
Bank Sta=205.3,241.7
XS Rating Curve= 0 ,0
Exp/Cntr(USF)=0,0
Exp/Cntr=0.3,0.1

Type RM Length L Ch R = 1 ,136362  ,260.4,258.2,253.2
XS GIS Cut Line= 2
2338852.87344018669000.867200076 2339162.5366235668134.506159092
#Sta/Elev= 30
       0 2825.56    20.9 2825.71    45.5 2828.38    71.2 2828.95   101.6 2825.32
   110.1 2828.79   148.3 2832.57   284.3  2835.4   335.2 2839.63   360.7 2840.25
   373.5 2836.13   394.7 2820.76   411.7 2811.53   421.7 2809.14   437.2 2808.97
   445.7 2806.57   458.4 2806.42     470 2803.57   481.1 2802.94   515.5 2803.62
   534.9 2809.34   564.6 2808.64     575 2810.27   590.1 2810.41   628.3 2808.34
   703.3 2808.67     719 2814.53   734.5 2815.37   819.5 2813.62     920  2814.6
#Mann= 7 ,-1,0
       0     .12       0     210      .1       0     310     .06       0
     410      .1       0     470    .045       0   515.5      .1       0
     830     .12       0
Bank Sta=470,515.5
XS Rating Curve= 0 ,0
Exp/Cntr(USF)=0,0
Exp/Cntr=0.3,0.1

Type RM Length L Ch R = 1 ,136104  ,211.8,211.9,212.7
XS GIS Cut Line= 3
 2339081.4251666669550.5638775362339280.50906144668503.662877111
 2339355.0974932668149.806565809
#Sta/Elev= 30
       0 2835.48    89.1 2833.31   103.2 2834.03   119.5  2830.7   229.4 2818.27
   274.2 2815.39   347.5 2814.42   355.6 2811.18   367.9 2809.89   407.2 2809.37
   445.2 2811.65   482.5 2808.84   754.7 2808.76   811.7 2809.44   823.9 2811.44
     885 2804.97   929.8 2802.88   974.5 2802.76   975.1 2802.93   982.7 2806.19
   994.9  2805.3  1015.3 2807.22  1035.6 2806.14  1051.9 2809.26  1083.4 2807.93
  1121.3 2808.24  1162.2 2813.79  1198.8 2813.98  1227.6 2812.27  1427.3 2818.66
#Mann= 10 ,-1,0
       0     .06       0      60      .1       0     460     .12       0
     560      .1       0     750    .025       0     860      .1       0
   929.8    .045       0   975.1      .1       0 1155.66     .06       0
 1255.66      .1       0
#XS Ineff= 2 , 0
          823.06 2816.78
Permanent Ineff=
       T       F
Bank Sta=929.8,975.1
XS Rating Curve= 0 ,0
Exp/Cntr=0.3,0.1

Type RM Length L Ch R = 1 ,135892  ,332,340.1,353.9
XS GIS Cut Line= 3
2339350.42215046669195.7114502572339500.03469971668468.524873688
2339580.06001675668172.779136806
#Sta/Elev= 30
       0 2825.41    27.1 2821.99    43.4 2818.33   108.8 2815.09   125.6  2812.7
   152.7  2812.6   161.9 2809.53     438 2808.75     460  2811.2   476.3 2806.13
   488.6 2804.21   521.8 2804.46   544.6 2807.95     558 2805.35   570.2 2805.08
   576.9 2803.08   582.5 2802.66   623.1  2803.2   631.5 2805.97   639.7 2806.48
   651.9 2805.73   660.1 2806.92   703.4 2806.11     750 2807.27   762.5 2809.04
   774.6 2812.83   791.5 2814.24   890.9 2814.34   977.9 2819.78  1048.8 2821.83
#Mann= 8 ,-1,0
       0     .06       0     100      .1       0     200    .025       0
     500      .1       0   576.9    .045       0   623.1      .1       0
  802.42     .06       0 1002.42      .1       0
#XS Ineff= 2 , 0
          457.89 2814.13
Permanent Ineff=
       T       F
Bank Sta=576.9,623.1
XS Rating Curve= 0 ,0
Exp/Cntr(USF)=0,0
Exp/Cntr=0.3,0.1

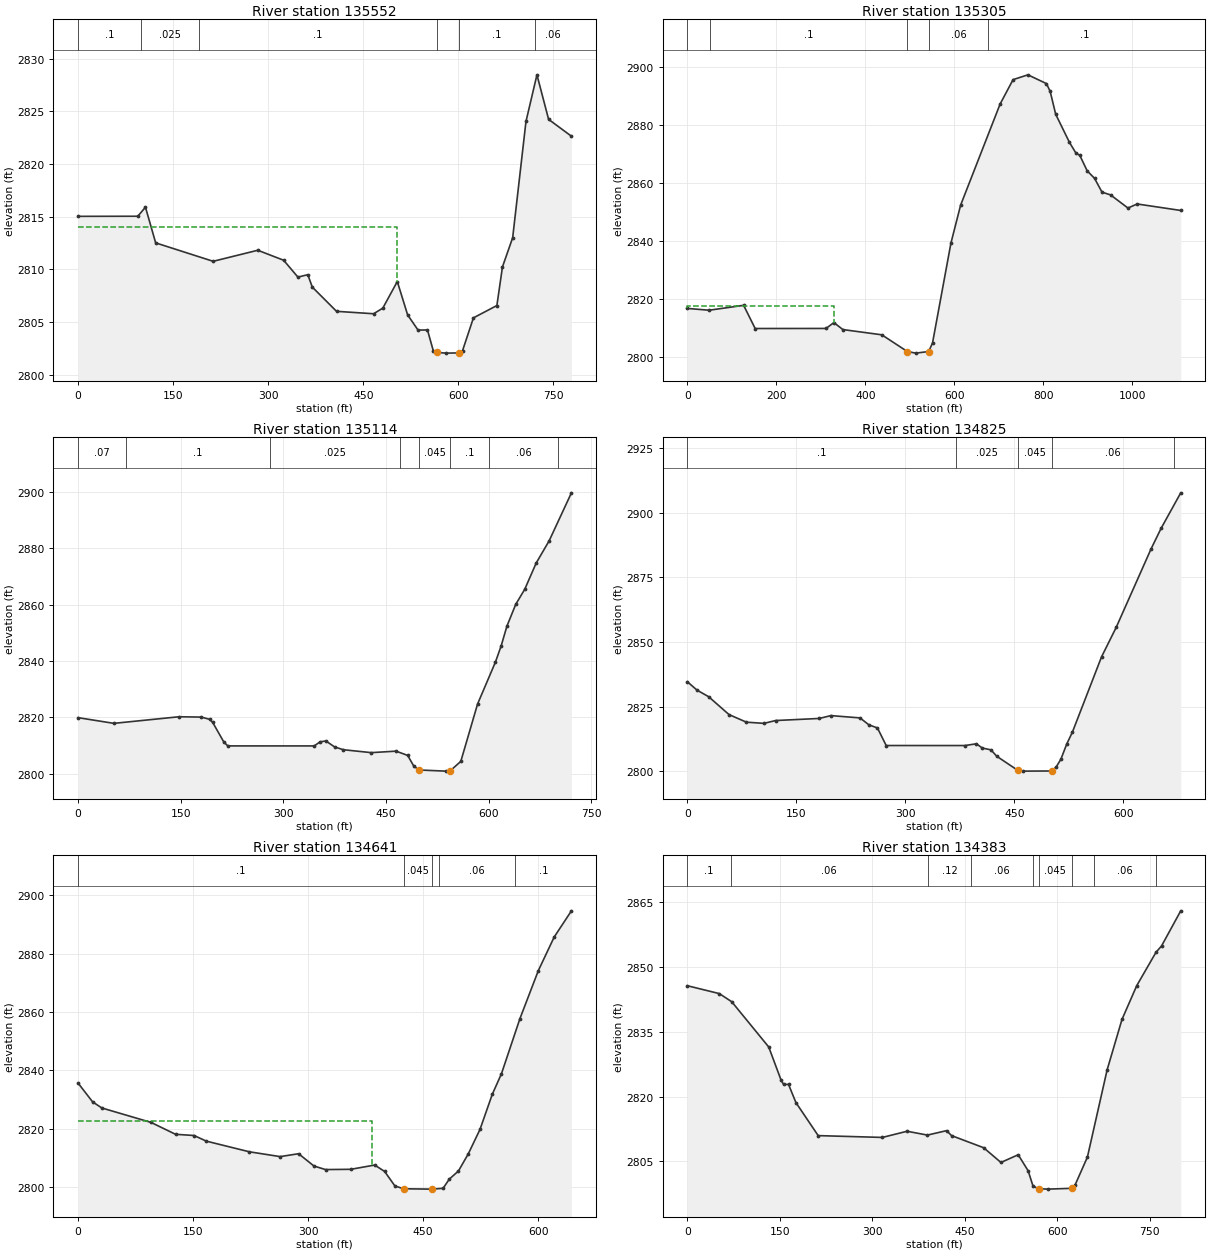
Type RM Length L Ch R = 1 ,135552  ,246.6,246.5,246.4
XS GIS Cut Line= 5
2339527.53730154 669098.628238692339562.84455064668819.002192958
2339703.64733593 668708.262106222339914.01570392668552.485053686
2339965.51673151668531.674517678
#Sta/Elev= 30
       0 2815.03    94.2 2815.04   106.3  2815.9   122.4 2812.51   213.1 2810.76
   283.5 2811.81   324.3 2810.86   346.8 2809.26   362.4 2809.49   369.5 2808.31
   407.7 2806.01   466.2 2805.78   480.7 2806.31   503.6 2808.84   519.9 2805.67
   536.3 2804.23   551.2 2804.24   560.3 2802.28   566.2  2802.1   580.4 2802.04
   600.8 2802.06   606.5 2802.27   623.7 2805.39   660.7 2806.56   669.5 2810.23
   685.6    2813   706.6 2824.04   723.9 2828.47   742.3 2824.24   778.3 2822.64
#Mann= 6 ,-1,0
       0      .1       0     100    .025       0     190      .1       0
   566.2    .045       0   600.8      .1       0  720.98     .06       0
#XS Ineff= 2 , 0
          502.88 2813.98
Permanent Ineff=
       T       F
Bank Sta=566.2,600.8
XS Rating Curve= 0 ,0
Exp/Cntr=0.3,0.1

Type RM Length L Ch R = 1 ,135305  ,186.5,191.6,202.4
XS GIS Cut Line= 3
2339578.46210397669134.9157866732340062.12496543668737.744732125
2340526.30510647668603.866914356
#Sta/Elev= 30
       0 2816.79    48.8 2816.17   126.4 2817.86   152.3 2809.88   311.6  2809.9
   329.3 2811.92   349.4 2809.52     437 2807.71   494.4 2801.96   513.3 2801.41
   542.4 2801.96     551 2804.92   592.3 2839.24   614.1 2852.32   702.9 2887.13
     732 2895.51   765.4 2897.17     807 2894.15   815.4 2891.48   827.8 2883.61
   858.8 2873.91   873.5 2870.19   881.9 2869.49   898.6 2864.13   915.2 2861.54
   931.9  2856.8   951.1 2855.86   990.2 2851.34    1011 2852.73  1108.9  2850.5
#Mann= 5 ,-1,0
       0     .07       0      50      .1       0   494.4    .045       0
   542.4     .06       0  675.84      .1       0
#XS Ineff= 2 , 0
             329 2817.71
Permanent Ineff=
       T       F
Bank Sta=494.4,542.4
XS Rating Curve= 0 ,0
Exp/Cntr(USF)=0,0
Exp/Cntr=0.3,0.1

Type RM Length L Ch R = 1 ,135114  ,280.6,288.4,293.7
XS GIS Cut Line= 3
 2339561.7737018669201.7021272472339793.26166585669081.331741624
2340224.53336765668921.845188928
#Sta/Elev= 30
       0 2819.91    52.3 2817.89   147.5 2820.23   180.1 2820.11   192.1 2819.32
   196.6 2818.24   212.8 2811.31   218.7 2809.89     345 2809.88   353.6 2811.35
   362.1 2811.63   374.9  2809.5   387.7 2808.53   428.3  2807.5   464.5 2808.03
   481.5 2806.51   490.6 2802.64   498.6 2801.34     537 2800.94   543.5 2801.03
   559.1  2804.4   583.6 2824.76   609.5 2839.52     618 2845.33   626.5  2852.4
   639.3 2860.09   652.5 2865.46   669.2 2874.77   688.1 2882.63   720.7 2899.68
#Mann= 8 ,-1,0
       0     .07       0      70      .1       0  280.91    .025       0
  470.91      .1       0   498.6    .045       0   543.5      .1       0
  600.91     .06       0  700.91      .1       0
Bank Sta=498.6,543.5
XS Rating Curve= 0 ,0
Exp/Cntr=0.3,0.1

Type RM Length L Ch R = 1 ,134825  ,182.1,184.6,189.1
XS GIS Cut Line= 2
2339542.96508981669298.1354123282340220.95940813669261.610465887
#Sta/Elev= 30
       0 2834.59    13.2 2831.36    29.3 2828.79    57.3 2821.87    81.3 2818.93
   105.4 2818.48   121.4 2819.57   181.5 2820.38   197.5 2821.48   237.6 2820.59
   249.6 2817.94   261.6 2816.68   273.6 2809.89   381.8 2809.88   397.8 2810.56
   405.8 2808.92   417.8 2808.21   425.8 2805.72   454.4 2800.33   461.8 2799.97
   501.9 2800.03   507.6 2801.59     514 2804.56     522  2810.4     530 2815.16
     570 2844.25   590.1 2855.63   638.1 2886.04     652 2894.06     679 2907.79
#Mann= 5 ,-1,0
       0      .1       0     370    .025       0   454.4    .045       0
   501.9     .06       0     670      .1       0
Bank Sta=454.4,501.9
XS Rating Curve= 0 ,0
Exp/Cntr(USF)=0,0
Exp/Cntr=0.3,0.1

Type RM Length L Ch R = 1 ,134641  ,258.6,257.7,257.1
XS GIS Cut Line= 2
     2339541.288      669425.4422340183.13983681669466.608447304
#Sta/Elev= 30
       0 2835.62    18.9 2829.19      31 2827.09    95.1 2822.14   127.1 2818.07
   151.2 2817.66   167.2 2815.73   223.3 2812.08   263.4 2810.43   287.5 2811.42
   307.5 2807.21   322.6 2805.99   355.6 2806.08   386.7 2807.54   399.7 2805.34
     413 2800.39   424.3 2799.41   459.8 2799.29   461.6  2799.3   475.9 2799.57
   483.9  2802.7   495.9  2805.5   508.8 2811.41     524 2819.75     540 2831.76
     552 2838.84   576.1 2857.73   600.1 2874.18   620.8 2885.69   643.2 2894.63
#Mann= 5 ,-1,0
       0      .1       0   424.3    .045       0   461.6      .1       0
     470     .06       0     570      .1       0
#XS Ineff= 2 , 0
          383.04 2822.66
Permanent Ineff=
       F       F
Bank Sta=424.3,461.6
XS Rating Curve= 0 ,0
Exp/Cntr=0.3,0.1

Type RM Length L Ch R = 1 ,134383  ,222,225.3,226.6
XS GIS Cut Line= 2
2339356.41997618669677.1943169232340155.38449411669720.149398532
#Sta/Elev= 30
       0 2845.65    51.8 2843.83    71.9 2841.95   131.9 2831.48     152 2823.79
     156 2822.83     164 2822.82     176 2818.62   212.1 2810.98   316.2 2810.56
   356.3 2811.99   389.2  2811.1   420.4 2812.13   428.4 2810.98   480.4 2808.18
   508.5 2804.77   536.5 2806.55   552.6 2802.84   560.6 2799.27     570 2798.69
   584.6  2798.6   623.2 2798.79   628.7 2799.55   648.7    2806   680.7 2826.19
   704.8 2837.86   728.8 2845.69     760  2853.4   768.9 2854.84   800.1 2862.98
#Mann= 9 ,-1,0
       0      .1       0      70     .06       0     390     .12       0
     460     .06       0     560      .1       0     570    .045       0
   623.2      .1       0     660     .06       0     760      .1       0
Bank Sta=570,623.2
XS Rating Curve= 0 ,0
Exp/Cntr(USF)=0,0
Exp/Cntr=0.3,0.1

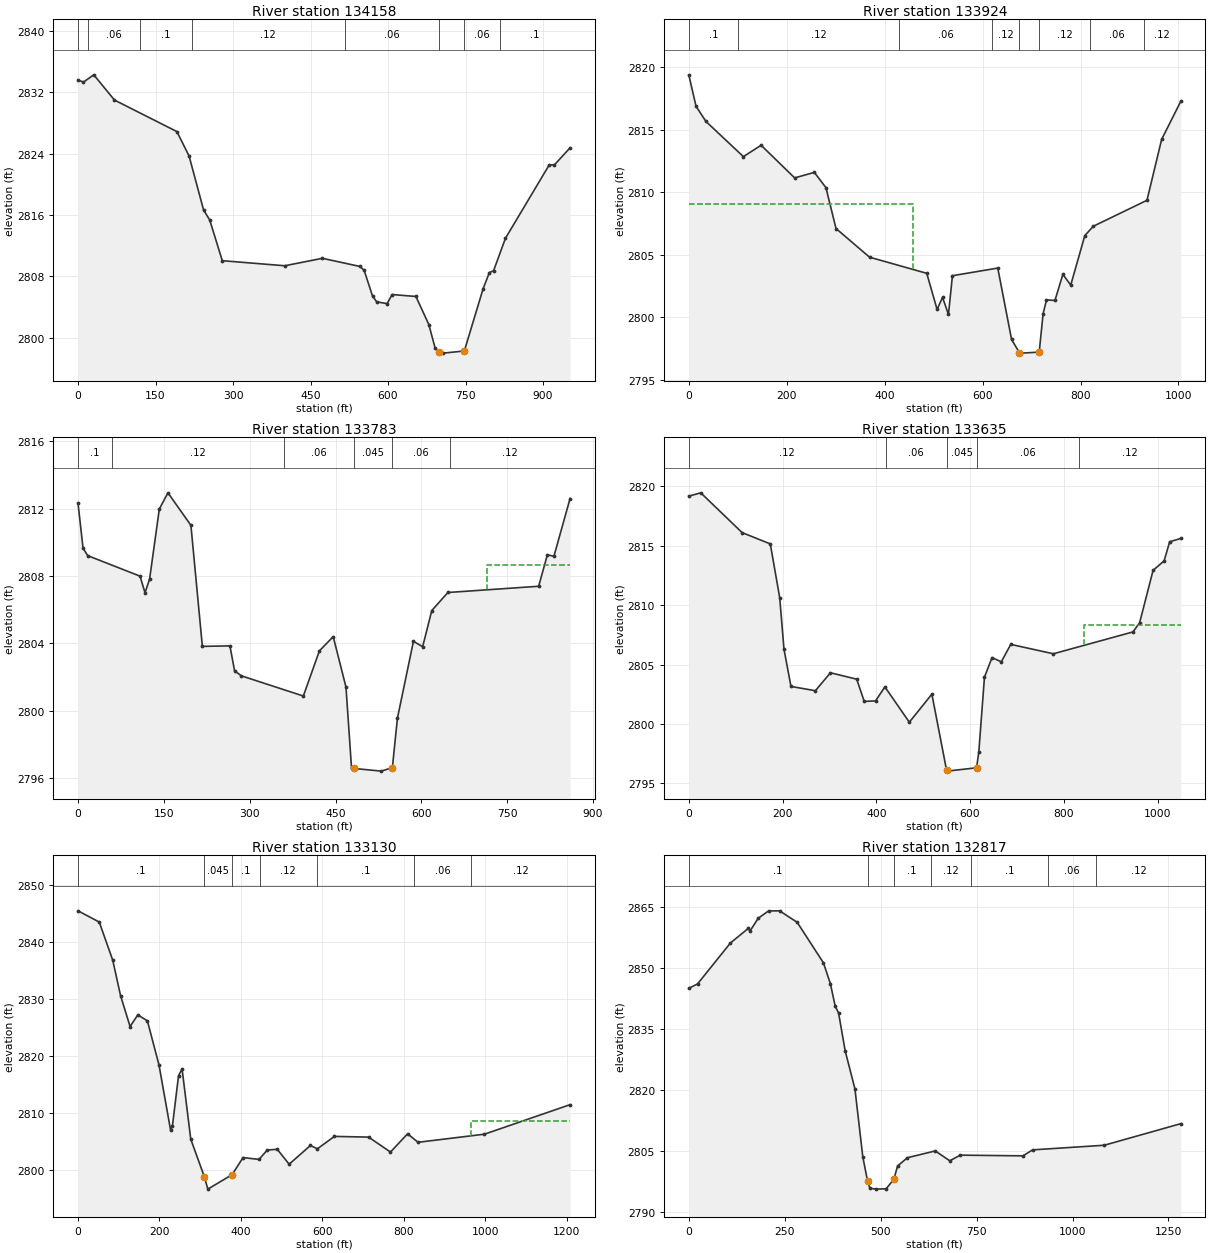
Type RM Length L Ch R = 1 ,134158  ,233.7,234.1,232.9
XS GIS Cut Line= 3
2339205.71302852669851.0032559312339511.33560676669873.177853104
2340150.70251666669963.950597172
#Sta/Elev= 30
       0 2833.58    10.5  2833.3    30.5 2834.25    70.6 2830.96   191.3 2826.86
     215 2823.66   243.1 2816.62   254.9 2815.34   279.2 2810.04   400.2 2809.38
   472.9 2810.35   545.6 2809.29   553.7 2808.79   569.9 2805.45     578 2804.68
   598.2 2804.45   607.9 2805.63   653.9 2805.38     679 2801.71   691.1 2798.65
   698.2 2798.09   706.9    2798   747.6 2798.28     784 2806.39   796.1  2808.5
   804.2 2808.73   827.2 2812.96   912.1 2822.54   921.4 2822.48   952.2 2824.74
#Mann= 8 ,-1,0
       0      .1       0      20     .06       0     120      .1       0
     220     .12       0  516.43     .06       0   698.2    .045       0
   747.6     .06       0  816.43      .1       0
Bank Sta=698.2,747.6
XS Rating Curve= 0 ,0
Exp/Cntr=0.3,0.1

Type RM Length L Ch R = 1 ,133924  ,142.2,140.9,140.2
XS GIS Cut Line= 3
2339197.48617422670080.9720840532340000.74620032670175.473263594
2340176.86203492670089.563100375
#Sta/Elev= 30
       0 2819.38    14.8 2816.87    34.9 2815.66   111.5 2812.84   147.7 2813.75
   216.2 2811.14   256.4 2811.58   280.1 2810.36   300.7 2807.09   369.2  2804.8
     486 2803.51   507.1 2800.62   518.2 2801.59   530.3 2800.22   538.4 2803.32
     631 2803.93   659.2 2798.22   675.3 2797.16   679.3 2797.13   715.6 2797.21
   723.6 2800.28   730.5 2801.39   747.8 2801.34   763.9 2803.43     780 2802.57
   808.8 2806.53     826 2807.27   935.7 2809.35   965.6 2814.21  1004.8 2817.27
#Mann= 8 ,-1,0
       0      .1       0     100     .12       0     430     .06       0
     620     .12       0   675.3    .045       0   715.6     .12       0
   818.8     .06       0   928.8     .12       0
#XS Ineff= 2 , 0
          457.13 2809.05
Permanent Ineff=
       F       F
Bank Sta=675.3,715.6
XS Rating Curve= 0 ,0
Exp/Cntr(USF)=0,0
Exp/Cntr=0.3,0.1

Type RM Length L Ch R = 1 ,133783  ,152.6,148,143.9
XS GIS Cut Line= 3
 2339363.3555269670266.3301391782340063.19203983670315.038647402
 2340205.4475043670245.493824331
#Sta/Elev= 30
       0 2812.32     8.8 2809.65    16.9 2809.21   108.4 2807.99   117.1    2807
   125.1 2807.82   142.1 2811.98   157.2 2812.94   197.3 2811.01   217.3 2803.82
   265.5 2803.85   273.6 2802.37   285.5 2802.07   393.8 2800.87   421.8 2803.55
     446  2804.4   468.3  2801.4     478  2796.6     482 2796.57   530.1 2796.41
   549.4 2796.62   558.2 2799.55   586.2 2804.12   602.3  2803.8   618.3 2805.95
   646.4 2807.02     805 2807.39   820.3 2809.26   831.7 2809.17   859.9  2812.6
#Mann= 6 ,-1,0
       0      .1       0      60     .12       0     360     .06       0
     482    .045       0   549.4     .06       0     650     .12       0
#XS Ineff= 2 , 0
                          715.59         2808.63
Permanent Ineff=
       F       F
Bank Sta=482,549.4
XS Rating Curve= 0 ,0
Exp/Cntr=0.3,0.1

Type RM Length L Ch R = 1 ,133635  ,508,505.3,476.3
XS GIS Cut Line= 3
2339298.60799152670487.1732925042340068.73633353670438.381479676
 2340272.2217417670248.927823417
#Sta/Elev= 30
       0 2819.18    25.6 2819.46   113.8 2816.11   173.9 2815.16     194 2810.63
   203.1  2806.3     218 2803.16   270.1  2802.8   302.2 2804.31   358.3 2803.77
   374.3  2801.9   398.4 2801.94   418.4 2803.12   470.5 2800.15   518.6 2802.51
   549.9 2796.12   550.7 2796.03     614 2796.31   618.8 2797.67   630.8 2803.94
   646.9 2805.59   666.7 2805.23   686.9  2806.7   777.8 2805.91   947.6 2807.75
   961.8 2808.52   990.6 2812.94  1014.1 2813.73  1025.9 2815.34  1049.7 2815.62
#Mann= 5 ,-1,0
       0     .12       0     420     .06       0   549.9    .045       0
     614     .06       0  831.67     .12       0
#XS Ineff= 2 , 0
                          842.84          2808.3
Permanent Ineff=
       F       F
Bank Sta=549.9,614
XS Rating Curve= 0 ,0
Exp/Cntr(USF)=0,0
Exp/Cntr=0.3,0.1

Type RM Length L Ch R = 1 ,133130  ,325.9,312.5,282.6
XS GIS Cut Line= 3
 2339448.0579401671096.9760895592339774.68214946670890.807245864
2340360.39442746670313.577099322
#Sta/Elev= 30
       0 2845.43    52.2 2843.46    85.3 2836.77   104.5 2830.56   127.9 2825.15
   146.8 2827.19   170.4 2826.15   198.8 2818.45   227.2 2807.07   231.9 2807.72
   246.9 2816.52   255.6 2817.72   276.9 2805.42   310.2 2798.84   318.9 2796.65
   378.6 2799.19   405.4 2802.18   444.5 2801.86   464.8  2803.5   489.4 2803.63
   518.6 2801.02   570.9  2804.3     588 2803.72   629.8 2805.89   713.7 2805.77
   767.5 2803.15   809.5 2806.34   835.4 2804.86   998.3 2806.28  1208.6 2811.45
#Mann= 7 ,-1,0
       0      .1       0   310.2    .045       0   378.6      .1       0
  446.25     .12       0  586.25      .1       0  826.25     .06       0
  966.25     .12       0
#XS Ineff= 2 , 0
                          964.26         2808.66
Permanent Ineff=
       F       F
Bank Sta=310.2,378.6
XS Rating Curve= 0 ,0
Exp/Cntr=0.3,0.1

Type RM Length L Ch R = 1 ,132817  ,188.7,187.1,185.7
XS GIS Cut Line= 4
 2339853.9158305671466.647237984   2340084.16396 670852.22110786
2340170.54689428670538.5397302532340386.57129943670329.556583771
#Sta/Elev= 30
       0 2845.03    22.9 2846.13   108.5 2856.21   155.3 2859.82   159.6 2859.16
     181 2862.31     208 2864.11   236.5 2864.13   282.5  2861.3   350.9 2851.31
   368.9 2846.19   381.7 2840.58   390.3 2838.99   407.4 2829.69     433 2820.24
   453.4 2803.55   465.9 2797.53   472.1 2795.76   488.5 2795.57   514.2 2795.66
   534.2 2797.96   544.1 2801.27   569.7 2803.31   642.3 2804.98   680.1 2802.55
   707.4 2803.94   870.9 2803.77   895.8 2805.24  1082.6 2806.38  1282.1  2811.7
#Mann= 7 ,-1,0
       0      .1       0   465.9    .045       0   534.2      .1       0
     630     .12       0  736.15      .1       0  936.15     .06       0
 1061.51     .12       0
Bank Sta=465.9,534.2
XS Rating Curve= 0 ,0
Exp/Cntr(USF)=0,0
Exp/Cntr=0.3,0.1