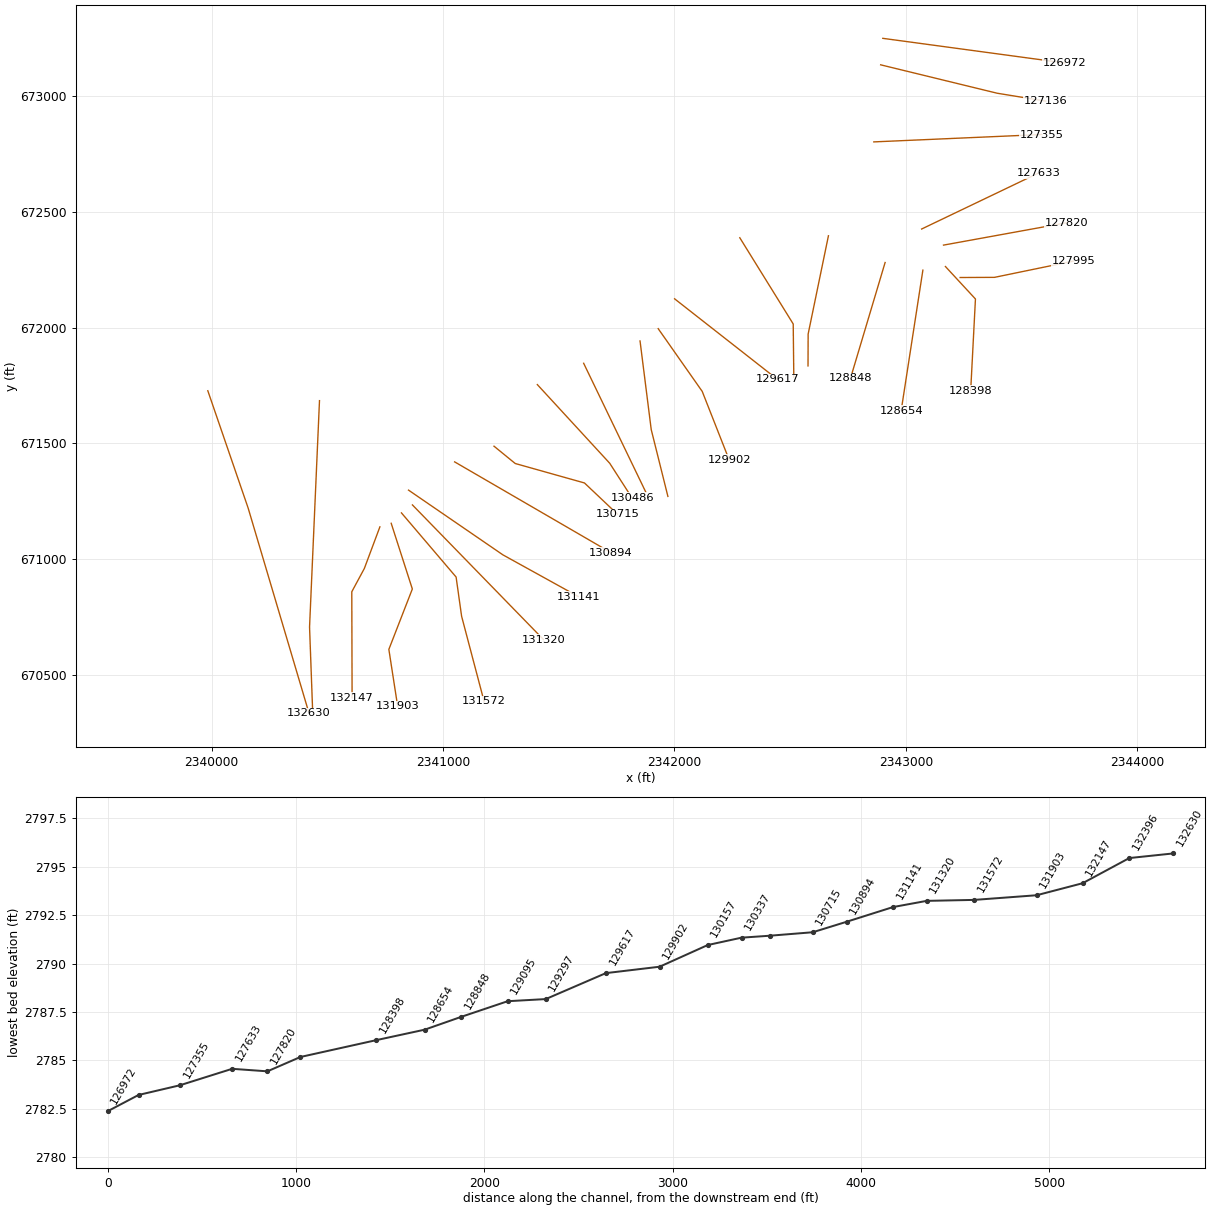
HEC-RAS study GLADYFK.prj: GLADYFK

--- GLADYFK.g01 (geometry) --- (continued)

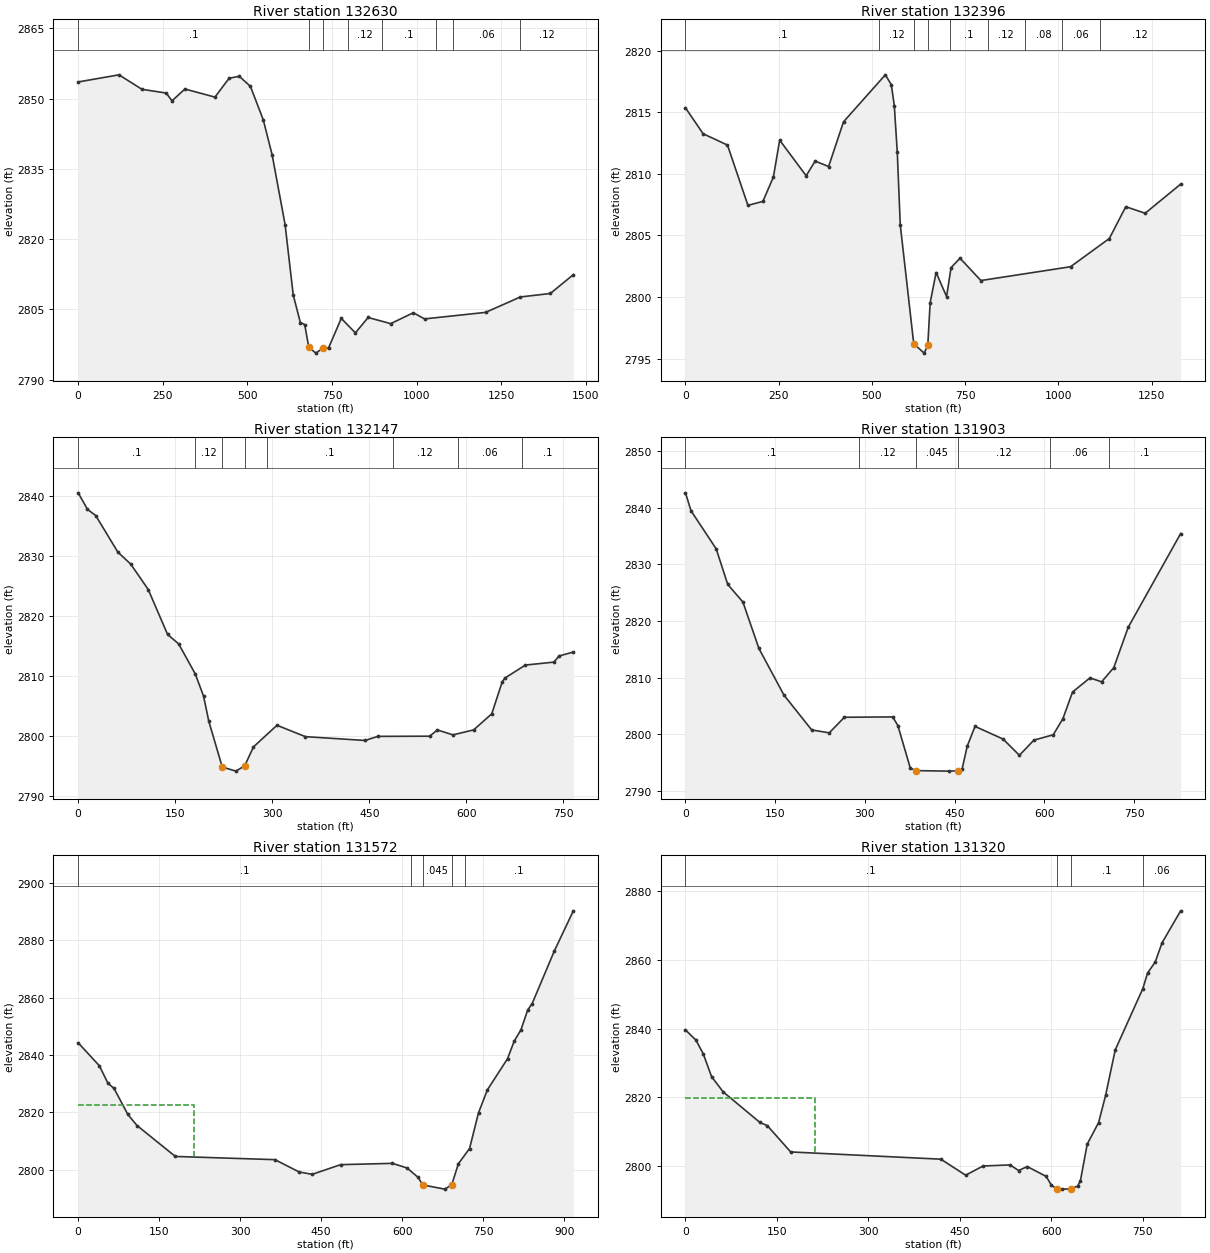
Type RM Length L Ch R = 1 ,132630  ,242.7,234.3,229
XS GIS Cut Line= 3
2339983.76629598671727.2440304592340158.03896349 671219.84678722
2340421.27696349670331.927265831
#Sta/Elev= 30
       0 2853.53   120.6 2855.05   188.3 2851.96   260.2 2851.16   277.1  2849.5
   315.2 2852.02     404  2850.3   445.8 2854.32   475.9 2854.74   508.8 2852.58
   546.8 2845.43   572.9 2837.99   611.2  2823.1   635.2  2808.1   656.2 2802.22
   669.1 2801.78   681.1 2796.94     702 2795.69   722.8 2796.75   739.5 2796.79
   777.1  2803.1   818.8 2800.01   856.4 2803.29   923.1 2801.98   989.9  2804.3
  1023.2 2802.99  1203.3 2804.38  1306.2 2807.67  1394.6 2808.41  1462.6 2812.43
#Mann= 8 ,-1,0
       0      .1       0   681.1    .045       0   722.8      .1       0
  796.49     .12       0  896.49      .1       0 1056.49     .08       0
 1106.49     .06       0 1306.49     .12       0
Bank Sta=681.1,722.8
XS Rating Curve= 0 ,0
Exp/Cntr=0.3,0.1

Type RM Length L Ch R = 1 ,132396  ,256.5,248.2,239.2
XS GIS Cut Line= 3
 2340466.3018587671684.4677317672340423.34677709670705.091871069
2340436.13162354670358.116040858
#Sta/Elev= 30
       0 2815.35    47.3 2813.25   112.6 2812.33   167.4 2807.44   207.5 2807.76
   235.7 2809.74   252.5 2812.73   323.5 2809.84   347.6 2811.03   383.7 2810.59
   423.7 2814.22   535.8 2818.03   551.8 2817.23   559.8 2815.54   567.8 2811.75
   575.8 2805.86   611.9 2796.21   639.9 2795.45   649.6 2796.08   655.9 2799.53
   671.9 2801.99     700 2800.04     712 2802.39     736 2803.15     792 2801.34
  1032.3 2802.46  1136.3 2804.75  1180.4 2807.33  1232.4  2806.8  1327.5 2809.16
#Mann= 9 ,-1,0
       0      .1       0     520     .12       0   611.9    .045       0
   649.6     .12       0     710      .1       0     810     .12       0
     910     .08       0 1010.32     .06       0 1110.32     .12       0
Bank Sta=611.9,649.6
XS Rating Curve= 0 ,0
Exp/Cntr(USF)=0,0
Exp/Cntr=0.3,0.1

Type RM Length L Ch R = 1 ,132147  ,238,244,253.9
XS GIS Cut Line= 4
2340727.31701581671138.6485964022340660.07374687670958.527733291
2340605.86947009 670857.87484813 2340607.1821267670399.024788692
#Sta/Elev= 30
       0 2840.51    14.4 2837.76    27.2 2836.71    61.3 2830.64    81.3 2828.63
   108.3  2824.4   138.2 2816.92   155.3 2815.35   180.9 2810.36   193.8 2806.65
     202 2802.42   222.7 2794.84   243.8 2794.15   257.4 2795.04     271 2798.19
   307.3 2801.79   351.3 2799.89   443.3 2799.26   463.3 2799.94   543.3 2799.97
   555.3 2801.01   579.3 2800.19   611.3 2801.02   639.3  2803.7   655.3 2808.97
   659.3 2809.63   691.3 2811.82   735.3 2812.31   743.3 2813.33   765.4 2813.99
#Mann= 8 ,-1,0
       0      .1       0     180     .12       0   222.7    .045       0
   257.4     .12       0  292.26      .1       0  486.58     .12       0
  586.58     .06       0  686.58      .1       0
Bank Sta=222.7,257.4
XS Rating Curve= 0 ,0
Exp/Cntr=0.3,0.1

Type RM Length L Ch R = 1 ,131903  ,314.5,331.2,346.1
XS GIS Cut Line= 4
2340776.17874355671153.9985046682340867.49110965670869.915587905
2340766.03292509670608.660762666 2340804.0797443670362.624665112
#Sta/Elev= 30
       0 2842.61     9.3 2839.43    51.3 2832.74    70.6 2826.46      96 2823.35
   122.7 2815.17   164.7 2806.92   210.9  2800.8   240.3 2800.28   265.6 2803.03
   346.4 2803.09     355 2801.56   375.7 2794.08   384.9 2793.62   440.6 2793.53
   455.2 2793.59   462.3 2793.88   470.8  2797.9   483.9 2801.42   530.9 2799.18
   558.1 2796.32   582.2 2798.99   614.6 2799.94   630.8 2802.78   646.9 2807.48
     676 2809.97   695.5 2809.28   715.8 2811.78     740 2818.91   827.6 2835.43
#Mann= 6 ,-1,0
       0      .1       0     290     .12       0   384.9    .045       0
   455.2     .12       0  608.66     .06       0  708.66      .1       0
Bank Sta=384.9,455.2
XS Rating Curve= 0 ,0
Exp/Cntr(USF)=0,0
Exp/Cntr=0.3,0.1

Type RM Length L Ch R = 1 ,131572  ,240.5,252.2,266.3
XS GIS Cut Line= 4
2340820.42726309671199.0011814822341056.59356797670921.602145489
2341080.35050792670752.0522448272341177.61219489  670383.3579659
#Sta/Elev= 30
       0 2844.29    39.2 2836.29    55.1  2830.2    66.4 2828.39    91.9 2819.33
   108.9 2815.46   179.9 2804.68   364.3 2803.56   409.2 2799.26   433.4 2798.45
   485.9 2801.82   581.9 2802.27   608.8 2800.67   629.5 2797.37   637.8 2794.76
   678.5 2793.29   691.6 2794.75   691.6 2794.76   691.6  2794.8     704 2802.16
   724.6 2807.43   741.2 2819.89   757.7  2827.9     795 2838.76   807.4 2844.92
   819.8  2848.8   832.2 2855.68   840.5 2857.94   881.8 2876.38   916.8 2890.28
#Mann= 5 ,-1,0
       0      .1       0  615.52     .06       0   637.8    .045       0
   691.6     .06       0  715.52      .1       0
#XS Ineff= 2 , 0
          213.68 2822.51
Permanent Ineff=
       F       F
Bank Sta=637.8,691.6
XS Rating Curve= 0 ,0
Exp/Cntr=0.3,0.1

Type RM Length L Ch R = 1 ,131320  ,179.1,179,184
XS GIS Cut Line= 2
2340867.88468511671233.4295854032341434.02135495670651.313251499
#Sta/Elev= 30
       0  2839.6    17.1 2836.64    29.1 2832.66    42.8 2825.99    61.7 2821.58
     122 2812.67   134.3 2811.71   172.5 2804.07   418.8 2801.96   459.4  2797.3
   488.1 2799.98   532.2 2800.29   546.3 2798.66   560.5 2799.81   591.4 2796.95
   600.1 2794.38   608.5 2793.34     617 2793.24   631.5 2793.29     643  2794.1
   647.6 2795.68   658.8 2806.35   677.4  2812.6   688.9 2820.52   704.7 2833.77
     750 2851.65   757.7 2856.15   770.4 2859.42   781.5 2864.97     812 2874.28
#Mann= 4 ,-1,0
       0      .1       0   608.5    .045       0   631.5      .1       0
     750     .06       0
#XS Ineff= 2 , 0
          212.55  2819.7
Permanent Ineff=
       F       F
Bank Sta=608.5,631.5
XS Rating Curve= 0 ,0
Exp/Cntr(USF)=0,0
Exp/Cntr=0.3,0.1

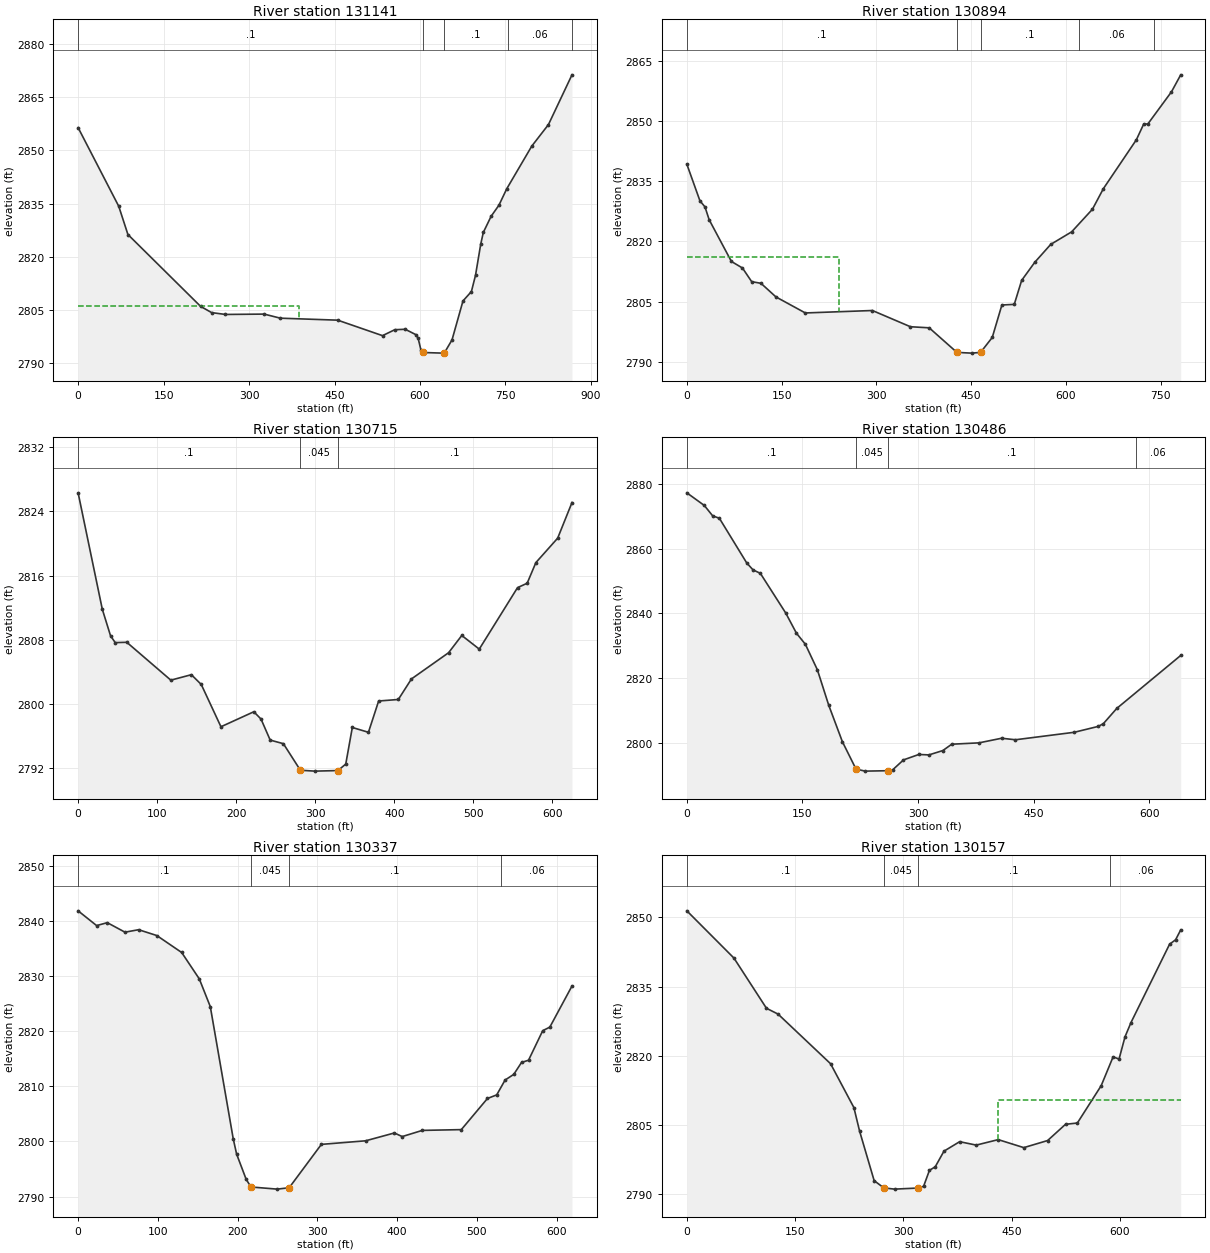
Type RM Length L Ch R = 1 ,131141  ,250,246.7,249.3
XS GIS Cut Line= 3
 2340851.0180341671297.5149025552341258.90911571671017.443228991
2341584.28852618670837.387081609
#Sta/Elev= 30
       0 2856.41    71.3 2834.27    87.4 2826.32   214.9 2806.09   234.3 2804.33
   258.6 2803.81   326.5 2803.91   354.9 2802.76   455.6  2802.2   534.2 2797.84
   555.7 2799.51     574 2799.64     593  2798.1   596.8 2797.06   601.4 2793.93
   604.8  2793.1   640.1 2792.92   642.5 2792.92   656.2 2796.66   675.4 2807.61
   690.2 2810.26   697.4 2814.83   706.5 2823.56   711.1 2826.91   724.8 2831.45
   738.5 2834.57   752.2 2839.19   796.1  2851.2   825.4 2857.27   866.7 2871.28
#Mann= 5 ,-1,0
       0      .1       0   604.8    .045       0   642.5      .1       0
  754.79     .06       0  866.66      .1       0
#XS Ineff= 2 , 0
           386.8 2806.26
Permanent Ineff=
       F       F
Bank Sta=604.8,642.5
XS Rating Curve= 0 ,0
Exp/Cntr=0.3,0.1

Type RM Length L Ch R = 1 ,130894  ,171,179.5,181
XS GIS Cut Line= 2
2341050.28882579671419.6171838982341726.00033495671026.974009656
#Sta/Elev= 30
       0 2839.19    20.7 2830.08    28.7 2828.56    35.3 2825.37    70.5 2814.98
      88 2813.35   102.6 2809.95   117.3 2809.54     141 2806.15   187.5 2802.16
   293.6 2802.77   353.8 2798.73   383.5 2798.46   427.4 2792.34   450.7 2792.16
   464.8 2792.34   483.3 2796.07   498.5 2804.14   518.1  2804.3   529.8 2810.27
   550.6 2814.78   575.8 2819.23   608.9 2822.35   641.8 2827.98   659.1  2833.1
   711.3 2845.27     723 2849.21   729.4 2849.19   766.9 2857.22   781.5 2861.44
#Mann= 5 ,-1,0
       0      .1       0   427.4    .045       0   464.8      .1       0
     620     .06       0     740      .1       0
#XS Ineff= 2 , 0
          241.49 2816.13
Permanent Ineff=
       F       F
Bank Sta=427.4,464.8
XS Rating Curve= 0 ,0
Exp/Cntr(USF)=0,0
Exp/Cntr=0.3,0.1

Type RM Length L Ch R = 1 ,130715  ,244.2,229.1,221.3
XS GIS Cut Line= 4
2341220.43973323671487.3835150312341312.06104239671412.590609593
2341611.23266414671328.4485909742341753.33918448671193.821361185
#Sta/Elev= 30
       0 2826.31    30.6  2811.8      41  2808.5    46.9 2807.64    61.6 2807.68
   117.3 2802.96   143.3 2803.64   155.8 2802.42   180.7 2797.15   222.3 2799.02
   231.4 2798.11     243 2795.49   259.7 2795.04   281.2 2791.73   299.5 2791.62
   328.7 2791.69   338.6  2792.5   346.9 2797.06   367.3 2796.46   380.2 2800.36
   405.1 2800.55   421.7 2803.11   468.7 2806.38   485.4 2808.53   507.5 2806.83
   555.9 2814.49   568.1 2815.04   579.1 2817.61   606.7 2820.66   624.8  2825.1
#Mann= 3 ,-1,0
       0      .1       0   281.2    .045       0   328.7      .1       0
Bank Sta=281.2,328.7
XS Rating Curve= 0 ,0
Exp/Cntr(USF)=0,0
Exp/Cntr=0.3,0.1

Type RM Length L Ch R = 1 ,130486  ,158.1,149.1,147
XS GIS Cut Line= 3
2341407.60716038671753.8626460042341720.45788489671413.508858486
2341817.02721608671263.410813155
#Sta/Elev= 30
       0 2877.16    22.7 2873.26    33.5 2870.07    42.2 2869.33    77.7 2855.56
    85.8 2853.45    95.4 2852.35   128.3 2840.14   142.2 2833.92   153.8 2830.51
   169.4 2822.63   184.1 2811.73   201.8 2800.51   219.5 2792.06   231.4 2791.44
   260.9 2791.57   267.2 2791.87   281.1  2794.9     301 2796.57   314.1 2796.44
   332.1 2797.77   343.7 2799.73   379.1 2800.15   408.4 2801.57   426.4  2801.1
   502.8 2803.41     534 2805.23   540.5 2806.08   557.8 2810.75   640.8 2827.07
#Mann= 4 ,-1,0
       0      .1       0   219.5    .045       0   260.9      .1       0
  582.29     .06       0
Bank Sta=219.5,260.9
XS Rating Curve= 0 ,0
Exp/Cntr=0.3,0.1

Type RM Length L Ch R = 1 ,130337  ,185,179.2,169.8
XS GIS Cut Line= 2
2341607.72948676671846.1202428642341876.59367584671288.100227792
#Sta/Elev= 30
       0  2841.9    23.2 2839.22    36.6 2839.75    58.8 2838.02    75.9 2838.47
    98.7 2837.41   129.9 2834.33     152 2829.53   165.8 2824.49   194.5 2800.52
   198.8  2797.7   210.8 2793.11   216.8 2791.73   249.7 2791.34   264.7 2791.59
   305.1 2799.47   360.6 2800.12   396.6 2801.54   406.5 2800.89   431.7 2802.01
   480.6 2802.15   513.4 2807.81     525 2808.46   535.5 2811.16   546.4 2812.19
   556.1 2814.35   564.9 2814.76   582.7 2820.13   591.6 2820.77   619.4 2828.24
#Mann= 4 ,-1,0
       0      .1       0   216.8    .045       0   264.7      .1       0
     530     .06       0
Bank Sta=216.8,264.7
XS Rating Curve= 0 ,0
Exp/Cntr(USF)=0,0
Exp/Cntr=0.3,0.1

Type RM Length L Ch R = 1 ,130157  ,249.9,255.7,259.7
XS GIS Cut Line= 3
2341851.36553084671942.597727535 2341899.6821491 671559.45966197
2341971.74176736671270.310785334
#Sta/Elev= 30
       0 2851.45    65.3 2841.17   110.3 2830.27   126.4    2829   199.1 2818.22
   231.4 2808.69   239.3 2803.58   259.5  2792.8   272.9 2791.23   287.7 2790.96
   320.6  2791.2     328 2791.58   336.1 2795.05   344.1 2795.81   356.2 2799.21
   377.9 2801.27   400.9 2800.53   431.4 2801.72   466.8 2799.98   499.8 2801.52
   524.6 2805.05     541 2805.33     574 2813.44   590.5  2819.7   598.8 2819.24
     607 2824.06   615.3 2827.17   668.8  2844.2   677.1 2845.16   684.2 2847.31
#Mann= 4 ,-1,0
       0      .1       0   272.9    .045       0   320.6      .1       0
  586.17     .06       0
#XS Ineff= 2 , 0
                          431.71         2810.31
Permanent Ineff=
       F       F
Bank Sta=272.9,320.6
XS Rating Curve= 0 ,0
Exp/Cntr=0.3,0.1

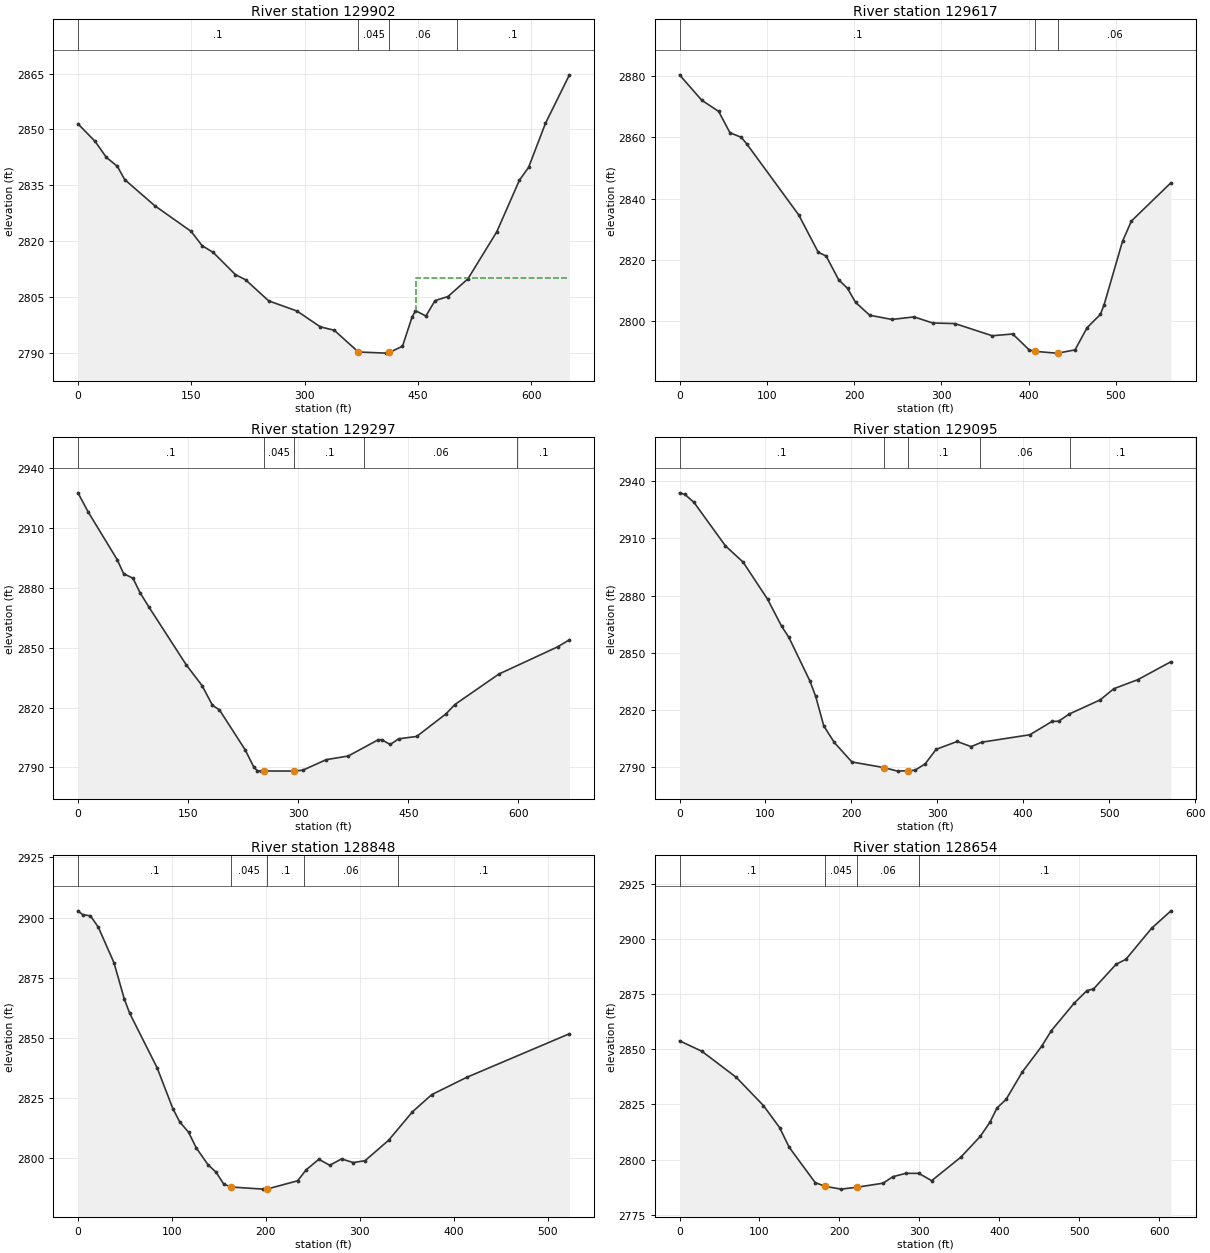
Type RM Length L Ch R = 1 ,129902  ,272.4,285.2,293.7
XS GIS Cut Line= 3
2341929.85922273671995.7710650882342120.09331878671724.370421394
2342236.77023102 671427.60523156
#Sta/Elev= 30
       0 2851.47    22.7 2846.75    37.4 2842.49      52 2840.08    61.8 2836.49
   101.6 2829.47   149.7 2822.57   164.3 2818.72     179  2816.9   208.3 2810.95
   221.8 2809.55   252.3 2803.89   289.8 2801.16   320.7  2796.9   339.2 2795.98
     371 2790.14   407.9 2789.84   412.2 2790.04   429.4 2791.69   441.9 2799.45
   446.6 2801.25   460.4 2799.83   472.4 2803.95   489.6 2805.06     516 2809.82
   554.1 2822.44   584.1 2836.32   596.2 2839.76   618.5 2851.57   650.3 2864.65
#Mann= 4 ,-1,0
       0      .1       0     371    .045       0   412.2     .06       0
  501.43      .1       0
#XS Ineff= 2 , 0
                          446.75         2809.96
Permanent Ineff=
       F       F
Bank Sta=371,412.2
XS Rating Curve= 0 ,0
Exp/Cntr(USF)=0,0
Exp/Cntr=0.3,0.1

Type RM Length L Ch R = 1 ,129617  ,319.3,319.2,299.1
XS GIS Cut Line= 2
2342000.64101027672124.8774249822342443.83678095671777.313993152
#Sta/Elev= 30
       0 2880.44    25.4 2872.17    44.9 2868.48    57.8 2861.53    70.7 2860.03
    77.3 2857.79   136.7 2834.64     159 2822.46     168 2821.26   182.4 2813.48
   192.6 2810.66   201.7  2806.1     218 2801.89   243.4 2800.51   268.8 2801.35
   290.1 2799.36   315.7 2799.16   358.4 2795.19   381.9 2795.76     401 2790.49
   407.9 2790.08   431.5 2789.51   433.8 2789.51   453.3 2790.58   467.1 2797.84
   482.3 2802.15   486.6 2805.35   507.7 2826.07   517.9 2832.68   563.2 2845.18
#Mann= 3 ,-1,0
       0      .1       0   407.9    .045       0   433.8     .06       0
Bank Sta=407.9,433.8
XS Rating Curve= 0 ,0
Exp/Cntr=0.3,0.1

Type RM Length L Ch R = 1 ,129297  ,212,202.1,181.8
XS GIS Cut Line= 3
2342282.42641407672388.9215302522342513.24378394672016.062701999
2342515.78023855671785.245332129
#Sta/Elev= 30
       0 2927.53    13.8 2917.99    53.4 2894.08    62.1 2887.08      75 2884.72
    84.4 2877.59      97 2870.12   147.7 2841.26   169.1 2830.95   183.2 2821.11
   192.6 2818.88   227.7 2798.87   239.6  2790.1   244.3 2788.42     249 2788.17
   253.1 2788.24   294.6 2788.21   306.2 2788.62   338.1 2793.91   368.1 2795.74
     409 2803.88   413.7 2803.91   425.3 2801.51   436.9 2804.36   461.4 2805.55
   501.4 2816.89   513.4 2821.53   573.4  2836.8   653.4 2850.41   669.4 2853.96
#Mann= 5 ,-1,0
       0      .1       0   253.1    .045       0   294.6      .1       0
     390     .06       0  598.52      .1       0
Bank Sta=253.1,294.6
XS Rating Curve= 0 ,0
Exp/Cntr(USF)=0,0
Exp/Cntr=0.3,0.1

Type RM Length L Ch R = 1 ,129095  ,250.4,247.5,246.6
XS GIS Cut Line= 3
2342665.43522899 672397.611805112342577.72478685  671972.5283788
2342577.19333542671834.700530645
#Sta/Elev= 30
       0 2933.86     6.2 2933.04    16.8 2928.89    53.5 2906.04      74 2897.58
   102.5 2878.12   118.9 2863.89   127.1 2858.29   151.6 2835.43   158.5 2827.18
   167.9 2811.73   180.1 2803.09   200.6 2792.86   238.4 2789.87   253.7 2788.06
   265.9 2788.28   274.1 2788.55   285.8 2791.84   298.6 2799.46   323.1  2803.6
   339.4 2800.89   351.7 2803.22   407.7 2807.12   433.4 2814.06   441.4 2814.24
   453.4 2817.96   489.4 2825.35   505.4 2831.24   533.4 2835.99   571.9 2845.39
#Mann= 5 ,-1,0
       0      .1       0   238.4    .045       0   265.9      .1       0
     350     .06       0  454.04      .1       0
Bank Sta=238.4,265.9
XS Rating Curve= 0 ,0
Exp/Cntr=0.3,0.1

Type RM Length L Ch R = 1 ,128848  ,190.8,193.5,196.2
XS GIS Cut Line= 2
2342910.27795963672281.8394155732342760.66541038671780.811343679
#Sta/Elev= 30
       0 2902.77     4.9  2901.2    13.2  2900.7    21.5  2896.1    38.3 2881.21
    49.3 2866.16      55 2860.24    84.2 2837.63   100.9 2820.71   108.3 2815.13
   117.6  2810.9   125.9 2804.34   138.4 2797.37   146.9 2794.28   155.1 2789.33
     163 2788.13   196.9 2787.25   201.1 2787.28   233.7 2790.71   242.8 2795.27
   256.2 2799.63   267.9 2797.16   280.4 2799.78   292.9 2798.29   305.4 2799.05
   330.5 2807.54   355.8 2819.31   376.4 2826.48   413.7 2833.67   522.9 2851.75
#Mann= 5 ,-1,0
       0      .1       0     163    .045       0   201.1      .1       0
     240     .06       0     340      .1       0
Bank Sta=163,201.1
XS Rating Curve= 0 ,0
Exp/Cntr(USF)=0,0
Exp/Cntr=0.3,0.1

Type RM Length L Ch R = 1 ,128654  ,255.7,256.8,260.1
XS GIS Cut Line= 2
2343073.51114738672248.9080475092342979.72414738      671641.396
#Sta/Elev= 30
       0  2853.9    28.1 2849.11    71.1 2837.28     105  2824.5   125.2 2814.52
   137.3 2805.53   169.7 2789.56   181.9 2787.89   202.1 2786.59   221.8 2787.45
   254.7 2789.29   266.9 2792.23     283 2793.75   299.2 2793.76   315.4 2790.43
   351.8 2801.06   376.1 2810.49   388.3 2816.95   397.1  2823.4   408.5 2827.33
   428.7  2839.7   452.8 2851.31   465.2 2858.54   493.5 2870.91   509.7  2876.7
   517.8 2877.39   546.1 2888.63   558.3 2890.86   590.6 2904.98   614.7 2912.86
#Mann= 4 ,-1,0
       0      .1       0   181.9    .045       0   221.8     .06       0
     300      .1       0
Bank Sta=181.9,221.8
XS Rating Curve= 0 ,0
Exp/Cntr=0.3,0.1

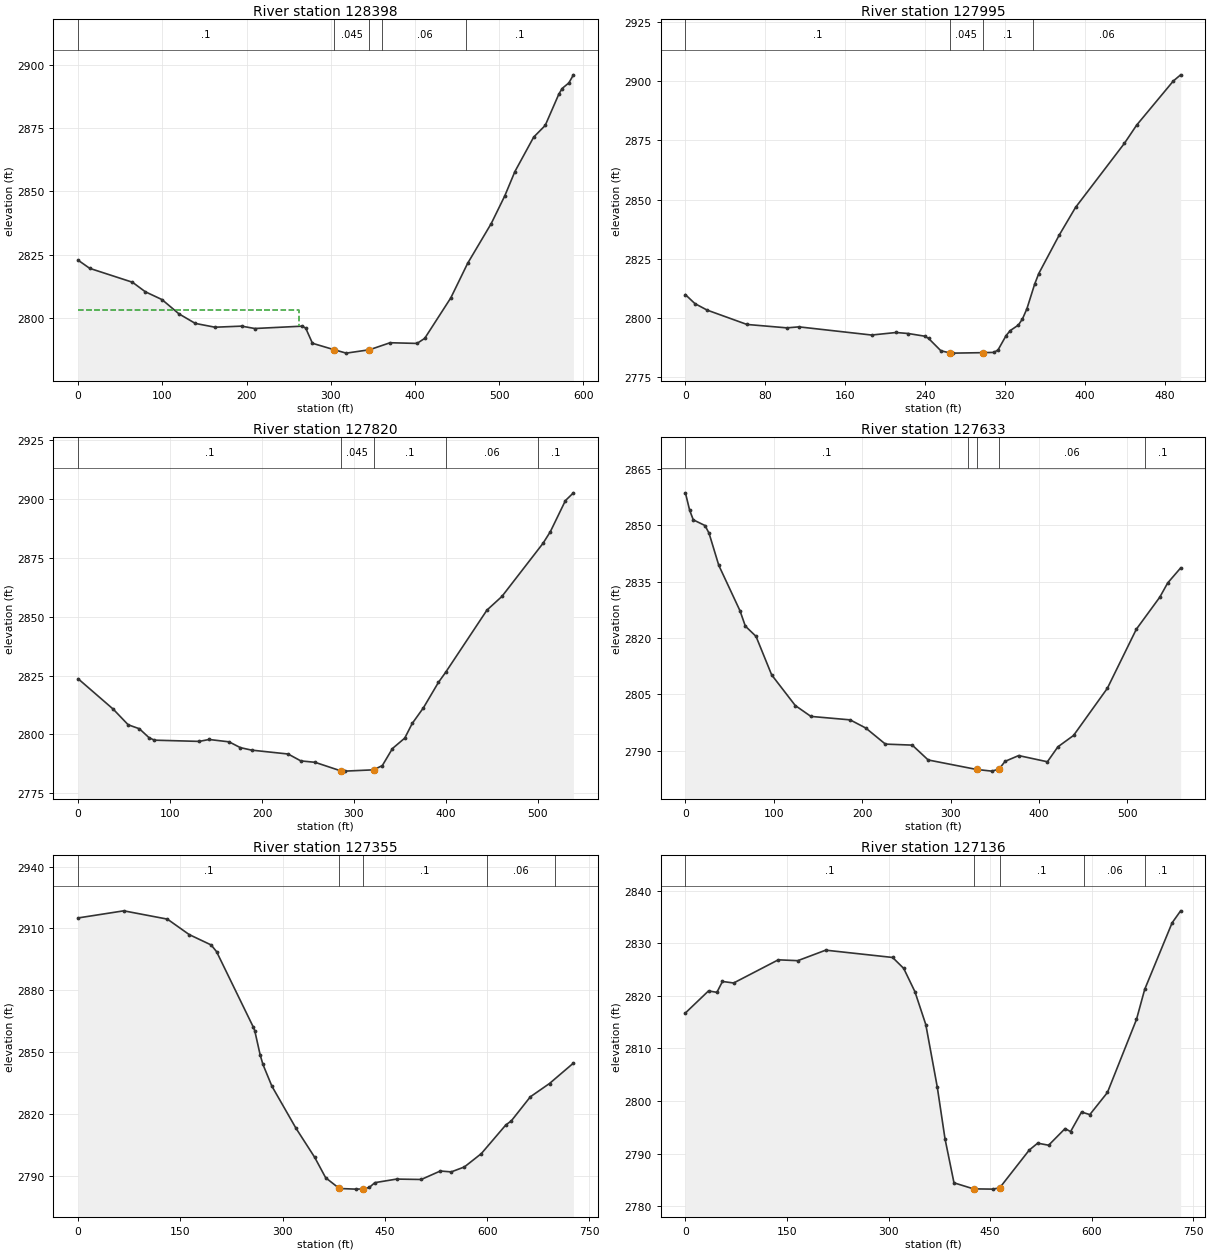
Type RM Length L Ch R = 1 ,128398  ,361.4,402.8,430.8
XS GIS Cut Line= 3
2343170.88864747672264.5233725422343300.63402136672124.185455299
2343280.06597237671727.783056474
#Sta/Elev= 30
       0  2822.8    13.7 2819.59    64.5 2814.09    79.7 2810.33    99.5 2807.24
   119.7 2801.58   139.1  2797.8   162.5  2796.3   194.1 2796.73   209.7 2795.79
   266.2 2796.72   270.2 2795.93   278.2 2789.95   303.7 2787.42   318.3 2786.05
   345.9 2787.38   370.4 2790.16   402.4 2789.89   411.5 2791.89   442.5 2807.92
   462.5 2821.59   490.5 2837.32   506.6 2848.27   518.6 2857.88   540.9 2871.51
   554.6 2876.13   570.6 2888.39   574.6 2890.73   582.7 2892.96   588.1 2896.15
#Mann= 5 ,-1,0
       0      .1       0   303.7    .045       0   345.9      .1       0
  361.12     .06       0  461.12      .1       0
#XS Ineff= 2 , 0
          262.29 2803.07
Permanent Ineff=
       F       F
Bank Sta=303.7,345.9
XS Rating Curve= 0 ,0
Exp/Cntr(USF)=0,0
Exp/Cntr=0.3,0.1

Type RM Length L Ch R = 1 ,127995  ,175.2,175.2,174.3
XS GIS Cut Line= 3
2343234.50646151 672216.982102152343382.90621734672217.676587097
2343723.30439166672287.965010187
#Sta/Elev= 30
       0 2809.88     9.5  2806.1    21.7 2803.36    61.6 2797.29   101.7 2795.85
   113.7 2796.27   186.5 2792.82     211 2793.89   223.2 2793.46   239.6 2792.34
   243.6 2791.37   255.9 2786.16   264.6  2785.3   268.1 2785.18     298 2785.38
     309 2785.49   313.1 2786.53   321.2  2792.6   325.3 2794.69   333.5 2797.04
   337.6 2799.65     342 2803.89   349.8 2814.33   353.9 2818.79   374.3 2834.96
   390.7 2846.69   439.7 2873.78   451.9 2881.44   488.7 2900.11     496 2902.69
#Mann= 4 ,-1,0
       0      .1       0   264.6    .045       0     298      .1       0
   348.4     .06       0
Bank Sta=264.6,298
XS Rating Curve= 0 ,0
Exp/Cntr=0.3,0.1

Type RM Length L Ch R = 1 ,127820  ,179.4,187.1,189.1
XS GIS Cut Line= 2
2343162.62891714672357.1364716242343692.74793145672453.521746955
#Sta/Elev= 30
       0  2823.6    38.2  2810.7    54.4  2804.1    66.6 2802.41      77 2798.66
    82.9 2797.57   131.7 2797.05   142.4 2797.86   164.2 2796.86   176.4 2794.41
   188.6 2793.35   228.4  2791.7   242.2 2788.78   257.7 2788.18   286.2 2784.49
   290.1 2784.44   321.3 2784.99   330.9  2786.8   341.9 2794.02   355.3 2798.45
   363.4 2804.65   375.6  2811.3   391.9 2822.06     400 2826.48   444.7 2852.73
     461 2858.53   505.7 2881.06   513.7 2886.01   530.1 2899.19   538.8 2902.48
#Mann= 5 ,-1,0
       0      .1       0   286.2    .045       0   321.3      .1       0
     400     .06       0     500      .1       0
Bank Sta=286.2,321.3
XS Rating Curve= 0 ,0
Exp/Cntr(USF)=0,0
Exp/Cntr=0.3,0.1

Type RM Length L Ch R = 1 ,127633  ,287.1,277.5,272.9
XS GIS Cut Line= 2
2343068.12612912672426.7619208192343573.46026066  672669.0373106
#Sta/Elev= 30
       0 2858.62     4.8 2853.99     8.9 2851.44    22.2 2849.91    26.7  2847.9
    37.8 2839.31    61.8 2827.22    67.8 2823.16    79.9 2820.43    97.6 2810.18
   124.3 2802.03     142 2799.13   186.4 2798.21   204.1 2796.04   226.3 2791.76
   256.7 2791.49   274.7 2787.54   329.4 2785.02   346.7 2784.57   354.9 2785.11
   361.7 2787.17   377.1 2788.71   409.6 2787.06   421.5 2791.04   439.2 2794.06
   477.5 2806.63   510.2 2822.31   536.8 2830.86   545.7 2834.63   560.4 2838.64
#Mann= 5 ,-1,0
       0      .1       0     320     .06       0   329.4    .045       0
   354.9     .06       0     520      .1       0
Bank Sta=329.4,354.9
XS Rating Curve= 0 ,0
Exp/Cntr=0.3,0.1

Type RM Length L Ch R = 1 ,127355  ,226.7,219.5,217.1
XS GIS Cut Line= 2
2342861.38354666 672803.521787982343587.31685717672835.481116116
#Sta/Elev= 30
       0 2915.11    66.9 2918.55   130.9 2914.53   162.9 2907.04     195 2902.03
     203 2898.79   256.7 2862.38     259 2860.56     267 2848.75   271.1 2844.11
   284.2  2833.6   319.5 2813.24   347.1 2799.07   363.1 2789.23   383.2 2784.03
   406.9 2783.72   418.4  2783.8   427.2 2784.54   435.2 2786.85   467.2 2788.59
   503.3 2788.39   531.3  2792.5   547.3 2792.07   566.6 2794.46   591.4  2800.9
   627.4 2814.81   635.4 2816.76   663.4 2828.45   691.5 2834.89   726.6 2844.78
#Mann= 5 ,-1,0
       0      .1       0   383.2    .045       0   418.4      .1       0
     600     .06       0     700      .1       0
Bank Sta=383.2,418.4
XS Rating Curve= 0 ,0
Exp/Cntr(USF)=0,0
Exp/Cntr=0.3,0.1

Type RM Length L Ch R = 1 ,127136  ,160.2,164.1,166.7
XS GIS Cut Line= 3
     2342891.017673136.894511862 2343394.4291469673014.034127965
2343604.61774886672979.784317517
#Sta/Elev= 30
       0 2816.76    34.1 2820.96    46.5 2820.69    54.7 2822.76    71.2 2822.47
   137.1 2826.88   165.9 2826.72   207.1 2828.72   305.9 2827.33   322.3 2825.24
   338.8 2820.82   354.9 2814.54   371.8 2802.67   383.2 2792.83   396.5 2784.42
   425.3 2783.27     454 2783.22   464.1 2783.49   507.6 2790.66     520 2791.97
   536.2 2791.58   560.5 2794.75   568.6 2794.17   584.8  2797.9     597 2797.41
     623 2801.62   665.9 2815.53     678 2821.25   718.5 2833.93   731.1 2836.21
#Mann= 5 ,-1,0
       0      .1       0   425.3    .045       0   464.1      .1       0
  588.19     .06       0  678.19      .1       0
Bank Sta=425.3,464.1
XS Rating Curve= 0 ,0
Exp/Cntr=0.3,0.1

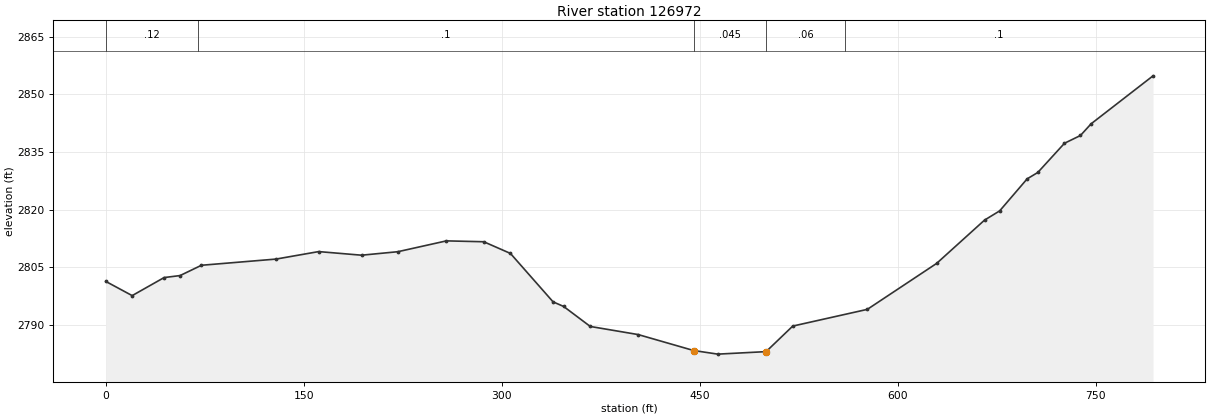
Type RM Length L Ch R = 1 ,126972  ,308.6,309.7,311.9
XS GIS Cut Line= 2
2342900.37869475673251.4285303712343686.67962508673144.897436585
#Sta/Elev= 30
       0 2801.31      20 2797.61    44.2 2802.31    56.3 2802.83    72.5 2805.51
     129 2807.12   161.3 2809.07   193.8 2808.13   221.3 2809.04   258.1 2811.86
   286.4 2811.63   306.6 2808.59   338.9 2795.99   346.9 2794.79   367.1 2789.58
   403.4 2787.47   445.4 2783.32   463.7 2782.38   500.3 2783.03   520.5 2789.68
     577 2794.03   629.5 2805.99   665.8 2817.26   677.3 2819.67   698.1    2828
   706.2 2829.67   726.4 2837.27   738.5 2839.29   746.6 2842.34   793.5 2854.82
#Mann= 5 ,-1,0
       0     .12       0      70      .1       0   445.4    .045       0
   500.3     .06       0     560      .1       0
Bank Sta=445.4,500.3
XS Rating Curve= 0 ,0
Exp/Cntr(USF)=0,0
Exp/Cntr=0.3,0.1