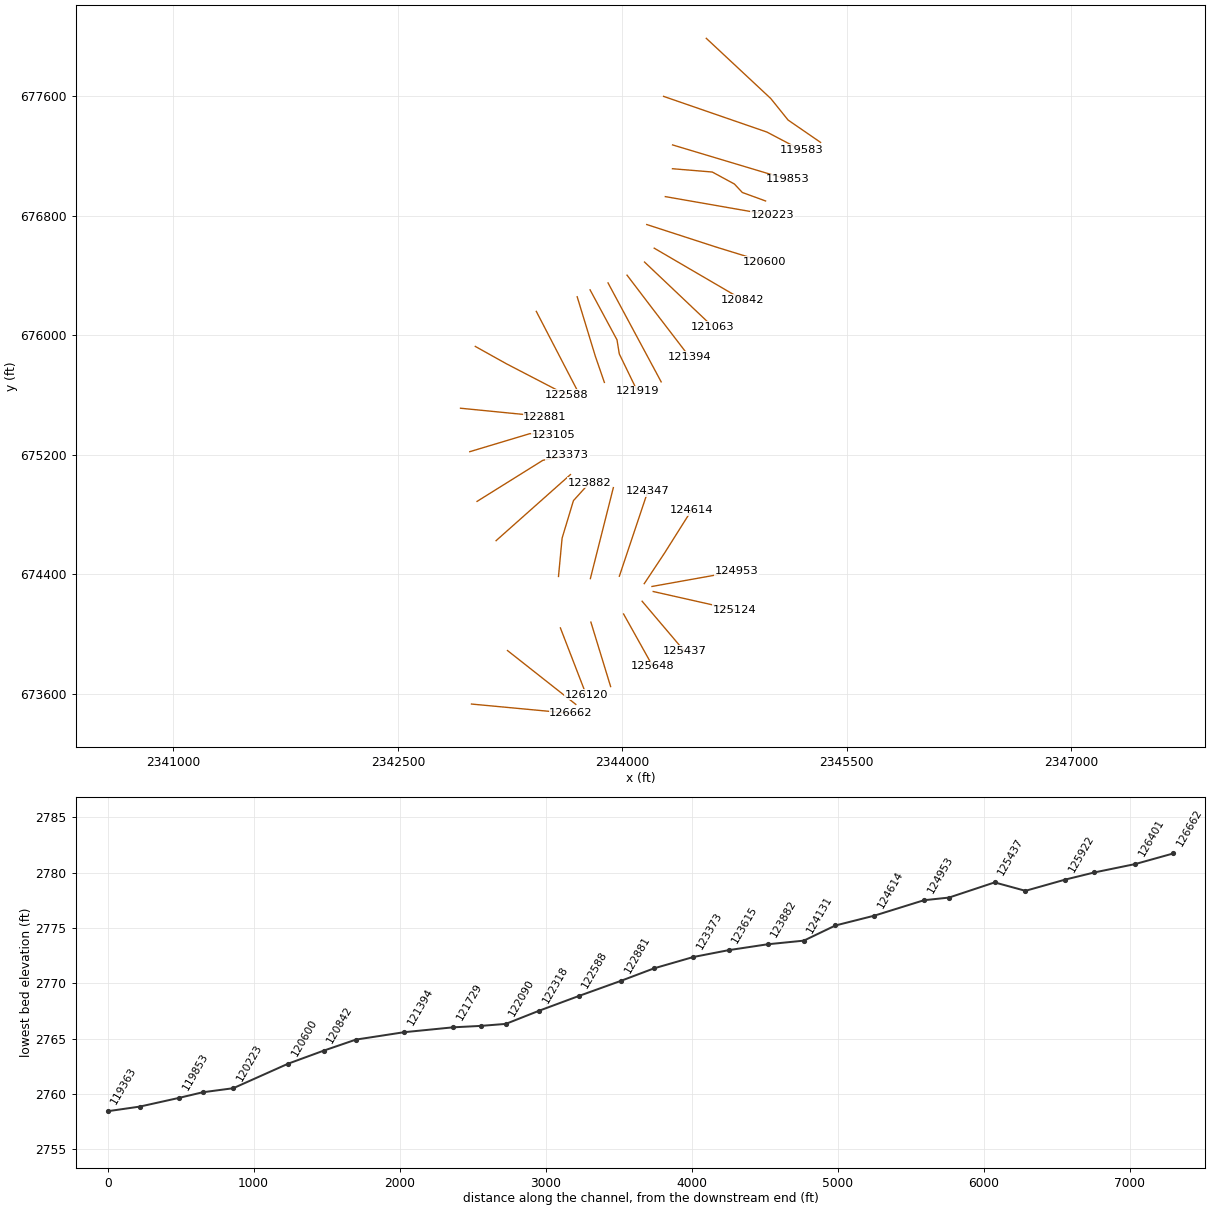
HEC-RAS study GLADYFK.prj: GLADYFK

--- GLADYFK.g01 (geometry) --- (continued)

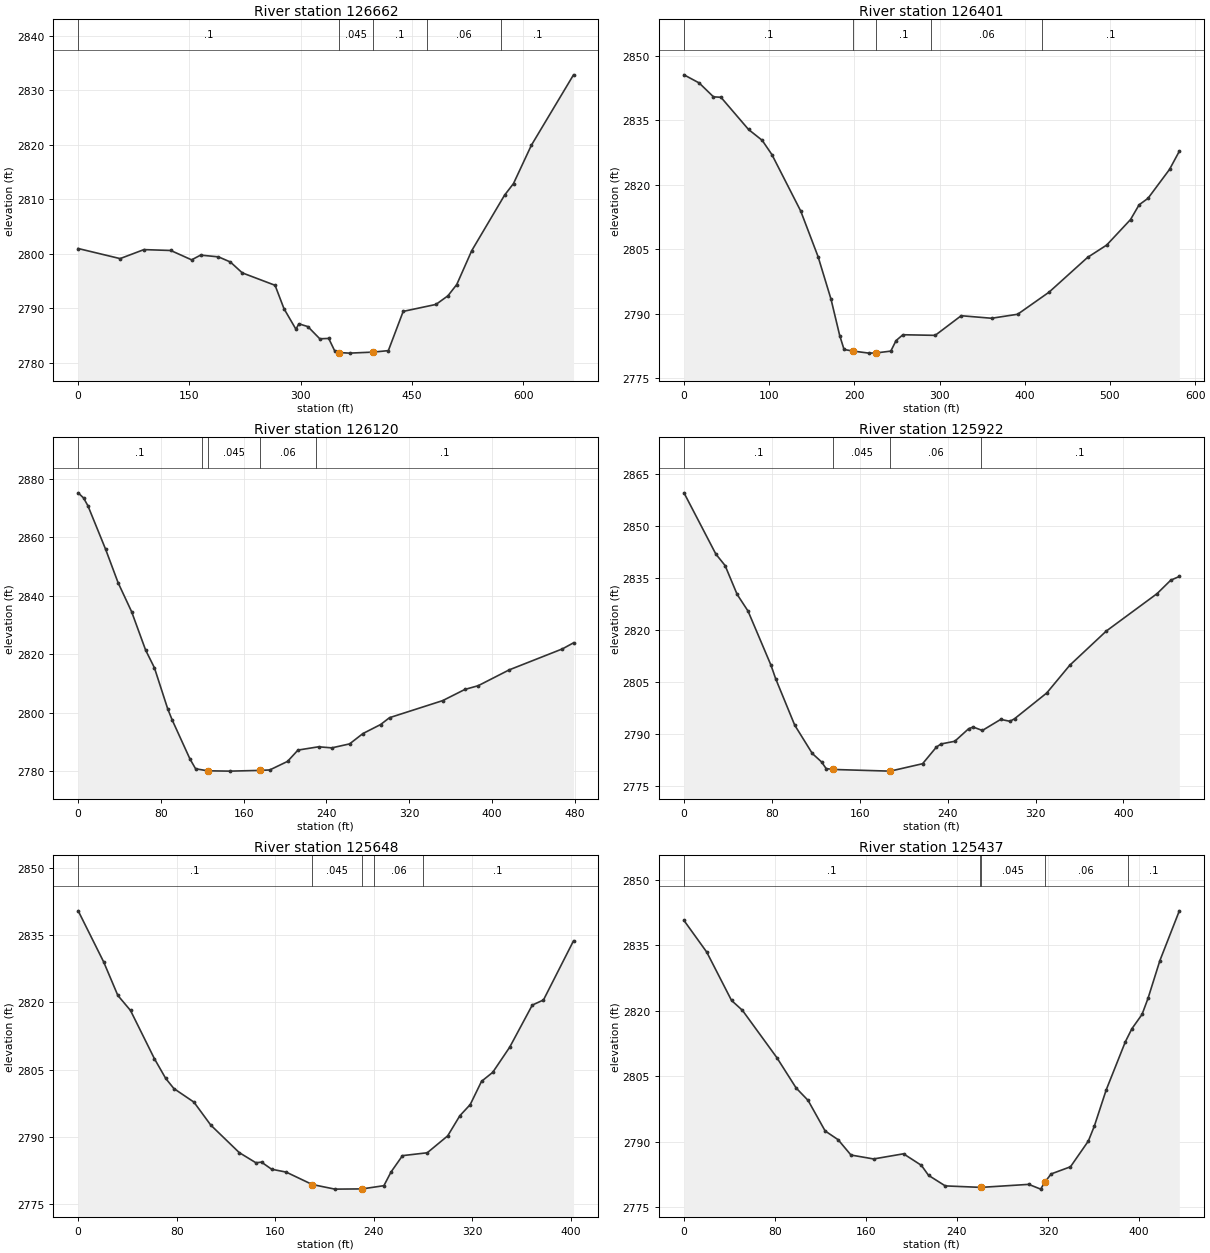
Type RM Length L Ch R = 1 ,126662  ,273.4,261,258
XS GIS Cut Line= 2
2342991.94665809673532.6578487132343656.69928915673470.262816949
#Sta/Elev= 30
       0 2800.94    56.5 2799.09    88.6 2800.74   124.8 2800.58   152.9 2798.86
     165 2799.73   189.1 2799.41   205.1 2798.47   221.2 2796.47   265.4 2794.19
   277.4  2789.9   293.5 2786.13   297.5 2787.12   309.6 2786.61   325.7 2784.37
   337.7 2784.44   345.7 2782.17   351.1 2781.85   365.8 2781.74     398 2781.93
   418.1  2782.2   438.1  2789.4   482.3 2790.68   498.4 2792.26   510.3 2794.33
   530.5 2800.55   574.7 2810.72   586.8 2812.87   610.9  2819.9   667.7 2832.82
#Mann= 5 ,-1,0
       0      .1       0   351.1    .045       0     398      .1       0
     470     .06       0     570      .1       0
Bank Sta=351.1,398
XS Rating Curve= 0 ,0
Exp/Cntr=0.3,0.1

Type RM Length L Ch R = 1 ,126401  ,293.3,280.6,275.5
XS GIS Cut Line= 2
2343232.65424918673890.6150930892343689.21607969673530.438537907
#Sta/Elev= 30
       0 2845.58    17.8 2843.69    34.6 2840.46    43.4 2840.35    75.8 2832.85
    91.8 2830.33   103.2 2827.01     137 2813.88   157.4 2803.25   172.6 2793.34
   182.8 2784.88   187.9 2781.63   198.1 2781.27   217.1 2780.78   225.7 2780.83
   242.8 2781.25     249 2783.71     257 2785.06   294.9 2784.92   325.4 2789.49
   361.1  2788.9   391.7 2789.83   428.6 2794.98   473.8 2803.07   496.2 2805.94
   524.2 2811.88   534.3 2815.32   544.7 2816.82     570 2823.56   581.5  2827.8
#Mann= 5 ,-1,0
       0      .1       0   198.1    .045       0   225.7      .1       0
     290     .06       0     420      .1       0
Bank Sta=198.1,225.7
XS Rating Curve= 0 ,0
Exp/Cntr(USF)=0,0
Exp/Cntr=0.3,0.1

Type RM Length L Ch R = 1 ,126120  ,200.5,198,197.3
XS GIS Cut Line= 2
 2343586.2673839674041.9743364482343758.69466355673595.179549724
#Sta/Elev= 30
       0 2875.26     5.2  2873.5     9.4 2870.84    26.6 2855.87    38.6 2844.49
    51.6 2834.63    65.2 2821.44    73.7 2815.39    86.6 2801.29    90.9 2797.51
     108 2784.23   113.5 2780.83   125.2 2780.13   146.6 2780.02   175.3 2780.26
   185.2 2780.42   202.4 2783.35   212.5 2787.22   232.4 2788.35   245.2 2787.98
   262.4 2789.34   275.3 2792.88   292.4 2795.97     301 2798.31   352.4 2804.15
   373.9 2807.98   386.7 2809.25   416.7 2814.67   468.2 2821.86   478.9 2823.93
#Mann= 5 ,-1,0
       0      .1       0     120     .06       0   125.2    .045       0
   175.3     .06       0     230      .1       0
Bank Sta=125.2,175.3
XS Rating Curve= 0 ,0
Exp/Cntr=0.3,0.1

Type RM Length L Ch R = 1 ,125922  ,273.6,273.9,279.5
XS GIS Cut Line= 2
2343790.01953931674080.9075132582343921.91517924673649.710228884
#Sta/Elev= 30
       0 2859.66      29    2842    37.4 2838.69    48.4 2830.35    58.3 2825.55
    79.2 2809.92    83.4 2806.08   100.8 2792.64   116.8 2784.47   125.2 2782.04
   129.4 2780.11     136 2779.86   187.3 2779.38   187.9 2779.39   217.2 2781.52
   229.8 2786.33     234 2787.22   246.5 2787.99   259.1 2791.61   263.2  2792.1
   271.6 2791.11   288.3  2794.3   296.7 2793.76   300.9 2794.49   330.2 2801.92
   351.1  2809.9   384.5 2819.81   430.6 2830.57   443.1 2834.46   450.9 2835.53
#Mann= 4 ,-1,0
       0      .1       0     136    .045       0   187.9     .06       0
     270      .1       0
Bank Sta=136,187.9
XS Rating Curve= 0 ,0
Exp/Cntr(USF)=0,0
Exp/Cntr=0.3,0.1

Type RM Length L Ch R = 1 ,125648  ,207.4,211.1,221.8
XS GIS Cut Line= 2
2344008.47202348674135.2298957592344204.47397628673783.879004794
#Sta/Elev= 30
       0 2840.44    20.7 2829.04    32.2 2821.57    42.5 2818.21    61.9 2807.46
    71.1 2803.05    77.7  2800.8      94 2797.77   107.7 2792.64   130.8 2786.51
   144.3 2784.25   148.9 2784.38   157.1  2782.8   168.9 2782.16   190.1 2779.39
   208.5 2778.36   230.6 2778.41   248.3 2779.13   254.1 2782.19   263.4 2785.83
   283.5 2786.47   300.1 2790.24     310 2794.74   318.4 2797.22   327.6 2802.41
   336.7 2804.42   350.5 2810.04   368.8 2819.41   377.9 2820.56   402.3 2833.75
#Mann= 5 ,-1,0
       0      .1       0   190.1    .045       0   230.6      .1       0
     240     .06       0     280      .1       0
Bank Sta=190.1,230.6
XS Rating Curve= 0 ,0
Exp/Cntr=0.3,0.1

Type RM Length L Ch R = 1 ,125437  ,302.6,312.8,337
XS GIS Cut Line= 2
 2344132.4409122674220.4125170252344413.98737435673888.136962597
#Sta/Elev= 30
       0 2840.64      20  2833.4    41.8 2822.33    51.4 2820.06    81.6 2809.25
    98.6 2802.28   109.1 2799.44   124.1 2792.44   135.5 2790.44   146.8 2786.93
   166.7 2786.03     193 2787.21   208.7 2784.57     215 2782.28   229.7 2779.86
   261.1 2779.52   303.1 2780.21   313.6 2779.12   317.1 2780.66   322.8  2782.6
   339.8 2784.24   355.5 2790.13   360.8 2793.57   371.2 2801.84   388.1  2812.9
   393.8 2815.86   402.7 2819.12     408 2822.83   418.4 2831.45   435.5 2842.85
#Mann= 5 ,-1,0
       0      .1       0     260     .06       0   261.1    .045       0
   317.1     .06       0     390      .1       0
Bank Sta=261.1,317.1
XS Rating Curve= 0 ,0
Exp/Cntr(USF)=0,0
Exp/Cntr=0.3,0.1

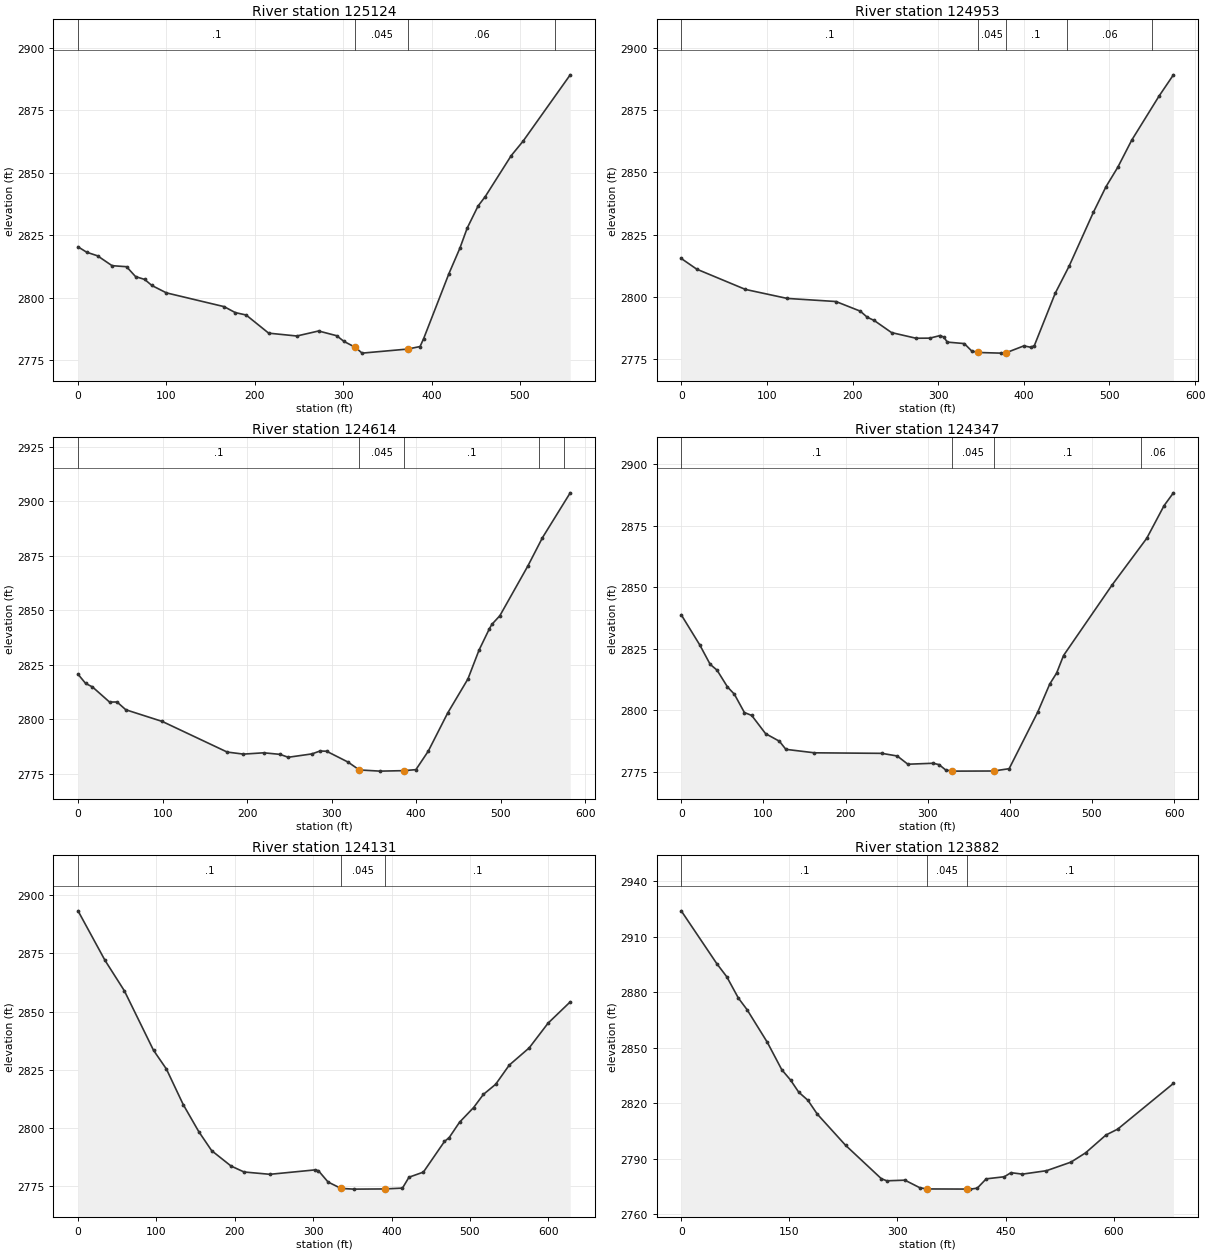
Type RM Length L Ch R = 1 ,125124  ,167.6,171.4,184.1
XS GIS Cut Line= 2
2344206.64412402674285.5240163222344749.93542437674163.076902069
#Sta/Elev= 30
       0 2820.33     9.8 2818.17    22.1 2816.73    38.5 2812.78    54.9 2812.37
    65.1 2808.41    75.4 2807.27    83.6 2804.84     100 2801.89   165.3 2796.37
   177.9 2793.99   190.2 2793.02   215.7 2785.75   247.6 2784.61   272.2 2786.62
   292.7 2784.72   300.9 2782.45   313.9 2780.04   321.4 2777.75     373 2779.38
     387 2780.39   391.1  2783.6   419.7 2809.63   432.1 2819.82   440.3 2827.81
   452.6 2836.67   460.8 2840.48   490.1 2856.85   503.5 2862.63   556.9 2889.23
#Mann= 4 ,-1,0
       0      .1       0   313.9    .045       0     373     .06       0
     540      .1       0
Bank Sta=313.9,373
XS Rating Curve= 0 ,0
Exp/Cntr=0.3,0.1

Type RM Length L Ch R = 1 ,124953  ,328.4,338.6,360.3
XS GIS Cut Line= 2
2344198.38873216 674319.334246972344764.01811107674420.792431528
#Sta/Elev= 30
       0 2815.46    18.1 2811.17      75 2803.04   123.7 2799.44   180.6  2798.2
   209.1 2794.33   217.2 2791.89   225.3  2790.6   245.6 2785.74   274.1 2783.48
   290.3 2783.52   302.5 2784.57   306.6  2783.9   310.7 2781.93   330.5 2781.34
   339.1 2778.39   346.6 2777.77   372.9 2777.51   378.7 2777.58   400.1 2780.42
   408.2 2779.85   412.3 2780.53   436.6 2801.46   452.9 2812.38   481.3 2834.01
   495.9 2844.19   509.7    2852     526 2862.88   557.9 2880.55   574.7 2889.07
#Mann= 5 ,-1,0
       0      .1       0   346.6    .045       0   378.7      .1       0
     450     .06       0     550      .1       0
Bank Sta=346.6,378.7
XS Rating Curve= 0 ,0
Exp/Cntr(USF)=0,0
Exp/Cntr=0.3,0.1

Type RM Length L Ch R = 1 ,124614  ,262.4,267.4,274.4
XS GIS Cut Line= 3
2344146.71756689674338.1084428742344282.22337759674542.558836782
2344461.60983678674827.584836782
#Sta/Elev= 30
       0  2820.6       9 2816.37    17.1 2814.76    37.3 2807.82    46.1 2807.86
    56.5 2804.29    99.7 2798.91   176.4 2784.87   195.6 2783.93   219.7 2784.53
   238.8 2783.82   248.6 2782.48   276.7 2784.03   286.2 2785.36     294 2785.25
   319.3 2780.28   332.7 2776.66   357.1 2776.12   385.4 2776.34   399.6  2776.8
   414.2 2785.28   437.1 2802.74   461.1 2818.41   474.2 2831.62   486.4  2841.4
   489.4 2843.46   498.9 2847.47     532 2870.28   549.3  2883.3   582.1 2903.86
#Mann= 5 ,-1,0
       0      .1       0   332.7    .045       0   385.4      .1       0
  545.28     .06       0  575.28      .1       0
Bank Sta=332.7,385.4
XS Rating Curve= 0 ,0
Exp/Cntr=0.3,0.1

Type RM Length L Ch R = 1 ,124347  ,216.3,216.6,218.7
XS GIS Cut Line= 2
2343980.25363536674387.8185215472344170.48773141674955.984355074
#Sta/Elev= 30
       0 2838.82    22.5 2826.59    35.2 2818.68    43.6 2816.29    56.3 2809.47
    64.7 2806.51    76.9 2799.06    85.8 2797.88   102.7 2790.47   119.5 2787.39
   127.4 2784.09   162.2 2782.68   244.3 2782.46     263 2781.38   275.9 2778.04
   306.7 2778.43   313.9 2777.87     322 2775.69   329.7 2775.25   330.5 2775.23
   380.2 2775.28   399.2 2776.22     434 2799.24   448.6 2810.63     457 2815.12
   465.4 2822.24   524.5 2850.92   566.7 2869.91   587.8  2883.2   599.2 2888.41
#Mann= 4 ,-1,0
       0      .1       0   329.7    .045       0   380.2      .1       0
     560     .06       0
Bank Sta=329.7,380.2
XS Rating Curve= 0 ,0
Exp/Cntr(USF)=0,0
Exp/Cntr=0.3,0.1

Type RM Length L Ch R = 1 ,124131  ,248.4,248.4,246
XS GIS Cut Line= 2
2343786.50965253674371.8566735072343940.21490425 674980.69523069
#Sta/Elev= 30
       0  2893.3    34.4 2872.05    59.1 2858.99    96.3 2833.45   112.8 2825.38
   134.2 2810.15     154 2798.56   170.5 2790.37   195.3 2783.75   211.8 2781.22
   244.8 2780.22   302.5 2782.12   306.7 2781.76     319 2776.91   335.5 2774.16
     352 2773.86   391.1 2773.94   413.9  2774.3   422.2 2778.97   440.6 2781.17
   467.5 2794.33   473.5 2795.98   486.7 2802.57   504.7 2808.89   517.1  2814.5
   532.8 2818.86   550.1 2827.08   575.6 2834.49   599.6 2845.08   627.9 2854.22
#Mann= 3 ,-1,0
       0      .1       0   335.5    .045       0   391.1      .1       0
Bank Sta=335.5,391.1
XS Rating Curve= 0 ,0
Exp/Cntr=0.3,0.1

Type RM Length L Ch R = 1 ,123882  ,280.2,266.6,261.9
XS GIS Cut Line= 4
2343573.50731473 674386.246192292343597.69766964674642.805386103
 2343673.4254864674893.548601585 2343782.8821609675014.577537738
#Sta/Elev= 30
       0 2924.05    49.2 2895.56    63.2 2888.37    79.3 2876.84    91.3 2870.61
   119.5 2852.89   139.5  2838.1   151.6 2832.56     163 2825.96   175.7 2821.59
   188.7 2814.13   227.9 2797.28   277.6 2779.17   285.2 2778.03   310.3 2778.38
   331.2 2774.24   341.4 2773.63   396.4 2773.56   401.2 2773.53   410.6 2774.04
   423.1 2779.09   448.2 2780.22   457.4 2782.43   473.3 2781.64   506.7  2783.5
   540.7 2788.14     561 2793.17   589.2  2802.8   605.4 2805.96   682.8 2830.71
#Mann= 3 ,-1,0
       0      .1       0   341.4    .045       0   396.4      .1       0
Bank Sta=341.4,396.4
XS Rating Curve= 0 ,0
Exp/Cntr(USF)=0,0
Exp/Cntr=0.3,0.1

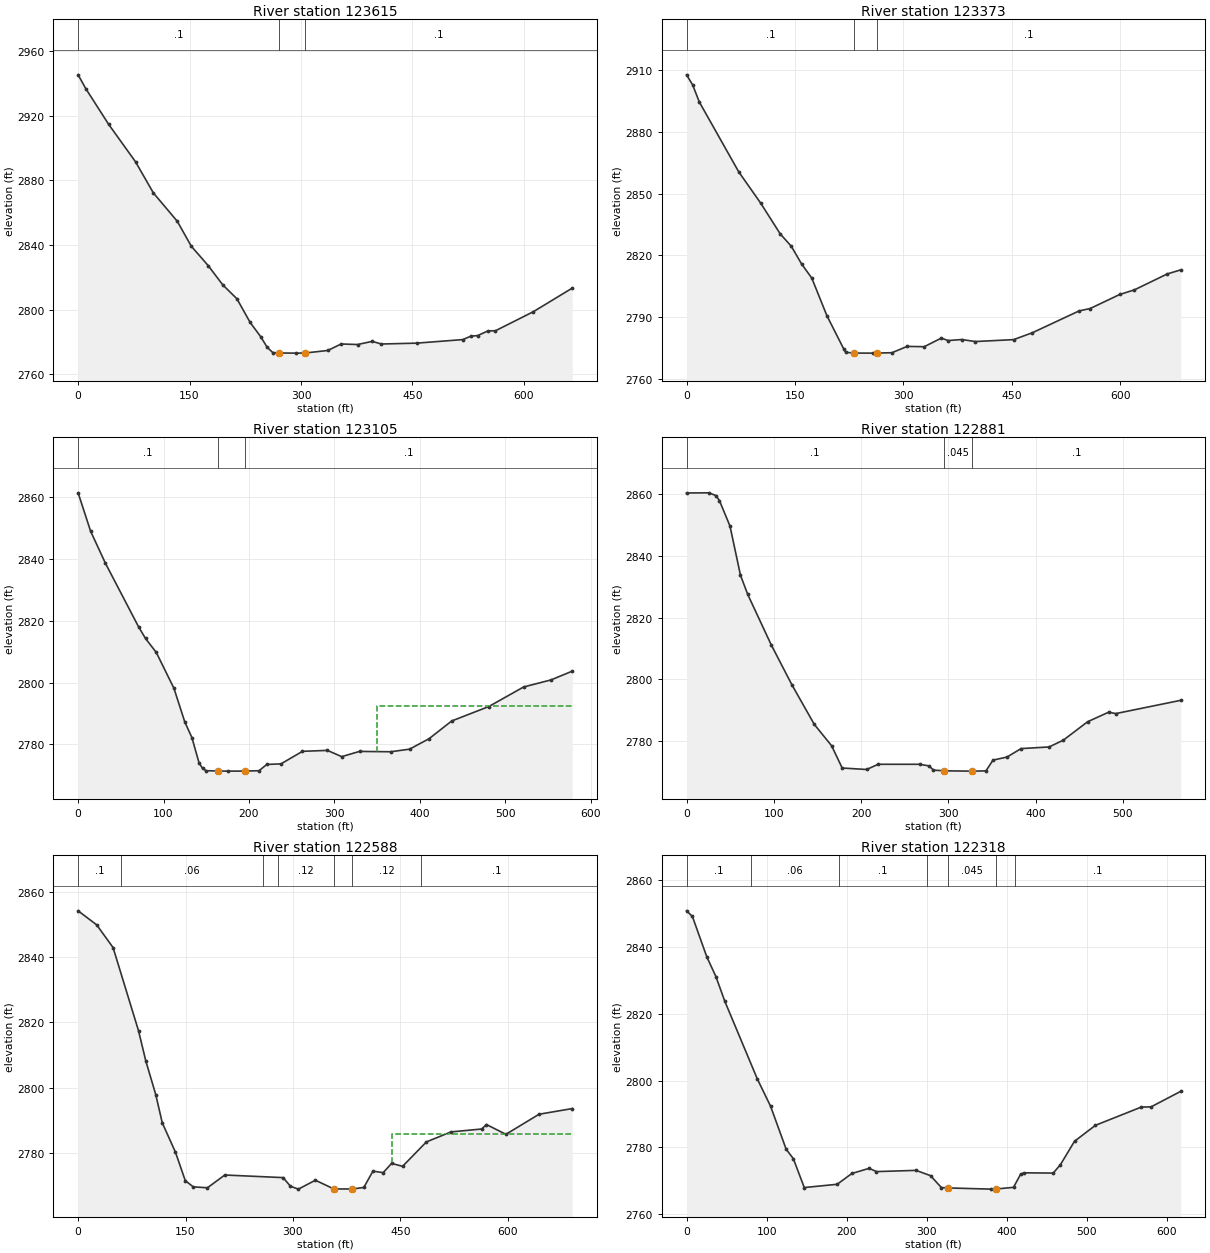
Type RM Length L Ch R = 1 ,123615  ,246.1,242.1,240.3
XS GIS Cut Line= 2
2343156.49901632674625.8216550572343653.46099782675067.977440689
#Sta/Elev= 30
       0 2945.46    10.3 2936.91    41.2 2914.71    77.3 2891.55   101.3 2872.27
   133.4 2854.76   152.3 2839.28     175 2827.28   194.8 2815.24   213.7 2806.73
   231.6 2791.99   245.9  2783.1   254.3 2776.74   261.9 2773.37   269.8 2773.09
   293.9    2773   305.9 2773.09     336 2774.64   354.1 2778.67   376.1 2778.33
   395.8 2780.27   408.2 2778.65   455.5 2779.18   517.8 2781.39   528.6  2783.5
   537.9 2783.88   551.8  2786.8   561.7 2786.84   612.8 2798.68   665.2 2813.31
#Mann= 3 ,-1,0
       0      .1       0   269.8    .045       0   305.9      .1       0
Bank Sta=269.8,305.9
XS Rating Curve= 0 ,0
Exp/Cntr=0.3,0.1

Type RM Length L Ch R = 1 ,123373  ,273.8,268.1,265.7
XS GIS Cut Line= 3
2343029.22129621674888.4880486232343468.97654012675163.269362611
2343630.90468608675196.227606275
#Sta/Elev= 30
       0 2907.78     8.5 2902.86    17.6 2894.62    72.3 2860.53   102.5 2845.42
   129.6 2830.42     145 2824.35   159.1 2815.82   173.3 2808.89   194.2 2790.62
   217.5 2774.42   220.4 2772.77     232 2772.41     258 2772.38   262.9 2772.41
   284.2 2772.58   305.3 2775.65   328.9 2775.51   352.5 2779.68     362 2778.51
   380.8 2778.99   399.7 2778.02   452.6 2778.95   478.7 2782.32   543.2 2792.92
   558.5 2794.08   599.4 2800.91   619.8 2803.17   665.3 2810.92   683.8 2812.88
#Mann= 3 ,-1,0
       0      .1       0     232    .045       0   262.9      .1       0
Bank Sta=232,262.9
XS Rating Curve= 0 ,0
Exp/Cntr(USF)=0,0
Exp/Cntr=0.3,0.1

Type RM Length L Ch R = 1 ,123105  ,236,224.8,223.9
XS GIS Cut Line= 3
 2342980.5937917 675220.975246362343382.87002787675341.883091222
2343541.03665103675331.253791667
#Sta/Elev= 30
       0 2861.42    14.6 2849.01    31.9 2838.67    70.7  2818.1    78.9 2814.29
    91.5 2809.77   112.2 2798.16   124.9 2787.27   133.2 2782.23   141.6 2774.01
   145.7 2772.24   149.9 2771.49   163.6 2771.42     175 2771.36   195.3 2771.38
   211.8 2771.49   220.9 2773.52   237.5 2773.71   262.7 2777.77   291.9 2778.07
   308.6 2776.05   329.5 2777.74   365.9 2777.63     388 2778.46   410.9 2781.85
   437.4 2787.59   480.9 2792.27   521.6 2798.59   553.7 2800.88   578.6 2803.72
#Mann= 3 ,-1,0
       0      .1       0   163.6    .045       0   195.3      .1       0
#XS Ineff= 2 , 0
                          349.69         2792.41
Permanent Ineff=
       F       F
Bank Sta=163.6,195.3
XS Rating Curve= 0 ,0
Exp/Cntr=0.3,0.1

Type RM Length L Ch R = 1 ,122881  ,297,292.8,285.5
XS GIS Cut Line= 2
2342918.65868375675511.7852054242343482.31526463675456.115419658
#Sta/Elev= 30
       0 2860.36    25.7 2860.41    33.7 2859.52    37.7 2857.91    49.8 2849.64
    61.8 2833.74    70.1 2827.52    96.9 2811.25   120.8 2798.19   146.4  2785.4
   166.3 2778.45   178.4 2771.25   206.5 2770.77   219.6 2772.46   267.2 2772.46
   278.1 2771.92   282.9 2770.57   294.9 2770.34   325.7 2770.24   327.1 2770.24
   343.2 2770.31   351.2  2773.8   367.3  2774.8   383.4 2777.54   415.5 2778.07
   431.8 2780.26   459.7 2786.24   483.9 2789.35   491.9 2788.88   566.4 2793.18
#Mann= 3 ,-1,0
       0      .1       0   294.9    .045       0   327.1      .1       0
Bank Sta=294.9,327.1
XS Rating Curve= 0 ,0
Exp/Cntr(USF)=0,0
Exp/Cntr=0.3,0.1

Type RM Length L Ch R = 1 ,122588  ,281.1,269.7,271.8
XS GIS Cut Line= 3
     2343017.537      675925.2232343225.76327936675808.984445103
2343626.47158755675600.873165745
#Sta/Elev= 30
       0 2854.21    25.9 2849.91    48.8 2842.94    84.3 2817.45    94.6 2808.08
   108.4 2797.84   117.5 2789.18   135.9 2780.18   149.6 2771.47   160.7 2769.55
   180.6 2769.27   204.8 2773.18   286.3 2772.38   296.5 2769.72   307.5 2768.85
   331.3 2771.58   357.1  2768.9   382.5  2768.9   398.9 2769.35   411.6 2774.37
     426 2773.91   437.7 2776.75     453 2775.84   486.3 2783.33   520.6  2786.4
   563.5 2787.29   570.2 2788.66   597.3 2785.66   643.6 2791.82     690 2793.56
#Mann= 7 ,-1,0
       0      .1       0      60     .06       0  258.47      .1       0
  278.47     .12       0   357.1    .045       0   382.5     .12       0
  478.47      .1       0
#XS Ineff= 2 , 0
                          438.04         2785.63
Permanent Ineff=
       F       F
Bank Sta=357.1,382.5
XS Rating Curve= 0 ,0
Exp/Cntr=0.3,0.1

Type RM Length L Ch R = 1 ,122318  ,231.2,228.3,220.1
XS GIS Cut Line= 2
2343425.13543593676159.6458166372343709.21835269675611.771620022
#Sta/Elev= 30
       0 2850.89     7.3 2849.22    25.3 2837.11    36.7 2831.19    47.8  2823.8
    88.4 2800.53     105 2792.33   124.4 2779.48   133.4 2776.64     147    2768
   188.1 2768.98   206.5 2772.22   228.1 2773.76   237.1 2772.78   286.6 2773.15
   304.7 2771.56   318.2    2768   326.2 2767.89   380.3 2767.53   386.9 2767.58
   408.3 2768.06   417.3 2772.05   421.8 2772.41   457.9 2772.34   466.9 2774.85
   484.5 2781.87   510.6 2786.64   567.9 2792.11   580.1 2792.17   617.1 2796.82
#Mann= 7 ,-1,0
       0      .1       0      80     .06       0     190      .1       0
     300     .12       0   326.2    .045       0   386.9     .12       0
     410      .1       0
Bank Sta=326.2,386.9
XS Rating Curve= 0 ,0
Exp/Cntr(USF)=0,0
Exp/Cntr=0.3,0.1

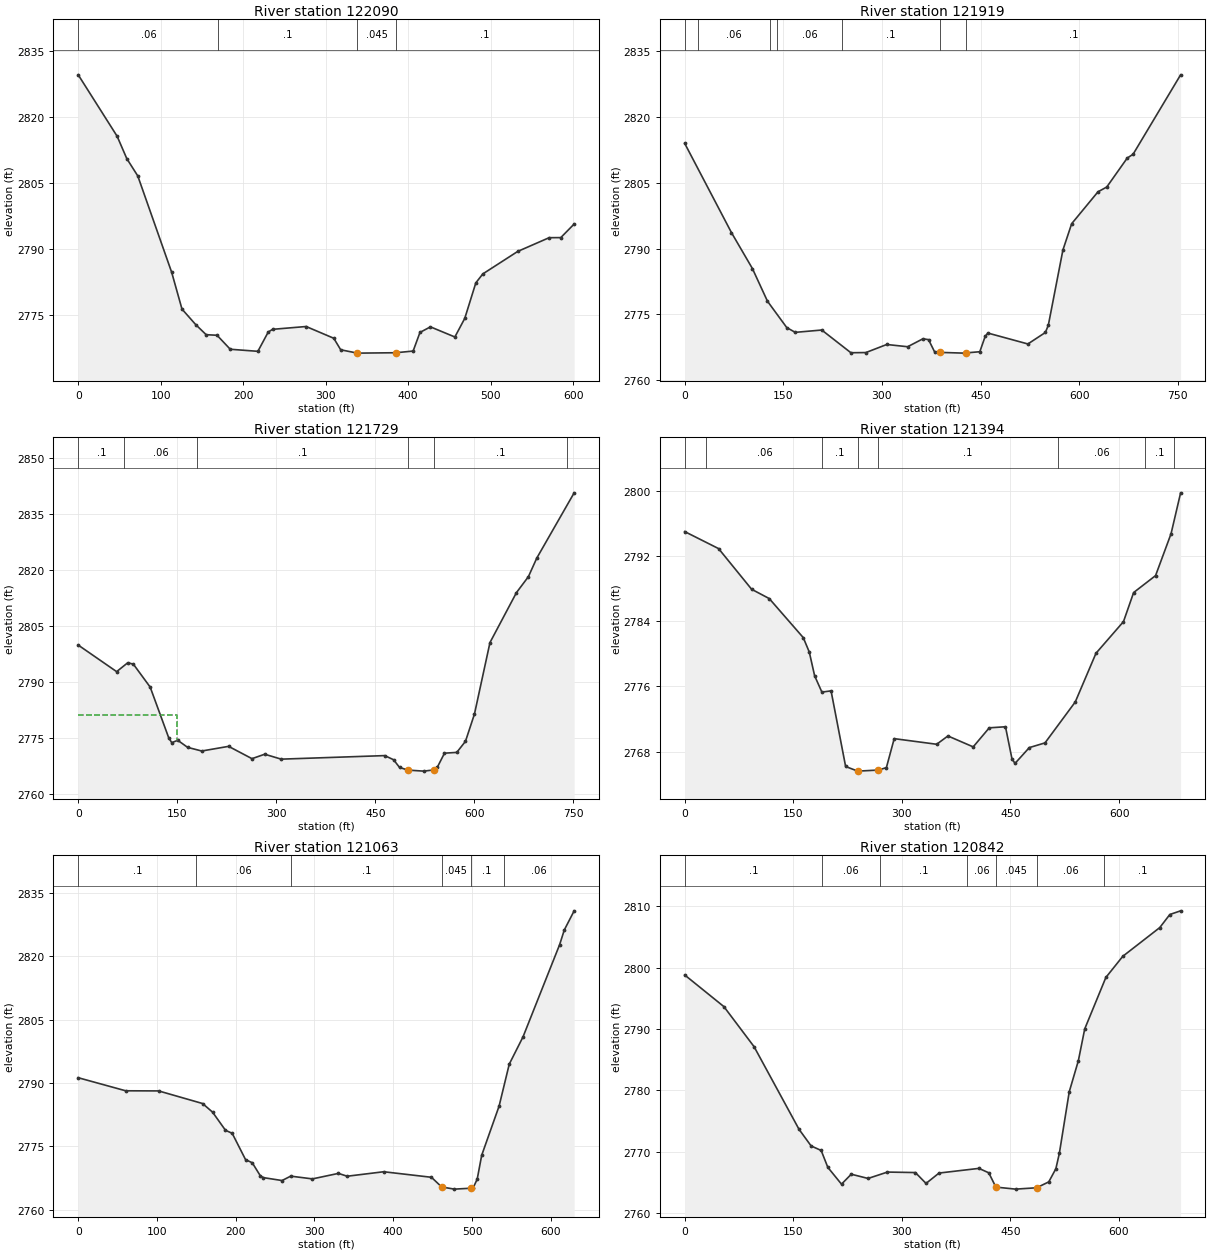
Type RM Length L Ch R = 1 ,122090  ,172.2,170.2,166.1
XS GIS Cut Line= 3
2343698.40743391676257.5058778332343819.61073565675860.047528701
2343880.12100265675684.553191936
#Sta/Elev= 30
       0  2829.6    47.2 2815.63    58.9 2810.55    72.2 2806.62   113.3 2784.71
   125.8 2776.35   142.5 2772.81   155.1 2770.53   168.3  2770.4   184.3 2767.22
   217.8 2766.75   230.3 2771.12   235.6 2771.75   276.3 2772.39   309.8 2769.72
   318.2  2767.1   338.2 2766.35   339.1 2766.34   385.1 2766.43     406 2766.81
   414.3 2771.05     427 2772.31   456.6 2770.01   468.6 2774.24     482 2782.31
   490.5 2784.35   532.8 2789.46   570.9 2792.58     585  2792.6   601.2 2795.69
#Mann= 4 ,-1,0
       0     .06       0     170      .1       0   338.2    .045       0
   385.1      .1       0
Bank Sta=338.2,385.1
XS Rating Curve= 0 ,0
Exp/Cntr=0.3,0.1

Type RM Length L Ch R = 1 ,121919  ,188.7,190.5,201.3
XS GIS Cut Line= 4
2343784.51595708676303.8548838922343964.60423467675969.042874849
2343979.82296236675875.1940541332344101.57278383675624.085047351
#Sta/Elev= 30
       0 2814.02    71.2 2793.64     103 2785.46   125.9 2778.01   155.3 2771.98
   168.2  2770.9   208.5 2771.43   252.8 2766.25   275.6 2766.29   307.3 2768.13
   339.1 2767.62   362.4 2769.43   370.9 2769.24     380 2766.48   388.1 2766.33
   424.6 2766.16   428.5 2766.22   448.9 2766.48     457 2769.96   461.1 2770.74
     522 2768.25   548.6 2770.87   553.1 2772.53   575.3  2789.7   588.6 2795.69
   628.6 2802.96     642 2804.06   673.1 2810.66     682 2811.53   754.3 2829.65
#Mann= 7 ,-1,0
       0      .1       0      20     .06       0     130      .1       0
     140     .06       0     240      .1       0   388.1    .045       0
   428.5      .1       0
Bank Sta=388.1,428.5
XS Rating Curve= 0 ,0
Exp/Cntr(USF)=0,0
Exp/Cntr=0.3,0.1

Type RM Length L Ch R = 1 ,121729  ,330.6,335.1,345.8
XS GIS Cut Line= 2
2343904.66044415676350.0716641182344259.82110859675688.165633028
#Sta/Elev= 30
       0 2799.81    58.2 2792.69    75.1 2795.08    83.6 2794.68     109 2788.55
   137.2 2774.91   141.7 2773.66   150.8 2774.29   165.7  2772.4   187.1 2771.42
   227.8 2772.67   263.2 2769.37   282.5 2770.56   307.5 2769.24   464.3 2770.19
   477.7 2769.08   486.7 2767.02   499.6  2766.3   523.5 2766.03   538.62766.355
   543.9 2767.06   554.8 2770.84   573.4 2771.05   586.6 2774.02   600.2 2781.33
   623.7 2800.49   663.8 2813.87   681.9 2818.14   694.6 2823.12   751.2 2840.61
#Mann= 6 ,-1,0
       0      .1       0      70     .06       0     180      .1       0
   499.6    .045       0   538.6      .1       0     740     .06       0
#XS Ineff= 2 , 0
          149.69 2781.14
Permanent Ineff=
       F       F
Bank Sta=499.6,538.6
XS Rating Curve= 0 ,0
Exp/Cntr=0.3,0.1

Type RM Length L Ch R = 1 ,121394  ,341.2,330.9,353.4
XS GIS Cut Line= 3
2344031.58010541 676402.162038962344198.46803023676182.574015561
2344447.24611474675857.633844029
#Sta/Elev= 30
       0 2795.02    46.8 2792.93    92.5 2787.93   116.8 2786.79   163.8 2781.99
   172.1 2780.22   179.5  2777.3   189.5  2775.3   202.2 2775.45   222.3 2766.16
     239 2765.59   267.5 2765.72   278.6 2766.02   289.4 2769.58   348.1 2768.89
   363.6 2769.91   398.5 2768.57   420.7 2770.91   443.1 2771.04   452.1 2767.08
   456.3 2766.54     476 2768.48   497.7 2769.06   539.5 2774.09   568.1 2780.07
   606.1 2783.96   620.1 2787.53   650.4 2789.61   671.8 2794.76     685 2799.78
#Mann= 8 ,-1,0
       0      .1       0      30     .06       0     190      .1       0
     239    .045       0   267.5      .1       0  515.81     .06       0
  635.81      .1       0  675.81     .06       0
Bank Sta=239,267.5
XS Rating Curve= 0 ,0
Exp/Cntr(USF)=0,0
Exp/Cntr=0.3,0.1

Type RM Length L Ch R = 1 ,121063  ,219.8,221.2,227.7
XS GIS Cut Line= 2
2344148.42038429 676489.80601668 2344605.3045483676056.515141071
#Sta/Elev= 30
       0 2791.26    60.3 2788.17   102.1 2788.14   157.9 2785.16   170.6 2783.12
     187 2778.83   195.5 2778.12   212.5 2771.89     221 2771.15   231.2 2768.08
   235.1 2767.64   258.8 2766.95   269.8 2767.99   297.4 2767.34   330.4 2768.64
   341.5 2767.97   387.9 2769.03   448.5 2767.72   461.5 2765.43   477.6 2764.92
   498.2 2765.13   501.3 2765.16   506.6 2767.27   512.3 2772.92   534.4 2784.55
   547.3 2794.47   564.8 2800.93   611.3 2822.74   617.2  2826.2   629.7 2830.72
#Mann= 6 ,-1,0
       0      .1       0     150     .06       0     270      .1       0
   461.5    .045       0   498.2      .1       0     540     .06       0
Bank Sta=461.5,498.2
XS Rating Curve= 0 ,0
Exp/Cntr=0.3,0.1

Type RM Length L Ch R = 1 ,120842  ,236.8,241.9,245.4
XS GIS Cut Line= 2
2344213.38062904676582.5291931832344805.08476139676236.752090845
#Sta/Elev= 30
       0 2798.82    54.2 2793.66    95.9 2787.13     158 2773.67   174.7 2770.96
   188.6 2770.22   197.8 2767.47   216.7 2764.73   230.2 2766.35   253.4 2765.66
   280.2  2766.7   318.8 2766.62   333.5 2764.85   351.5 2766.54   406.6  2767.3
   420.2 2766.58     430 2764.25   457.3 2763.92   486.3 2764.14   503.1  2765.1
   512.9 2767.24   517.7 2769.73   531.4 2779.78     544 2784.85   552.8 2790.03
     582 2798.41   605.4 2801.86   656.5 2806.54   670.4 2808.67   685.3 2809.27
#Mann= 7 ,-1,0
       0      .1       0     190     .06       0     270      .1       0
     390     .06       0     430    .045       0   486.3     .06       0
     580      .1       0
Bank Sta=430,486.3
XS Rating Curve= 0 ,0
Exp/Cntr(USF)=0,0
Exp/Cntr=0.3,0.1

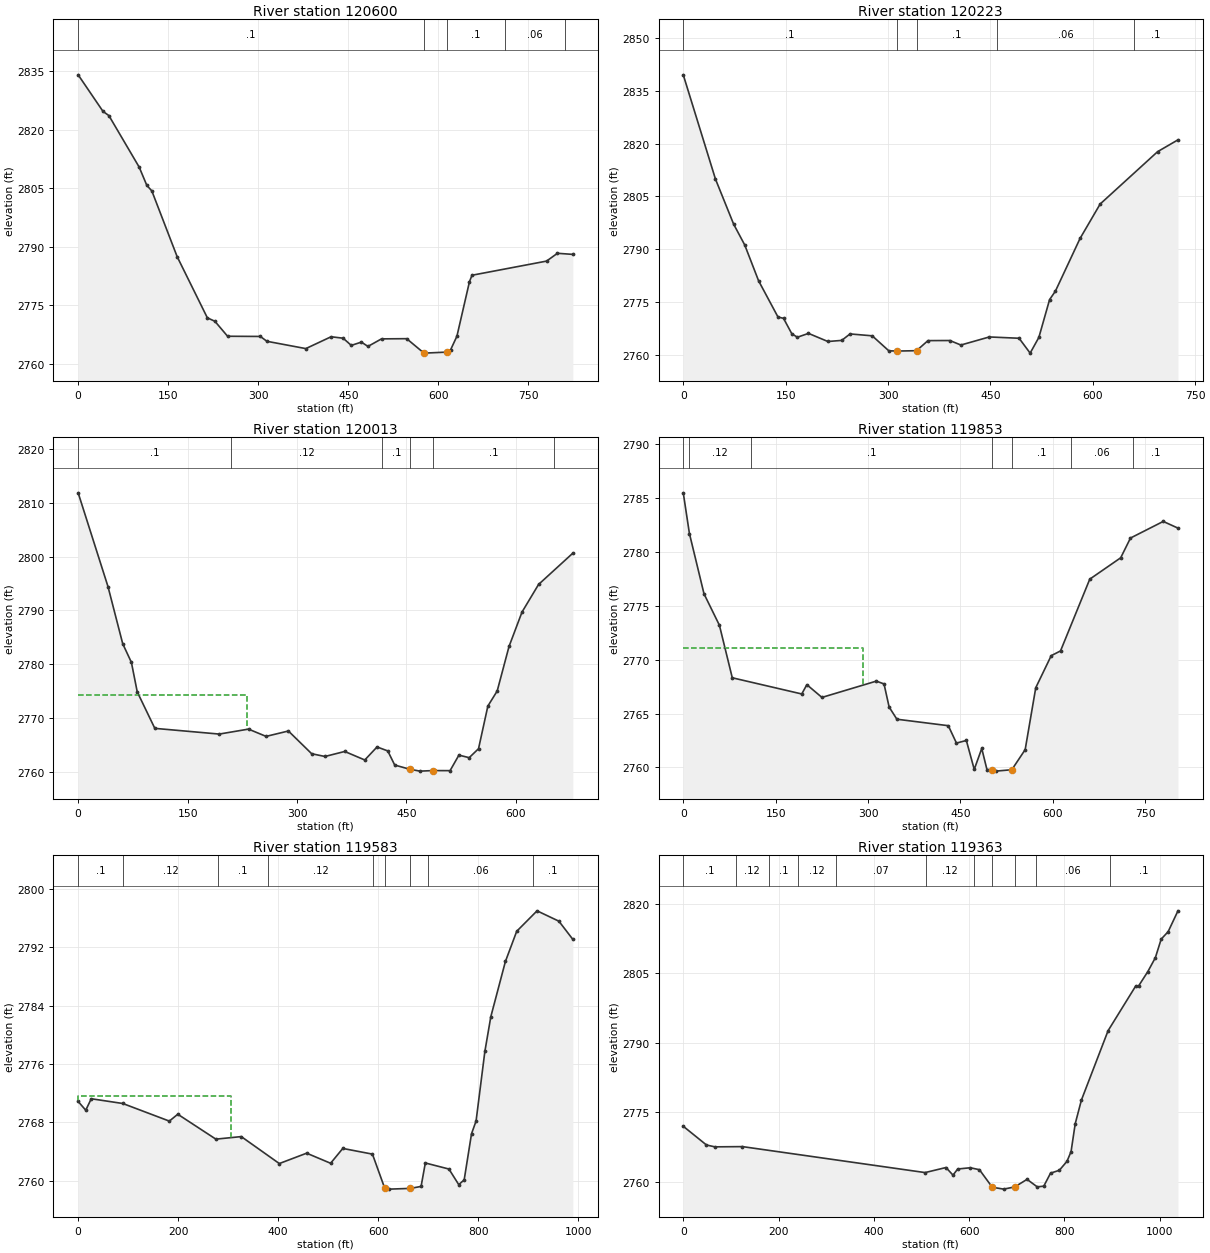
Type RM Length L Ch R = 1 ,120600  ,362,376.7,373.2
XS GIS Cut Line= 3
     2344163.476      676740.6842344630.49298478676589.004571683
2344948.69624105 676490.96287186
#Sta/Elev= 30
       0    2834    41.4 2824.64    51.2 2823.56   101.7 2810.36   114.4 2805.69
   122.7 2804.29   164.8 2787.48   215.2 2771.79   227.8  2770.9   248.9 2767.07
   303.5 2767.02   314.4 2765.78   379.2 2763.91   421.3 2766.94   441.4 2766.57
   454.9 2764.73   471.8 2765.57   482.7 2764.47   505.3  2766.4   547.2 2766.45
   575.4 2762.84   576.5 2762.75   613.8 2763.01   620.2 2763.54   630.9 2767.08
   651.8 2781.04     656 2782.69   780.2 2786.31   798.3 2788.31     824 2788.03
#Mann= 5 ,-1,0
       0      .1       0   575.4    .045       0   613.8      .1       0
  711.03     .06       0  811.03      .1       0
Bank Sta=575.4,613.8
XS Rating Curve= 0 ,0
Exp/Cntr=0.3,0.1

Type RM Length L Ch R = 1 ,120223  ,214,210.5,196.1
XS GIS Cut Line= 2
2344287.44788022676927.5178213832345001.54012557676802.592558579
#Sta/Elev= 30
       0  2839.5    47.2 2809.91    73.8 2797.14    90.1 2791.21   110.4 2781.05
   138.8 2770.78   146.9  2770.4   159.1 2766.02   167.2 2765.04   183.5 2766.13
   211.9 2763.83   232.2 2764.14   244.4 2765.98   276.9 2765.44   301.2 2761.19
   313.4 2761.12   341.8 2761.22   358.6 2764.08   390.6 2764.11   406.8 2762.83
   448.5 2765.12   492.1 2764.75   508.3 2760.53   521.1    2765   536.8 2775.72
   545.3 2778.11   581.4 2793.06   610.9 2802.84   695.1  2817.7   724.9 2821.05
#Mann= 5 ,-1,0
       0      .1       0   313.4    .045       0   341.8      .1       0
     460     .06       0     660      .1       0
Bank Sta=313.4,341.8
XS Rating Curve= 0 ,0
Exp/Cntr(USF)=0,0
Exp/Cntr=0.3,0.1

Type RM Length L Ch R = 1 ,120013  ,150.1,159.5,166.4
XS GIS Cut Line= 5
2344335.42866037677114.094830505 2344601.4608177677092.006471813
2344749.39640606677011.6620796572344802.30155121676955.072676742
2344957.63597007676898.419856554
#Sta/Elev= 30
       0 2811.83    40.9 2794.42    61.1 2783.81      73 2780.35      81 2774.87
   105.1  2768.1   193.4 2767.04   233.5 2767.96   257.6 2766.61   288.2 2767.61
   320.1 2763.39   338.3 2762.88   365.4 2763.81   392.9 2762.23   409.7 2764.65
   424.4 2763.91   433.9 2761.29   455.1 2760.49   468.6 2760.16   486.2 2760.26
   509.8 2760.25   521.9 2763.13     536 2762.66   548.8 2764.32   561.6 2772.24
   574.4 2775.04   590.6  2783.3   608.4 2789.69   631.1 2794.82   678.1 2800.63
#Mann= 6 ,-1,0
       0      .1       0     210     .12       0  416.95      .1       0
   455.1    .045       0   486.2      .1       0  652.76     .06       0
#XS Ineff= 2 , 0
          231.09 2774.25
Permanent Ineff=
       F       F
Bank Sta=455.1,486.2
XS Rating Curve= 0 ,0
Exp/Cntr=0.3,0.1

Type RM Length L Ch R = 1 ,119853  ,271.5,269.8,267.3
XS GIS Cut Line= 2
2344335.93534102677273.4007955092345105.32657392677042.301597349
#Sta/Elev= 30
       0 2785.45      10 2781.68    33.7 2776.09    58.7 2773.18    79.6 2768.31
   192.4 2766.81   200.7 2767.67   225.2 2766.49   313.5    2768     326 2767.74
   334.3  2765.6   346.9 2764.47   430.4 2763.87   443.6 2762.26   459.7  2762.5
   472.5 2759.82   484.7 2761.76   493.1 2759.81   501.5 2759.78   507.4 2759.66
   533.5 2759.79   555.2 2761.65   572.4 2767.39   597.5 2770.36   612.6  2770.8
   660.1 2777.45   710.3 2779.43   726.2 2781.26   779.4  2782.8   803.3 2782.18
#Mann= 7 ,-1,0
       0      .1       0      10     .12       0     110      .1       0
   501.5    .045       0   533.5      .1       0     630     .06       0
     730      .1       0
#XS Ineff= 2 , 0
          292.26 2771.05
Permanent Ineff=
       F       F
Bank Sta=501.5,533.5
XS Rating Curve= 0 ,0
Exp/Cntr(USF)=0,0
Exp/Cntr=0.3,0.1

Type RM Length L Ch R = 1 ,119583  ,235.2,220.5,207.5
XS GIS Cut Line= 3
2344275.81630209677598.1513612382344966.26872898677359.508480195
2345195.57449132677238.947288393
#Sta/Elev= 30
       0 2770.87    15.2 2769.67    26.2 2771.24    89.3 2770.59   182.4 2768.18
   199.3 2769.12   275.5 2765.71   326.3 2766.06   402.4 2762.37   457.1 2763.79
     505 2762.41   529.4 2764.44   588.7 2763.66   613.4 2758.97   622.5 2758.87
   664.7 2758.97     686 2759.24   694.5 2762.45   741.7 2761.62   761.3 2759.49
   772.2 2760.13   786.9 2766.45     796 2768.19   813.6 2777.72   825.5 2782.47
   854.7 2790.03   877.3 2794.16     918 2796.96   961.7 2795.54   989.6 2793.05
#Mann= 9 ,-1,0
       0      .1       0      90     .12       0     280      .1       0
     380     .12       0     590      .1       0   613.4    .045       0
   664.7      .1       0     700     .06       0  910.53      .1       0
#XS Ineff= 2 , 0
          305.26 2771.55
Permanent Ineff=
       F       F
Bank Sta=613.4,664.7
XS Rating Curve= 0 ,0
Exp/Cntr=0.3,0.1

Type RM Length L Ch R = 1 ,119363  ,288.2,288.1,285.2
XS GIS Cut Line= 4
2344561.39797337677986.4263703222344992.59525774677583.411914993
2345108.14485683677439.6794868692345325.15264046677290.310492936
#Sta/Elev= 30
       0 2772.01    48.7 2767.97    66.3 2767.57   124.3 2767.62   507.5 2762.02
   551.3 2763.11     566 2761.47   575.9 2762.79   602.3 2763.06   621.5 2762.64
   648.4 2758.86   672.5 2758.45   695.7 2758.93   721.4 2760.56   742.8 2758.94
   756.5 2759.09   770.7 2761.89   789.2 2762.52   805.2 2764.44   813.8 2766.55
   822.5 2772.56   835.5 2777.66   891.5 2792.63     949 2802.19   955.4 2802.26
   974.9 2805.38   990.7 2808.38  1002.9 2812.38  1017.5 2813.98  1038.1 2818.48
#Mann= 11 ,-1,0
       0      .1       0     110     .12       0     180      .1       0
     240     .12       0     320     .07       0     510     .12       0
  610.21      .1       0   648.4    .045       0   695.7      .1       0
  740.21     .06       0  894.63      .1       0
Bank Sta=648.4,695.7
XS Rating Curve= 0 ,0
Exp/Cntr(USF)=0,0
Exp/Cntr=0.3,0.1