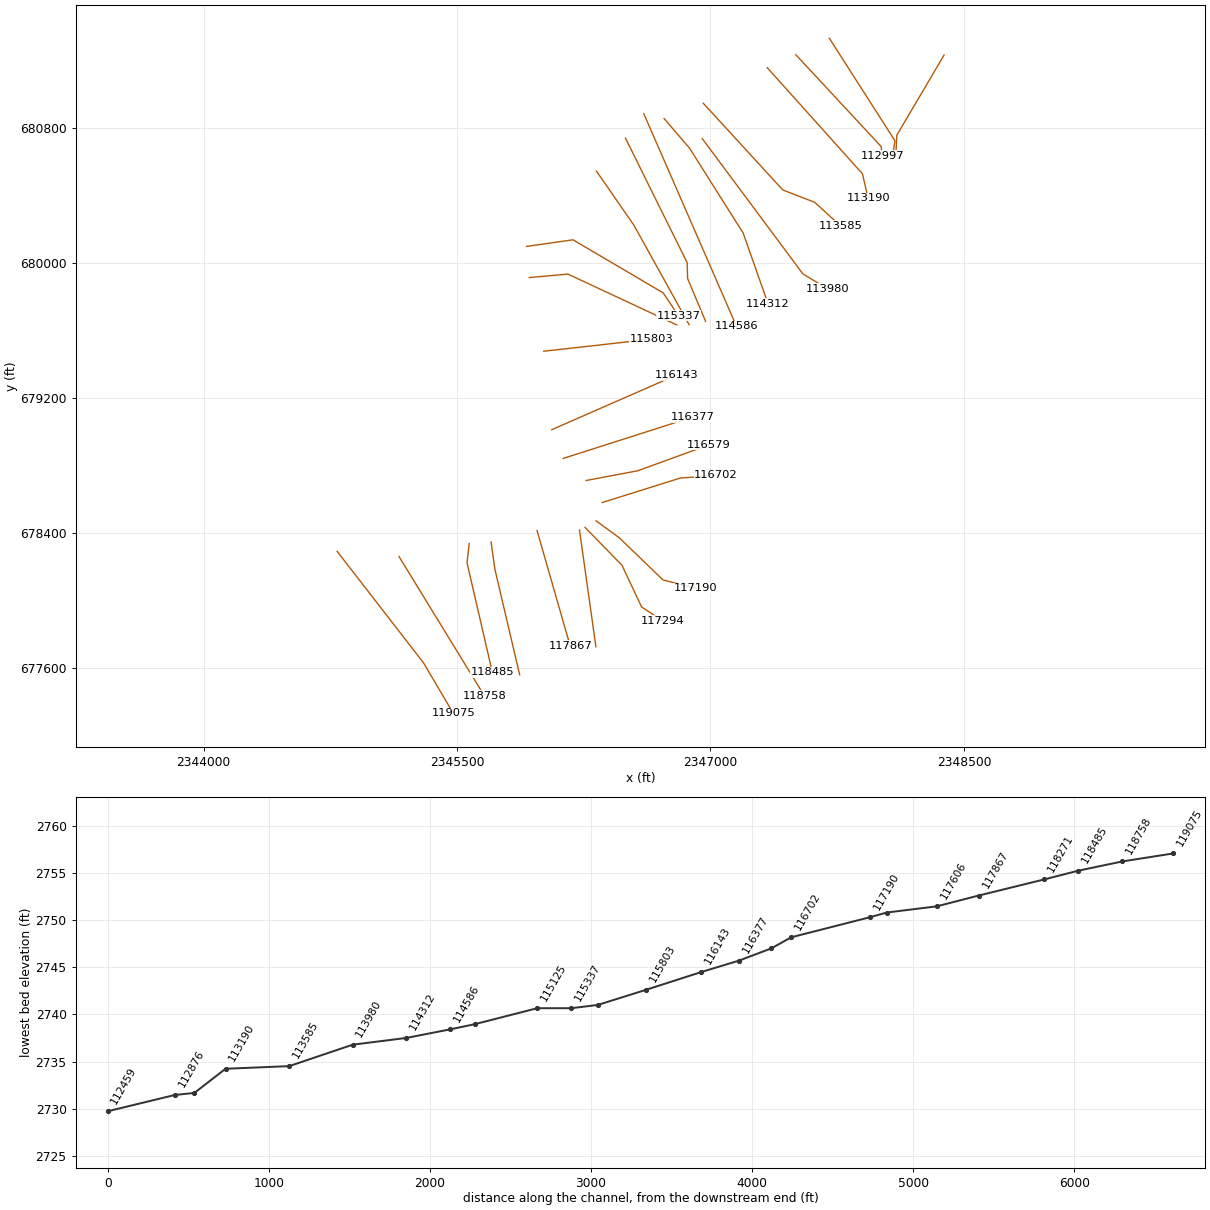
HEC-RAS study GLADYFK.prj: GLADYFK

--- GLADYFK.g01 (geometry) --- (continued)

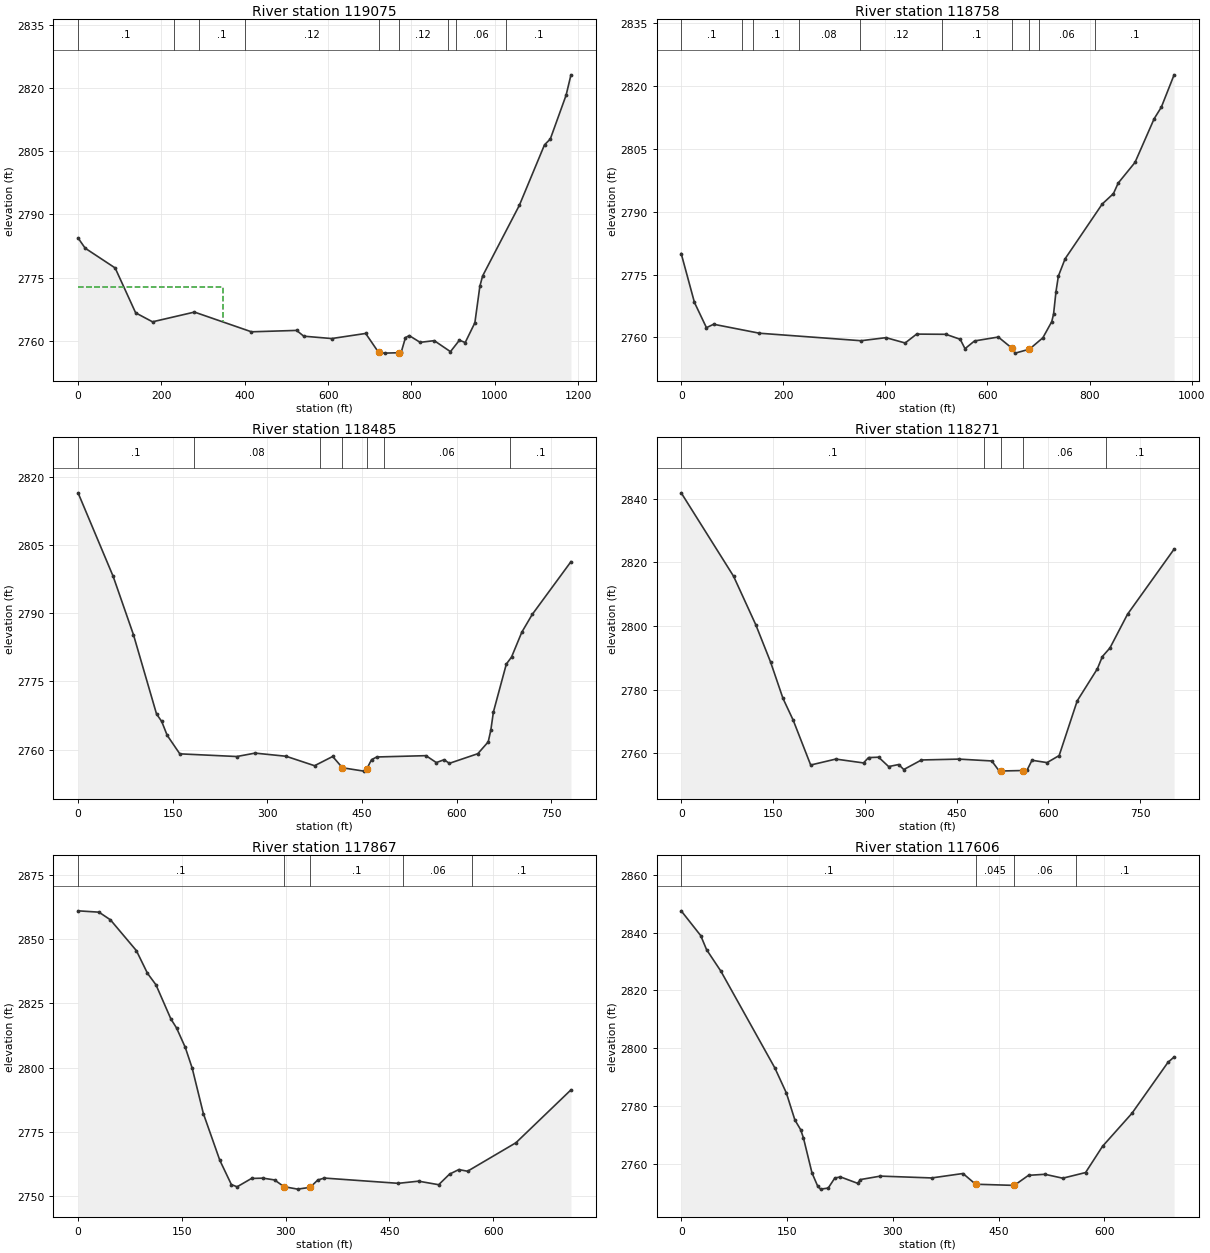
Type RM Length L Ch R = 1 ,119075  ,310.3,316.3,294.8
XS GIS Cut Line= 3
2344789.70718957678290.4713838862345301.79261476677628.877971045
2345477.38540042 677330.38870092
#Sta/Elev= 30
       0 2784.42    17.1    2782      89 2777.31   138.2 2766.66   178.7 2764.53
   279.3 2766.84   416.1 2762.16   524.5 2762.49   541.6 2761.12   608.6 2760.56
   690.2 2761.77   721.2 2757.28     736  2757.1   770.5  2757.2   775.4 2757.27
   785.7 2760.78   794.8 2761.26   820.9 2759.66   854.8 2760.06   893.7 2757.45
   915.2 2760.17   929.1 2759.61   952.3  2764.3   964.3 2772.99   970.9 2775.42
    1059 2792.17  1119.4 2806.53  1133.3 2807.91  1171.2  2818.3  1182.9 2823.14
#Mann= 9 ,-1,0
       0      .1       0     230     .12       0     290      .1       0
     400     .12       0   721.2    .045       0   770.5     .12       0
  886.62      .1       0  906.62     .06       0 1026.62      .1       0
#XS Ineff= 2 , 0
          346.64 2772.91
Permanent Ineff=
       F       F
Bank Sta=721.2,770.5
XS Rating Curve= 0 ,0
Exp/Cntr=0.3,0.1

Type RM Length L Ch R = 1 ,118758  ,274,273.5,260.3
XS GIS Cut Line= 2
2345156.21322781678259.3594136712345660.37272515677435.794520498
#Sta/Elev= 30
       0 2780.01      26 2768.33    49.5 2762.32    63.5 2763.14   153.2    2761
   352.3 2759.21   401.2 2759.94   438.7 2758.67   461.2 2760.79   518.5 2760.74
   546.6 2759.55     556 2757.31   574.7 2759.16   621.2 2760.09   647.4 2757.49
   654.5 2756.25   682.3  2757.2   708.5 2759.91   725.9 2763.75   729.5 2765.57
   734.2 2770.91   738.9 2774.63   752.1 2778.76   824.8 2791.82   846.8 2794.31
   856.1 2796.82     889 2801.74   926.5 2812.16   940.6 2814.93   965.6 2822.64
#Mann= 10 ,-1,0
       0      .1       0     120     .08       0     140      .1       0
     230     .08       0     350     .12       0     510      .1       0
   647.4    .045       0   682.3      .1       0     700     .06       0
     810      .1       0
Bank Sta=647.4,682.3
XS Rating Curve= 0 ,0
Exp/Cntr(USF)=0,0
Exp/Cntr=0.3,0.1

Type RM Length L Ch R = 1 ,118485  ,213,214,211.6
XS GIS Cut Line= 3
2345571.92177947678336.4033176842345558.55928267678223.225877004
2345708.63543512677573.385114006
#Sta/Elev= 30
       0 2816.44    55.6 2798.08    87.8 2785.24   124.3 2767.84   132.5 2766.19
   141.2 2763.14   161.2 2759.07   251.5 2758.48   280.4 2759.23   329.5 2758.54
   374.7 2756.46   403.4 2758.49   418.8 2756.01   452.7 2755.27   457.2 2755.72
     465 2757.79   473.2 2758.38   551.2 2758.67   567.6 2757.15     580 2757.78
   588.2 2756.98   633.3  2759.1   649.8  2761.7   653.9 2764.25     658 2768.26
   678.5  2778.8   686.7 2780.33   703.1 2785.83   719.5  2789.7   780.9 2801.31
#Mann= 7 ,-1,0
       0      .1       0  183.96     .08       0  383.96      .1       0
   418.8    .045       0   457.2      .1       0  483.96     .06       0
  683.96      .1       0
Bank Sta=418.8,457.2
XS Rating Curve= 0 ,0
Exp/Cntr=0.3,0.1

Type RM Length L Ch R = 1 ,118271  ,401.2,404.4,401.9
XS GIS Cut Line= 3
 2345700.7345641678345.935514994 2345724.0131933678182.856175451
2345870.24119793677559.116797575
#Sta/Elev= 30
       0 2841.87    85.6 2815.63     122 2800.32   146.2 2788.57   166.3 2777.22
     183 2770.36   211.6 2756.25   252.6 2758.12   297.9 2756.91   306.1 2758.59
   322.6 2758.71     339 2755.76   355.4 2756.41   363.7 2754.83   392.6 2757.84
     454 2758.11   507.5 2757.53   519.8 2754.33   522.4 2754.37   558.5 2754.52
     565 2754.59   573.2 2757.75   597.8 2757.01   617.6 2759.23   647.1 2776.44
     680 2786.51   688.2 2790.37   700.6 2793.08   729.3 2803.68   805.4 2824.16
#Mann= 5 ,-1,0
       0      .1       0  494.73     .06       0   522.4    .045       0
   558.5     .06       0  694.73      .1       0
Bank Sta=522.4,558.5
XS Rating Curve= 0 ,0
Exp/Cntr=0.3,0.1

Type RM Length L Ch R = 1 ,117867  ,268.4,260.8,274.8
XS GIS Cut Line= 2
 2345973.1414174678414.1897158212346169.46300452677729.346970053
#Sta/Elev= 30
       0 2861.02    30.2  2860.5    46.8 2857.51    84.3 2845.52   100.3  2836.7
   112.6 2832.21   134.2 2818.88   142.3 2815.43     155  2807.8     165  2799.7
   181.1 2782.06   204.9 2763.85   221.6  2754.4   229.9 2753.54   250.7 2756.79
   267.4  2756.9     284 2756.21   297.6 2753.59   317.3 2752.63   335.4 2753.32
   346.4 2756.16   355.8 2756.94   462.9 2754.89   492.1 2755.73   521.2 2754.35
   536.9 2758.47   550.3 2760.24   562.9  2759.6   632.9  2770.7   712.4 2791.29
#Mann= 5 ,-1,0
       0      .1       0   297.6    .045       0   335.4      .1       0
     470     .06       0     570      .1       0
Bank Sta=297.6,335.4
XS Rating Curve= 0 ,0
Exp/Cntr(USF)=0,0
Exp/Cntr=0.3,0.1

Type RM Length L Ch R = 1 ,117606  ,303.2,311.3,348.9
XS GIS Cut Line= 2
2346224.50194569678416.8190257812346321.62009945677724.799380205
#Sta/Elev= 30
       0 2847.48    27.7 2838.93      36 2834.08    56.2 2826.69   132.9 2793.23
   149.1 2784.65   161.2 2775.32   169.3 2772.02   173.3 2769.16   185.4 2757.11
   193.5 2752.52   197.6 2751.48   208.4 2751.84   217.8 2755.31   225.8 2755.69
   250.1 2753.49   254.1 2754.78   282.4 2755.97   355.1 2755.34   399.5 2756.87
   417.4 2753.17   472.2 2752.77   492.4 2756.24   515.7  2756.6   540.9 2755.25
   573.3  2757.2   597.4 2766.27     639 2777.62   690.1 2795.21   698.8 2797.06
#Mann= 4 ,-1,0
       0      .1       0   417.4    .045       0   472.2     .06       0
     560      .1       0
Bank Sta=417.4,472.2
XS Rating Curve= 0 ,0
Exp/Cntr=0.3,0.1

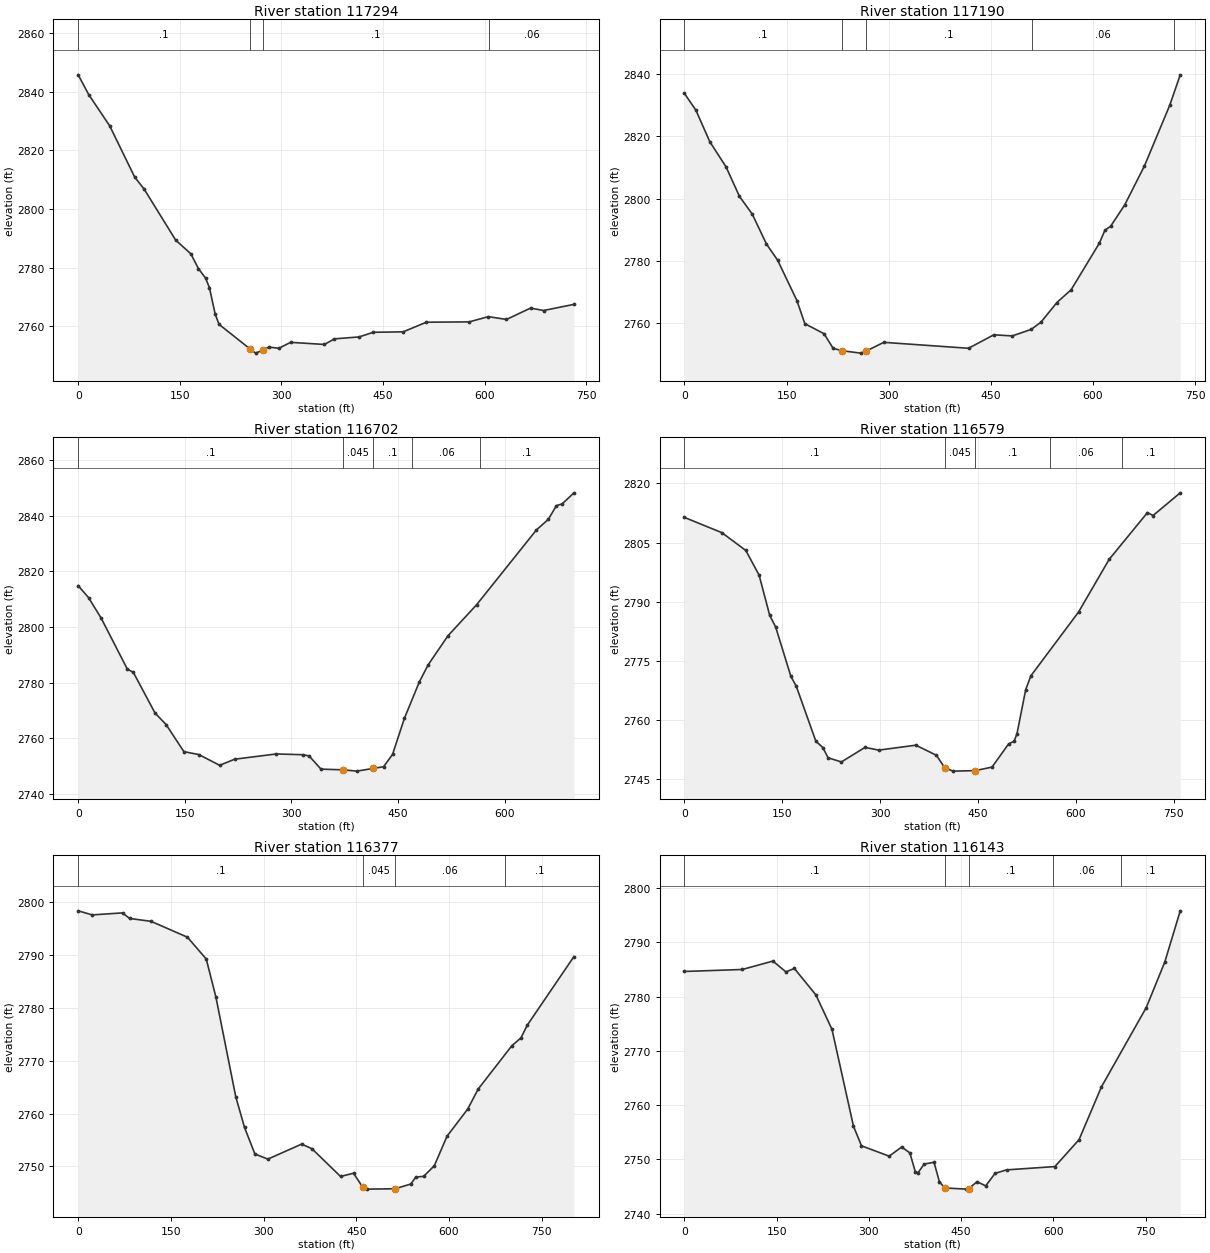
Type RM Length L Ch R = 1 ,117294  ,104.3,104.4,105.7
XS GIS Cut Line= 4
2346257.36567177678432.2252364332346476.13492018678207.846520117
 2346592.0639236 677961.029932172346713.60239494677880.627558824
#Sta/Elev= 30
       0 2845.79    15.5 2839.05    46.6 2828.33    83.3 2810.92    97.5 2806.73
   143.9 2789.38   166.3 2784.71   177.4 2779.69     188 2776.41   193.7 2773.17
   202.1 2764.23   207.8 2760.66   253.1 2752.35   261.9 2750.82   273.3 2751.85
   281.3 2752.89   296.2 2752.48   313.5  2754.5   363.5 2753.78   378.2 2755.69
   414.6 2756.35   435.6 2757.93   479.8 2758.09   513.9 2761.37   577.1 2761.48
   605.4 2763.27   632.2 2762.31   667.7  2766.2   686.9 2765.36   731.8 2767.46
#Mann= 4 ,-1,0
       0      .1       0   253.1    .045       0   273.3      .1       0
  606.06     .06       0
Bank Sta=253.1,273.3
XS Rating Curve= 0 ,0
Exp/Cntr(USF)=0,0
Exp/Cntr=0.3,0.1

Type RM Length L Ch R = 1 ,117190  ,480,488.5,521.6
XS GIS Cut Line= 4
2346322.97472255678471.1574892162346459.97363364678370.908109075
2346718.33574063678121.4893057942346911.11362045678070.810584808
#Sta/Elev= 30
       0 2833.81    16.9 2828.38    37.2 2818.29      61 2810.23    80.8 2800.71
    99.6    2795   120.4 2785.41   136.8 2780.21   165.1 2767.24   176.8 2759.79
   205.1 2756.55   218.3 2751.88   231.2 2751.09     259 2750.32   267.3 2751.03
   292.8 2753.79   417.2 2751.88   454.4 2756.21   481.4 2755.85   509.2 2757.94
   523.6 2760.27     547 2766.58     568 2770.71   609.4 2785.67   617.6 2789.84
   625.9  2791.1   646.6 2797.96   675.5 2810.45   712.8 2830.02   728.2  2839.8
#Mann= 5 ,-1,0
       0      .1       0   231.2    .045       0   267.3      .1       0
  509.76     .06       0  718.87      .1       0
Bank Sta=231.2,267.3
XS Rating Curve= 0 ,0
Exp/Cntr(USF)=0,0
Exp/Cntr=0.3,0.1

Type RM Length L Ch R = 1 ,116702  ,123.8,122.2,124.7
XS GIS Cut Line= 3
2346358.26890218678579.5544620282346821.75504829678724.865008456
2347032.82581017678740.466413966
#Sta/Elev= 30
       0 2814.83    14.6 2810.51    32.2  2803.2    69.1 2784.85    77.5  2783.7
   108.1 2769.05   123.6 2764.93   148.7 2755.18   169.7 2754.14     199 2750.28
     220 2752.47   278.7 2754.36   316.4 2754.08   324.8 2753.65   341.5 2748.91
   372.9 2748.65   391.9 2748.19   414.5 2749.14   429.6 2749.78   442.2  2754.2
   458.9 2767.19   479.9 2780.26   492.3 2786.38   520.2 2796.84   560.4 2807.96
   644.6 2834.85   661.3 2838.63   672.7 2843.57   680.7 2844.19   697.4 2848.18
#Mann= 5 ,-1,0
       0      .1       0   372.9    .045       0   414.5      .1       0
     470     .06       0  565.73      .1       0
Bank Sta=372.9,414.5
XS Rating Curve= 0 ,0
Exp/Cntr(USF)=0,0
Exp/Cntr=0.3,0.1

Type RM Length L Ch R = 1 ,116579  ,202.8,202.6,200.2
XS GIS Cut Line= 3
2346263.78351556678710.3336006492346569.25801799678767.907166937
2346991.36593452678921.635700487
#Sta/Elev= 30
       0 2811.36    57.4 2807.49      94 2802.99   114.4 2796.74   130.7 2786.52
   139.8 2783.57   163.2 2771.02   171.4 2768.56   201.4 2754.62   212.1    2753
   220.2 2750.41   240.6 2749.35   276.8 2753.04   297.9 2752.35   354.7  2753.6
   386.3 2751.04   399.1 2747.85   411.9 2747.02   445.9 2747.15   471.5 2748.04
     497 2753.93   505.5 2754.61   509.8 2756.51   523.2 2767.71   531.1 2771.19
   604.3 2787.39   651.1 2800.72   709.9  2812.6   718.4 2811.84   760.1  2817.6
#Mann= 5 ,-1,0
       0      .1       0   399.1    .045       0   445.9      .1       0
  560.85     .06       0  670.85      .1       0
Bank Sta=399.1,445.9
XS Rating Curve= 0 ,0
Exp/Cntr=0.3,0.1

Type RM Length L Ch R = 1 ,116377  ,232.6,233.7,239.8
XS GIS Cut Line= 2
2346127.84385531678841.0595080852346891.91166495679085.310693133
#Sta/Elev= 30
       0 2798.38    22.6 2797.61    71.7 2797.99    83.1 2796.94   117.9 2796.39
   176.7 2793.39   207.2 2789.26   222.9 2782.02   254.9 2763.22   269.1 2757.39
   285.9 2752.36   306.9 2751.39   361.5 2754.23   378.3 2753.35   424.5 2748.11
   445.5 2748.72   460.2 2746.11   468.1 2745.71   512.7 2745.78   538.1 2746.67
   546.3    2748   558.9 2748.12   576.3 2750.15   596.7  2755.7   630.3 2760.87
   647.1 2764.63   701.6 2772.84   716.4 2774.33   726.8 2776.77   802.2 2789.73
#Mann= 4 ,-1,0
       0      .1       0   460.2    .045       0   512.7     .06       0
     690      .1       0
Bank Sta=460.2,512.7
XS Rating Curve= 0 ,0
Exp/Cntr(USF)=0,0
Exp/Cntr=0.3,0.1

Type RM Length L Ch R = 1 ,116143  ,347,339.7,335.5
XS GIS Cut Line= 2
      2346060.49      679011.4422346798.89034323679335.319368751
#Sta/Elev= 30
       0 2784.65    93.9 2785.01   143.8 2786.56     165 2784.57   178.7  2785.2
   213.7 2780.33   239.9 2773.97   274.8 2756.13   287.9 2752.49   332.9 2750.58
   353.3 2752.27   366.6 2751.18   375.3 2747.74   379.7 2747.49   389.7 2749.12
   405.9 2749.45   414.6 2745.86   423.3 2744.72   458.3  2744.5   462.6  2744.6
   475.8 2745.87   489.9  2745.1   505.1  2747.4   523.8 2748.05   602.4 2748.66
   641.7 2753.62   678.1 2763.35     751 2777.98   781.1 2786.36   806.3 2795.83
#Mann= 5 ,-1,0
       0      .1       0   423.3    .045       0   462.6      .1       0
     600     .06       0     710      .1       0
Bank Sta=423.3,462.6
XS Rating Curve= 0 ,0
Exp/Cntr=0.3,0.1

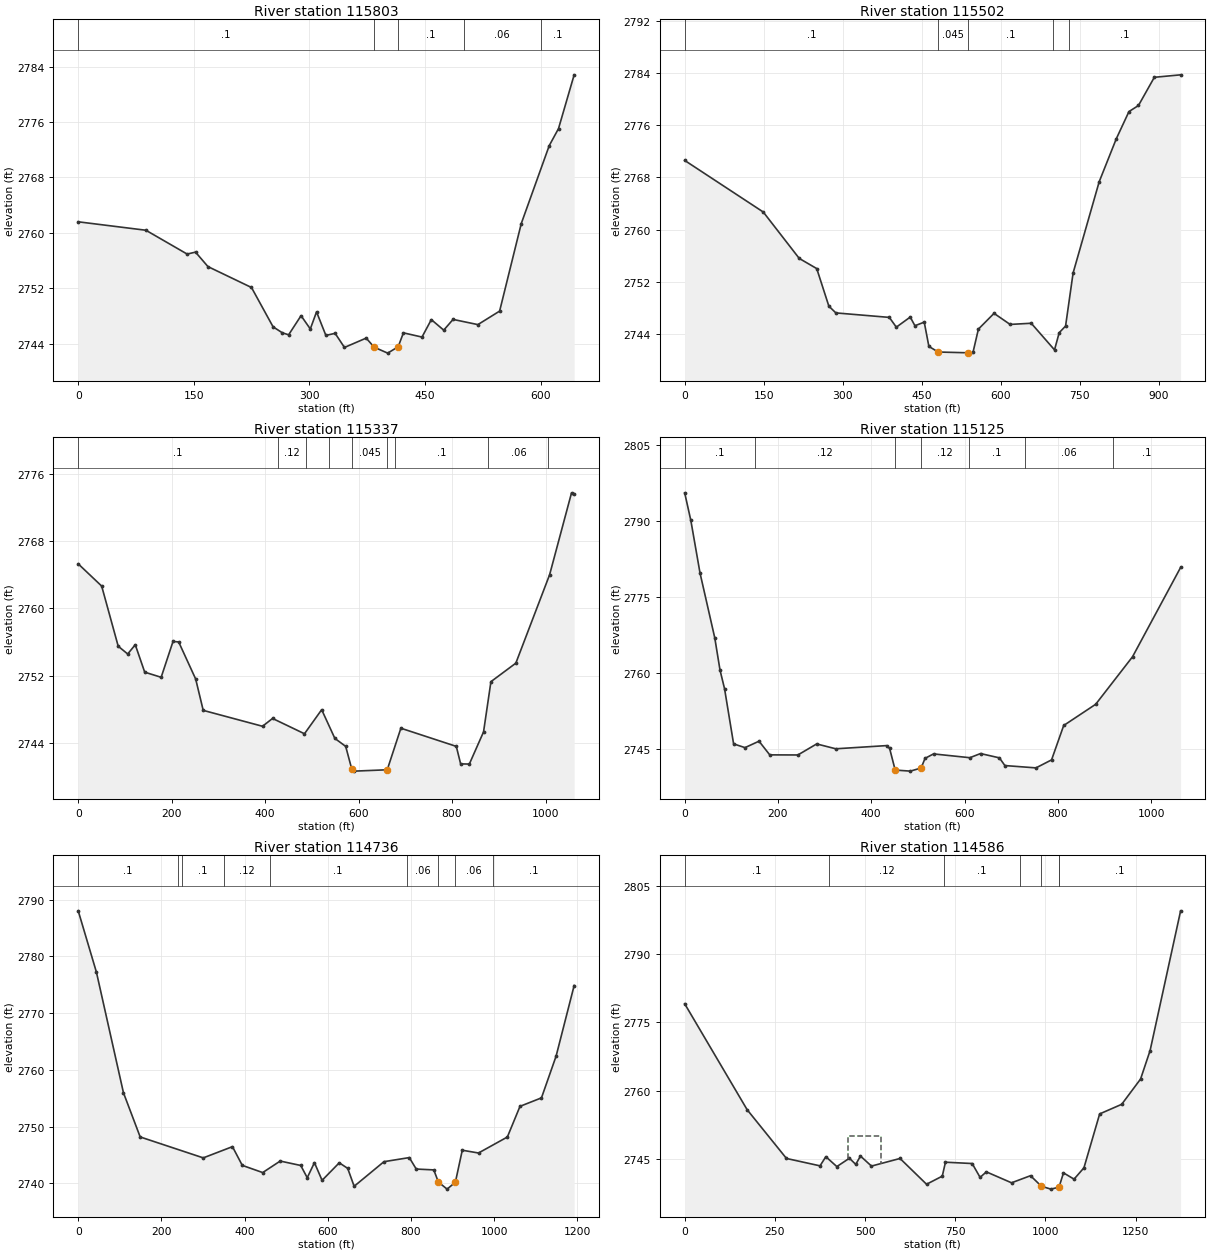
Type RM Length L Ch R = 1 ,115803  ,319.2,301.8,290
XS GIS Cut Line= 2
2346012.89530494679476.2676950522346652.32847798 679547.82880828
#Sta/Elev= 30
       0  2761.6    87.8 2760.38   141.3 2756.94   152.2 2757.22   168.3 2755.13
   224.8 2752.11   252.8 2746.43   264.9 2745.56     273 2745.28   289.1 2748.04
   301.1 2746.12   309.2 2748.59   321.3 2745.19   333.3 2745.49   345.4 2743.45
   373.6  2744.8   383.9 2743.49   401.5 2742.63   415.1 2743.55   421.9 2745.56
     446 2744.95   458.1 2747.47   474.2 2745.95   486.3  2747.5   518.5 2746.75
   546.7  2748.7   574.8 2761.35   611.1 2772.61   623.1 2775.06   643.4 2782.83
#Mann= 5 ,-1,0
       0      .1       0   383.9    .045       0   415.1      .1       0
     500     .06       0     600      .1       0
Bank Sta=383.9,415.1
XS Rating Curve= 0 ,0
Exp/Cntr(USF)=0,0
Exp/Cntr=0.3,0.1

Type RM Length L Ch R = 1 ,115502  ,167.7,164.5,161.1
XS GIS Cut Line= 3
2345927.53724298679912.787851654 2346156.0175314679933.335450509
2346801.09964796679631.648124201
#Sta/Elev= 30
       0 2770.62   149.2 2762.69   217.5 2755.56   250.7    2754   273.7 2748.23
     287 2747.19   388.5  2746.5   401.8    2745   428.2 2746.55   437.1 2745.22
   454.8 2745.77   463.6 2742.04   481.3 2741.18   538.7 2741.06   542.5 2741.01
   547.5 2741.18   557.6  2744.7   587.3 2747.12   617.8 2745.42   657.9  2745.6
   702.1 2741.51     711 2744.15   723.1 2745.17   737.4 2753.33   786.9 2767.34
   819.3 2773.93   843.4 2778.12   861.5 2779.06   891.6 2783.39   941.5 2783.77
#Mann= 5 ,-1,0
       0      .1       0   481.3    .045       0   538.7      .1       0
   699.4     .06       0   729.4      .1       0
Bank Sta=481.3,538.7
XS Rating Curve= 0 ,0
Exp/Cntr=0.3,0.1

Type RM Length L Ch R = 1 ,115337  ,232,212.3,203.9
XS GIS Cut Line= 4
2345911.32469262680097.233484032 2346186.0270305680136.476675157
 2346719.2727452679822.5311461562346811.31760571679685.580873492
#Sta/Elev= 30
       0 2765.29    50.2 2762.65    85.6  2755.5   105.9 2754.58   122.1 2755.68
   142.3 2752.42   177.5 2751.81   202.9 2756.07     215 2756.01   251.4  2751.6
   267.5 2747.88   394.4 2745.99   415.9 2746.92   484.2  2745.1     521 2747.96
   549.2 2744.55   572.4  2743.6   585.3 2740.92     591 2740.66   661.3 2740.82
   690.5 2745.76   809.1  2743.6   818.4 2741.52     837  2741.5   867.4 2745.32
   883.2 2751.29   936.5 2753.49  1008.8    2764  1055.7 2773.73  1061.3 2773.61
#Mann= 9 ,-1,0
       0      .1       0  427.49     .12       0  487.49      .1       0
  537.49     .12       0   585.3    .045       0   661.3     .12       0
  677.49      .1       0  877.49     .06       0 1006.29      .1       0
Bank Sta=585.3,661.3
XS Rating Curve= 0 ,0
Exp/Cntr(USF)=0,0
Exp/Cntr=0.3,0.1

Type RM Length L Ch R = 1 ,115125  ,412.8,388.5,377
XS GIS Cut Line= 3
2346324.68603872680543.4558330632346546.37846371680223.332406445
2346873.17402017679633.943165314
#Sta/Elev= 30
       0 2795.61    13.2 2790.16    32.9 2779.77    64.5 2766.98    75.8 2760.59
    85.5 2756.92   104.9 2746.04   129.3  2745.3   159.4 2746.57   182.4 2743.87
   242.7 2743.85     283 2746.03   323.9 2745.07     433  2745.7   439.4 2745.14
   451.3 2740.87   483.8 2740.66     507 2741.28   515.3 2743.18   533.5 2744.06
   611.4 2743.31   634.3 2744.13   674.8 2743.28   686.5 2741.76   753.2  2741.3
   786.6 2742.88   812.6 2749.67   881.2 2753.86   960.2 2763.24  1063.3 2780.88
#Mann= 7 ,-1,0
       0      .1       0     150     .12       0   451.3    .045       0
     507     .12       0  609.39      .1       0  729.39     .06       0
  919.39      .1       0
Bank Sta=451.3,507
XS Rating Curve= 0 ,0
Exp/Cntr=0.3,0.1

Type RM Length L Ch R = 1 ,114736  ,141.5,150.2,159.2
XS GIS Cut Line= 4
2346496.75708909 680738.73135618 2346862.0065535 680000.62306352
2346864.54300811679906.774242803 2346971.0741019679653.128781408
#Sta/Elev= 30
       0 2788.03    43.8 2777.21   108.8 2755.95     149 2748.16   300.7 2744.47
   370.9 2746.45   394.5 2743.15   443.6 2741.88   485.7 2743.91   535.1 2743.13
   550.7 2740.97     568 2743.63   586.4 2740.51   627.7  2743.6     648 2742.62
   663.5 2739.46   735.2  2743.8   796.1 2744.52   812.8  2742.5     855 2742.35
     866 2740.21     887 2738.96   906.9 2740.18   923.5 2745.82   962.5 2745.33
  1031.9 2748.15  1062.3 2753.56  1113.9 2755.05  1149.1 2762.41  1192.5 2774.86
#Mann= 9 ,-1,0
       0      .1       0     240     .08       0     250      .1       0
     350     .12       0     460      .1       0     790     .06       0
     866    .045       0   906.9     .06       0  997.42      .1       0
Bank Sta=866,906.9
XS Rating Curve= 0 ,0
Exp/Cntr(USF)=0,0
Exp/Cntr=0.3,0.1

Type RM Length L Ch R = 1 ,114586  ,273.1,274.3,271.8
XS GIS Cut Line= 3
2346605.10777083680883.8799623912346964.16216694680059.725798701
2347154.09535024679623.428132576
#Sta/Elev= 30
       0 2779.11   173.1 2755.86   282.2 2745.15   375.2 2743.53   391.3 2745.54
   421.8 2743.37   456.7  2745.2   474.2 2743.85   487.3 2745.68   517.8 2743.48
     597 2745.15   670.5 2739.49   714.1 2741.27   722.9 2744.33     797 2744.04
   818.9    2741   836.3 2742.21   906.1 2739.81   958.7 2741.37   988.9 2739.05
  1015.2 2738.42  1037.7 2738.85  1050.1 2741.99  1079.4 2740.61  1106.8  2743.1
  1150.4 2754.93  1211.5 2757.04  1263.8 2762.59  1290.2 2768.84  1374.8 2799.51
#Mann= 7 ,-1,0
       0      .1       0     400     .12       0     720      .1       0
  928.97     .06       0   988.9    .045       0  1037.7     .06       0
 1038.97      .1       0
#XS Ineff= 1 ,-1
  451.89   543.72750.052
Permanent Ineff=
       F
Bank Sta=988.9,1037.7
XS Rating Curve= 0 ,0
Exp/Cntr=0.3,0.1

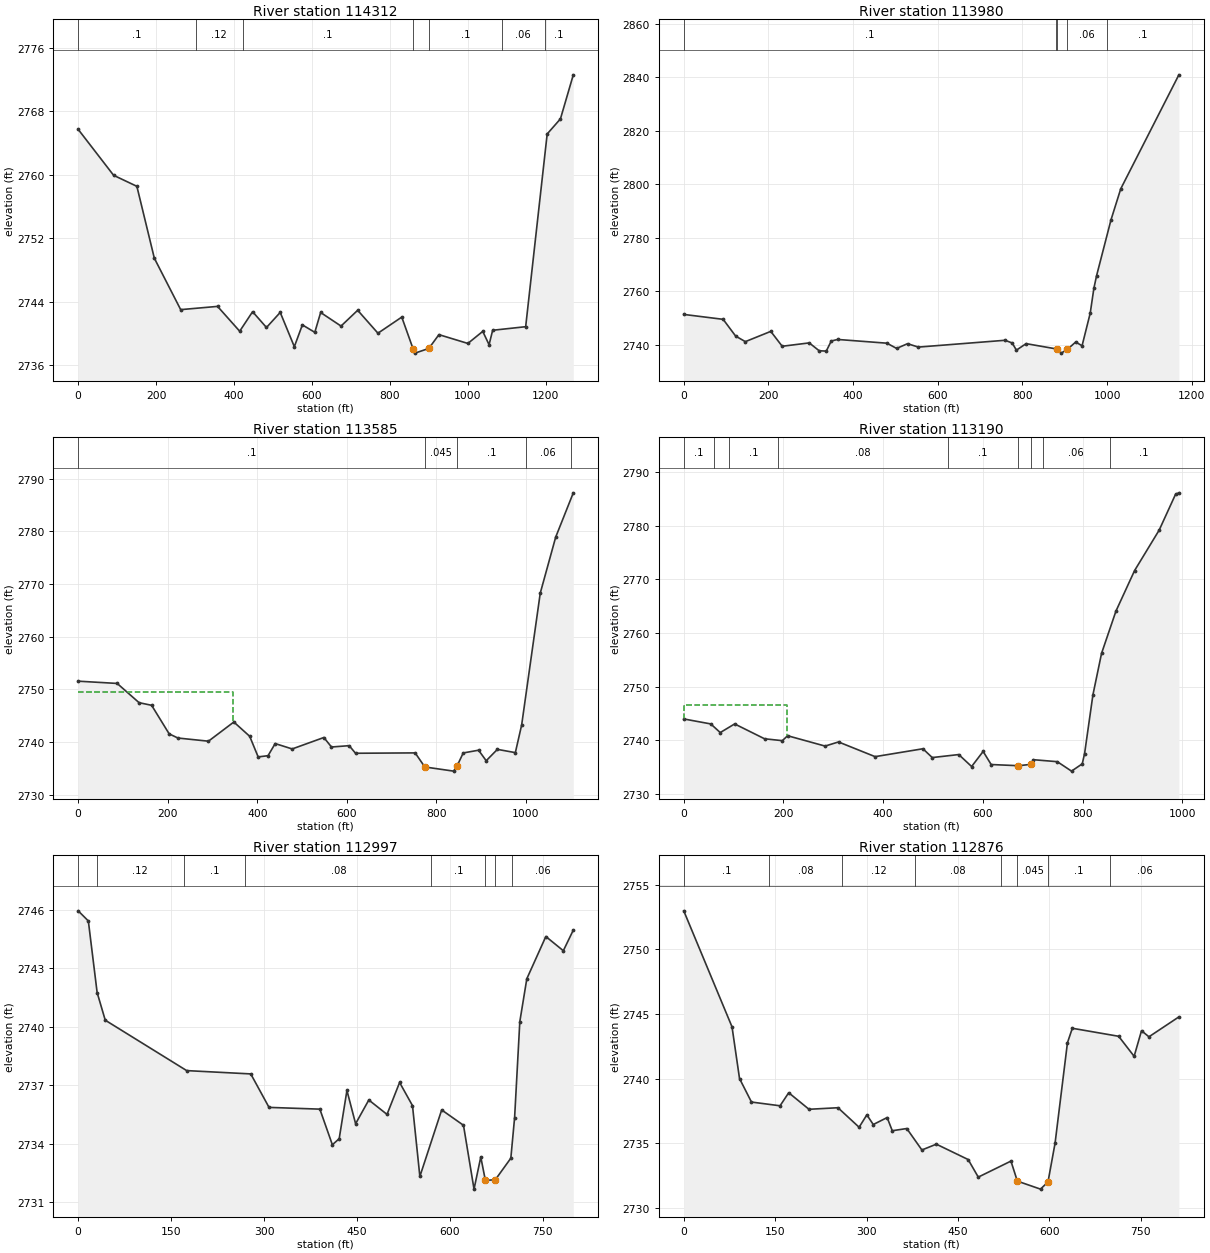
Type RM Length L Ch R = 1 ,114312  ,318.6,331.6,313.1
XS GIS Cut Line= 4
2346724.98886494680855.5375832092346875.95635576680679.482571527
2347193.51824608680176.2114283682347340.56813445679758.035227256
#Sta/Elev= 30
       0  2765.7    90.9 2759.91   150.6 2758.52   195.4 2749.46     263 2742.98
   357.6 2743.39   414.4 2740.26   447.5 2742.72   483.1 2740.73   518.4 2742.63
   554.6 2738.31   575.2 2741.06   607.1 2740.12   622.1 2742.62   674.4 2740.91
   717.1  2742.9   769.1 2740.01   830.2 2742.04   859.1 2738.06   864.1  2737.5
   899.6 2738.09   925.6 2739.83   999.8 2738.72    1038 2740.24  1054.2 2738.56
  1063.4 2740.38  1148.1 2740.83  1203.3 2765.12  1237.3 2767.02  1270.3 2772.57
#Mann= 7 ,-1,0
       0      .1       0  301.92     .12       0  421.92      .1       0
   859.1    .045       0   899.6      .1       0 1087.01     .06       0
 1197.01      .1       0
Bank Sta=859.1,899.6
XS Rating Curve= 0 ,0
Exp/Cntr(USF)=0,0
Exp/Cntr=0.3,0.1

Type RM Length L Ch R = 1 ,113980  ,383.7,394.7,383.1
XS GIS Cut Line= 3
 2346951.2827224680735.8900777182347547.36560121679934.005575818
2347693.42494166679846.060704335
#Sta/Elev= 30
       0 2751.28    93.1 2749.44   122.6 2743.17   145.5 2741.09   205.6 2744.93
   232.6 2739.36   296.5 2740.62   319.9 2737.68   336.7 2737.55   348.5 2741.32
   363.6 2741.91     480 2740.51   502.9 2738.55   528.6 2740.32   554.3 2739.05
   759.1  2741.6   775.9 2740.59   785.9  2737.9   808.8 2740.34   882.22738.311
   891.7 2736.79     906 2738.16     926 2740.95     941 2739.54   960.3 2751.78
   968.9 2761.05   975.3 2765.79  1009.4 2786.71  1032.4 2798.31  1169.7 2840.97
#Mann= 5 ,-1,0
       0      .1       0     880     .06       0   882.2    .045       0
     906     .06       0  999.17      .1       0
Bank Sta=882.2,906
XS Rating Curve= 0 ,0
Exp/Cntr=0.3,0.1

Type RM Length L Ch R = 1 ,113585  ,406.1,395.4,371.4
XS GIS Cut Line= 4
2346957.37310389680945.4334241852347428.27475458680431.724141493
2347617.22204911680358.5829910442347769.13814063680219.243132643
#Sta/Elev= 30
       0 2751.58    87.1 2751.15     136  2747.5     164    2747   203.2 2741.58
   222.8 2740.79   290.9 2740.19   347.6 2743.83     383 2741.12   401.9 2737.21
     424 2737.44   439.9 2739.74   477.9 2738.72   548.6 2740.89   565.6 2739.09
   605.2 2739.34   619.3  2737.9   752.5 2737.97     774  2735.3   838.3 2734.51
   846.2 2735.51   859.8 2737.96   894.1 2738.48   911.1 2736.48   936.1 2738.64
   976.2 2738.02   990.3 2743.28  1031.8 2768.28  1066.3 2778.92  1105.6 2787.32
#Mann= 5 ,-1,0
       0      .1       0     774    .045       0   846.2      .1       0
  999.49     .06       0 1099.49      .1       0
#XS Ineff= 2 , 0
          346.64 2749.52
Permanent Ineff=
       F       F
Bank Sta=774,846.2
XS Rating Curve= 0 ,0
Exp/Cntr=0.3,0.1

Type RM Length L Ch R = 1 ,113190  ,194.1,193.5,192.5
XS GIS Cut Line= 3
 2347335.9898362681156.305742639 2347899.3626389680527.867344917
2347933.31236736680382.708109267
#Sta/Elev= 30
       0 2743.96    54.2 2743.03    73.2 2741.42   102.1 2743.03   162.1 2740.26
   197.8 2739.91   208.3 2740.83   283.5  2738.9   310.4 2739.67   383.8 2736.93
   479.7  2738.4   498.4 2736.76   551.6 2737.32   577.4 2735.09   600.5  2737.9
   616.6 2735.46   671.4 2735.24   696.3 2735.49   701.4 2736.36   749.3 2735.99
   777.8 2734.23   799.3 2735.59     804 2737.51   820.7 2748.45     838 2756.18
   866.9 2764.07   904.3 2771.63   953.6 2779.17   986.4 2785.84   993.1 2786.12
#Mann= 9 ,-1,0
       0      .1       0      60     .08       0      90      .1       0
     190     .08       0     530      .1       0   671.4    .045       0
   696.3      .1       0     720     .06       0  853.99      .1       0
#XS Ineff= 2 , 0
          208.03 2746.58
Permanent Ineff=
       F       F
Bank Sta=671.4,696.3
XS Rating Curve= 0 ,0
Exp/Cntr(USF)=0,0
Exp/Cntr=0.3,0.1

Type RM Length L Ch R = 1 ,112997  ,131.5,120.4,108.8
XS GIS Cut Line= 3
2347505.01245705681233.2304419022348010.79743039680688.635288834
2348015.78163968680633.079479761
#Sta/Elev= 30
       0 2745.96    16.4 2745.44    30.6 2741.76    43.7 2740.34   175.1 2737.75
   278.5 2737.58     308 2735.86     390 2735.77   410.2 2733.94   421.2 2734.25
   433.7 2736.73   447.7 2735.02     469 2736.24   498.4  2735.5   518.7 2737.14
   539.5 2735.95   551.4 2732.31   586.6 2735.73   621.8 2734.94   638.8 2731.66
   649.7 2733.31   657.1 2732.11   673.1 2732.14   698.2 2733.25   704.3 2735.34
   712.7 2740.27     724 2742.47   754.7 2744.64   782.9 2743.91     799 2744.97
#Mann= 8 ,-1,0
       0      .1       0      30     .12       0     170      .1       0
     270     .08       0     570      .1       0   657.1    .045       0
   673.1      .1       0     700     .06       0
Bank Sta=657.1,673.1
XS Rating Curve= 0 ,0
Exp/Cntr=0.3,0.1

Type RM Length L Ch R = 1 ,112876  ,418.3,417.1,400.6
XS GIS Cut Line= 3
2347703.86496088681330.2938769342348092.10621537680723.171396683
2348077.61806337680632.620446687
#Sta/Elev= 30
       0 2752.99    79.2 2744.01    91.5 2740.01   111.1 2738.19     158  2737.9
   172.2 2738.91   205.5 2737.63     253 2737.75   287.7 2736.24   300.4  2737.2
   310.9 2736.45   333.7 2736.99   342.1 2735.97   365.9 2736.14   390.7 2734.48
   414.4 2734.93   466.6 2733.74   483.2 2732.38   536.8 2733.62   547.3 2732.07
   585.3 2731.45   597.6 2732.01   609.2 2735.01   629.5 2742.78   637.5  2743.9
   713.5 2743.28   738.9 2741.73     751 2743.71   763.2 2743.24   812.3 2744.78
#Mann= 8 ,-1,0
       0      .1       0     140     .08       0     260     .12       0
     380     .08       0     520      .1       0   547.3    .045       0
   597.6      .1       0     700     .06       0
Bank Sta=547.3,597.6
XS Rating Curve= 0 ,0
Exp/Cntr(USF)=0,0
Exp/Cntr=0.3,0.1

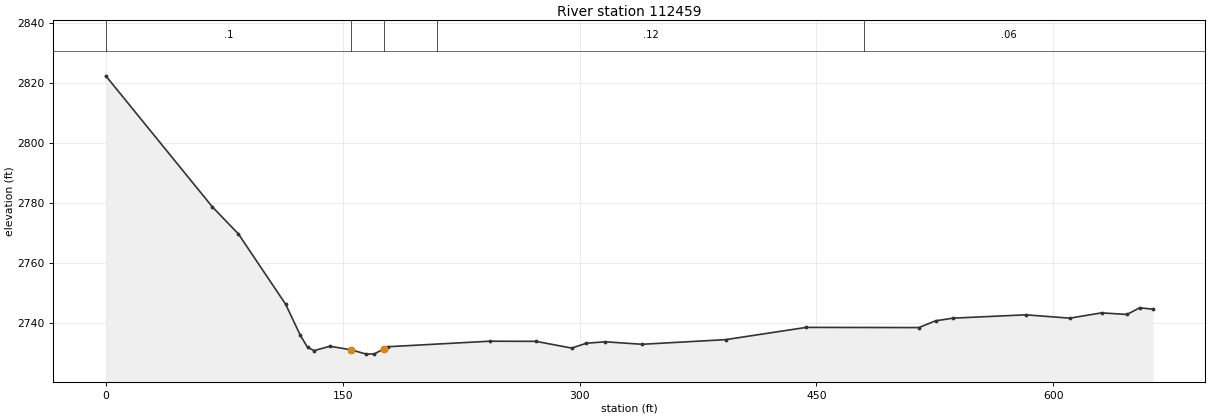
Type RM Length L Ch R = 1 ,112459  ,75.8,73.9,76.9
XS GIS Cut Line= 3
2348382.78933606681231.3338954772348102.87712115  680756.0609723
  2348097.501711680644.710219781
#Sta/Elev= 30
       0 2822.39    67.5 2778.75      84 2769.72   113.9 2746.32   123.2 2735.97
   127.8 2731.96     132 2730.88   141.8 2732.35   155.4 2731.15     165 2729.72
     170  2729.8   175.9 2731.39   178.9 2732.19     243 2734.02   272.3 2733.98
     295 2731.73   304.2 2733.34   316.1 2733.83   339.5    2733   392.4 2734.54
   443.5 2738.62   514.8 2738.56   525.4 2740.81   536.4  2741.7   582.5 2742.81
   610.4  2741.7   630.5 2743.46   646.6 2742.93   654.6 2745.15   663.1 2744.69
#Mann= 5 ,-1,0
       0      .1       0   155.4    .045       0   175.9      .1       0
     210     .12       0     480     .06       0
Bank Sta=155.4,175.9
XS Rating Curve= 0 ,0
Exp/Cntr=0.3,0.1