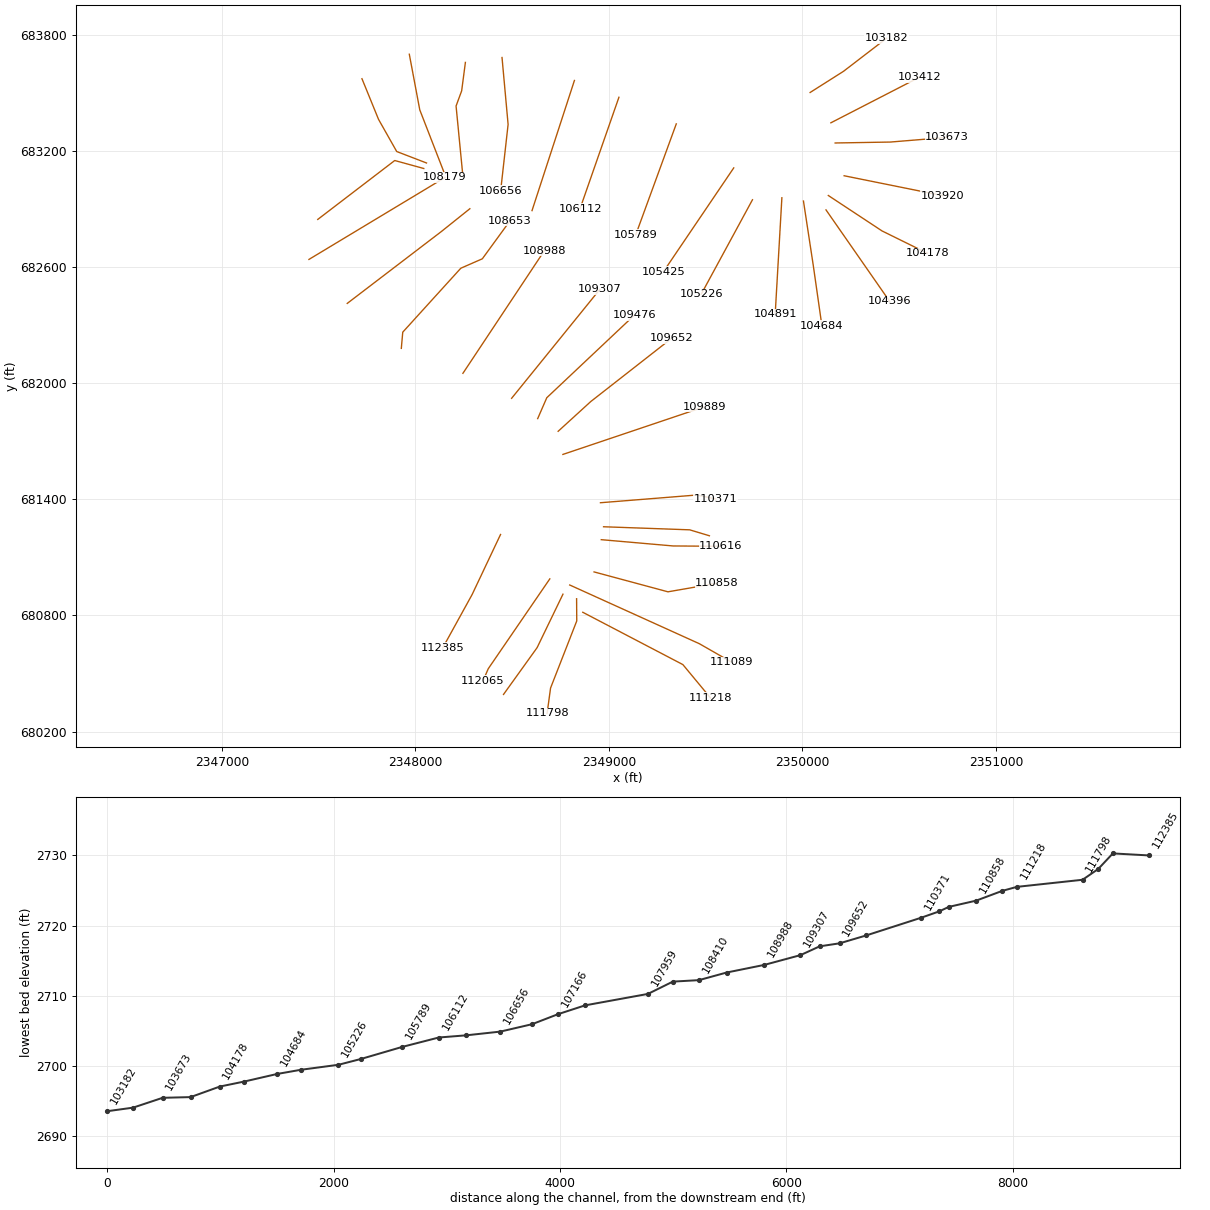
HEC-RAS study GLADYFK.prj: GLADYFK

--- GLADYFK.g01 (geometry) --- (continued)

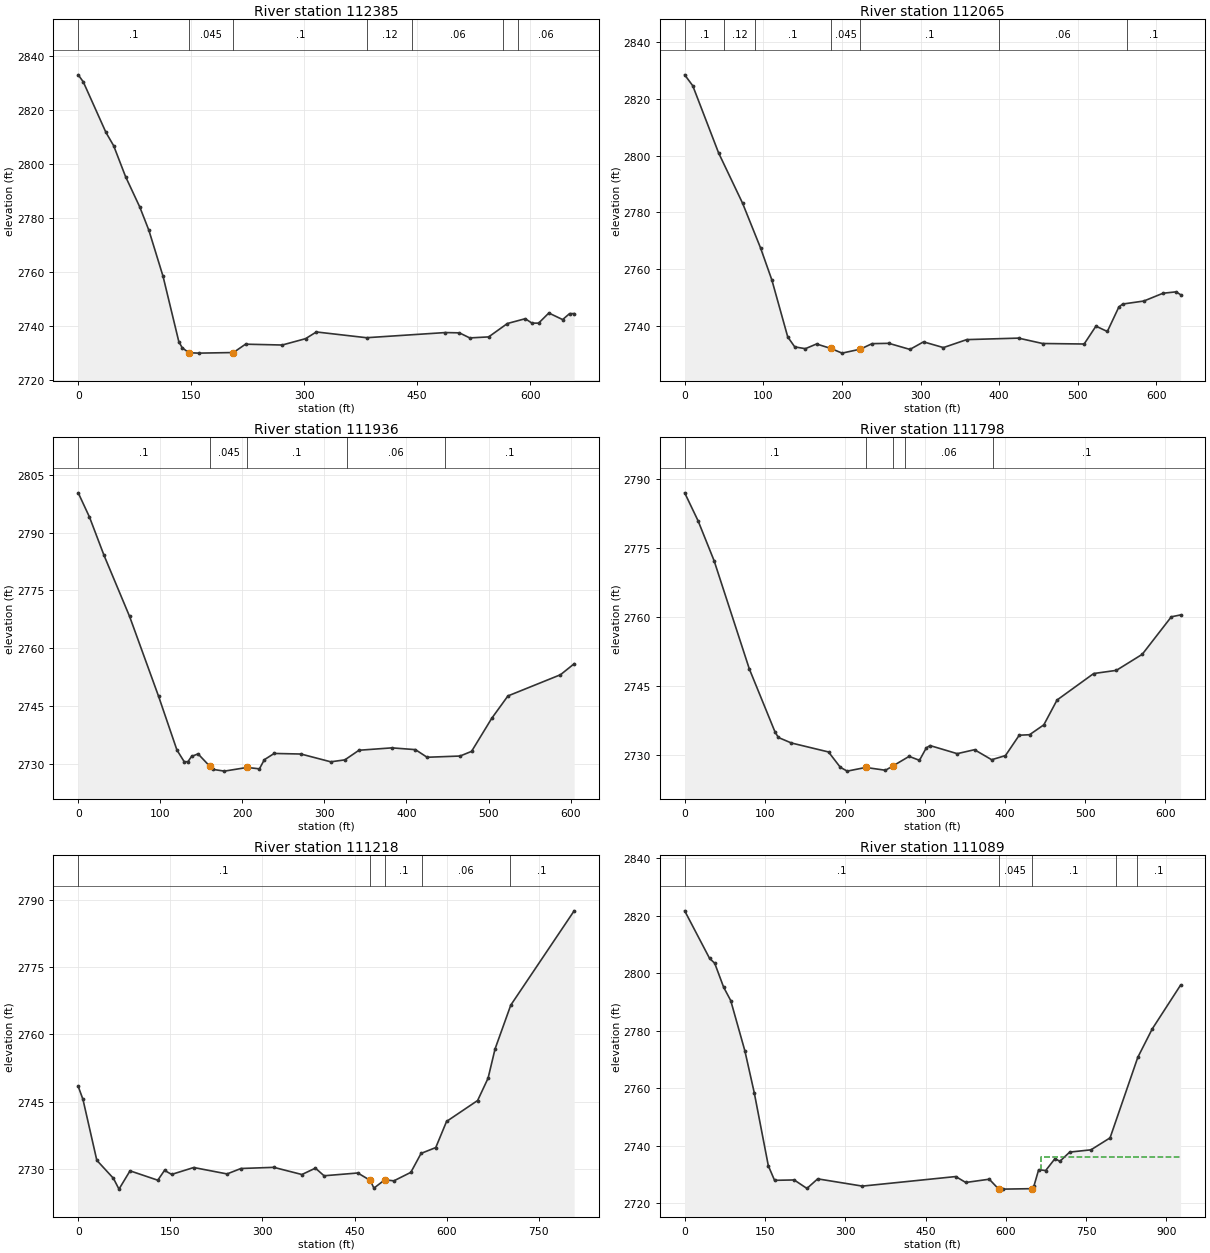
Type RM Length L Ch R = 1 ,112385  ,328.1,319.7,314
XS GIS Cut Line= 3
2348440.33776856681217.9631430282348293.30552947680907.378188537
2348141.38800482680631.754097104
#Sta/Elev= 30
       0 2832.92     6.7 2830.33    36.8 2811.62    47.1 2806.66    62.8  2795.3
    81.8 2783.97    93.8 2775.41   112.6 2758.39   133.6 2734.15   138.1 2731.95
   146.9 2730.11   160.2 2729.97     206 2730.19   222.1 2733.28   270.8 2732.97
   301.8 2735.32   316.1  2737.8   382.7 2735.67   487.4 2737.58     506 2737.47
   519.7  2735.6   544.8 2735.97   569.7 2740.93   593.4  2742.7   602.2 2741.08
   611.1 2741.06   624.7 2744.81     643 2742.38   652.2 2744.58   658.3 2744.59
#Mann= 7 ,-1,0
       0      .1       0   146.9    .045       0     206      .1       0
  383.63     .12       0  443.63     .06       0  563.63      .1       0
  583.63     .06       0
Bank Sta=146.9,206
XS Rating Curve= 0 ,0
Exp/Cntr(USF)=0,0
Exp/Cntr=0.3,0.1

Type RM Length L Ch R = 1 ,112065  ,124.8,129,131.8
XS GIS Cut Line= 3
2348694.93540226680988.7026100072348376.72586467680524.242603749
2348349.99823218680461.980273955
#Sta/Elev= 30
       0 2828.55    10.3 2824.68    43.1    2801    73.6 2783.23    96.6 2767.34
   110.9 2756.09   131.1 2735.97     140 2732.46   153.5 2731.83   167.7 2733.49
   185.8 2731.93   200.2 2730.26   223.2 2731.65   238.4 2733.61   259.7 2733.72
   286.5 2731.57   303.8 2734.24   329.1 2732.22   358.7 2735.03   424.6 2735.56
   455.2 2733.66   508.1 2733.48   523.1 2739.79   537.6  2737.9   552.2 2746.53
     557 2747.59     584 2748.66   608.4 2751.41   625.2 2751.91   630.8 2750.87
#Mann= 7 ,-1,0
       0      .1       0      50     .12       0      90      .1       0
   185.8    .045       0   223.2      .1       0     400     .06       0
  563.01      .1       0
Bank Sta=185.8,223.2
XS Rating Curve= 0 ,0
Exp/Cntr=0.3,0.1

Type RM Length L Ch R = 1 ,111936  ,140.2,138.3,139.5
XS GIS Cut Line= 3
2348762.81254878680909.5046473352348629.10773371 680633.03028397
2348455.71928932680391.605461778
#Sta/Elev= 30
       0  2800.3    13.7 2794.02    31.5 2784.04    62.6 2768.21    97.9 2747.49
   120.3 2733.52   129.2 2730.48   133.7 2730.51   138.1 2731.86     146 2732.53
   160.3 2729.32   164.8 2728.48   178.1 2728.05   205.9 2729.01   220.8 2728.64
   226.8 2731.02   238.8 2732.64   271.4 2732.49   307.7 2730.47   324.9 2730.97
   342.1 2733.47   382.2 2734.09   410.9 2733.63   425.1 2731.65   465.3 2731.97
   479.3 2733.18   503.9 2741.77   523.6 2747.57   587.6 2753.07   604.3 2755.92
#Mann= 5 ,-1,0
       0      .1       0   160.3    .045       0   205.9      .1       0
  327.11     .06       0  447.11      .1       0
Bank Sta=160.3,205.9
XS Rating Curve= 0 ,0
Exp/Cntr(USF)=0,0
Exp/Cntr=0.3,0.1

Type RM Length L Ch R = 1 ,111798  ,563,580.6,598.7
XS GIS Cut Line= 4
2348833.32366924680885.9151068882348834.13726254680771.289205352
2348698.81338779680424.7245267922348680.99279537680293.730588998
#Sta/Elev= 30
       0 2787.05    16.7 2780.97    36.7 2772.29    80.7 2748.73   112.7 2735.05
   116.9 2733.83   133.2 2732.63   179.5 2730.68   194.2 2727.35   202.8 2726.51
   225.9 2727.31   250.6  2726.7   259.8 2727.63   280.1 2729.72     293 2728.86
   301.5 2731.56   306.2 2732.07   340.1 2730.31   361.7 2731.17   383.1 2728.99
   400.3 2729.89   417.5 2734.32   430.4 2734.43   448.2 2736.58   464.7 2741.98
   510.4 2747.74   538.7 2748.43     571 2751.92   607.3 2760.08   618.9 2760.49
#Mann= 5 ,-1,0
       0      .1       0   225.9    .045       0   259.8      .1       0
  274.63     .06       0  384.63      .1       0
Bank Sta=225.9,259.8
XS Rating Curve= 0 ,0
Exp/Cntr=0.3,0.1

Type RM Length L Ch R = 1 ,111218  ,128.5,129,133.1
XS GIS Cut Line= 3
 2348865.3440151680816.1227656292349382.51536893680545.768345148
2349525.52332365680373.228321837
#Sta/Elev= 30
       0 2748.42     7.7 2745.53    30.3 2731.93    57.4  2727.9    66.4  2725.5
    84.4 2729.58   129.6 2727.49   140.6 2729.69   152.1 2728.78   188.1 2730.32
   242.4 2728.89     265  2730.1   318.5 2730.36   364.3 2728.76   386.3 2730.18
   400.4 2728.48   455.3  2729.1   475.6 2727.45   481.6 2725.72   499.3 2727.58
   514.1 2727.35   541.7 2729.24   558.4 2733.47   582.3 2734.77   599.9  2740.6
   650.5 2745.27   667.5 2750.24   678.9 2756.78   704.5 2766.55   807.7 2787.58
#Mann= 5 ,-1,0
       0      .1       0   475.6    .045       0   499.3      .1       0
     560     .06       0  703.57      .1       0
Bank Sta=475.6,499.3
XS Rating Curve= 0 ,0
Exp/Cntr(USF)=0,0
Exp/Cntr=0.3,0.1

Type RM Length L Ch R = 1 ,111089  ,215.1,230.7,249.5
XS GIS Cut Line= 3
2348797.82574875680957.076602105 2349467.8266425      680653.595
     2349633.644      680558.771
#Sta/Elev= 30
       0 2821.66    46.5 2805.14    56.1 2803.45    72.8  2795.1      86 2790.48
   112.4 2773.03   129.9 2758.51   156.3 2733.03   167.9 2727.99   204.6 2728.12
   228.4 2725.17   248.5  2728.5   331.9 2725.98   506.4  2729.3   525.1 2727.24
     569 2728.38   586.6 2724.95   594.1 2724.93   648.5 2725.09   652.5 2726.02
   661.3 2731.68   674.4 2731.39     692 2735.57   700.8 2734.58   719.3  2737.8
     759 2738.59   794.7 2742.75   846.5 2770.74   873.3 2780.56   926.5 2795.86
#Mann= 5 ,-1,0
       0      .1       0   586.6    .045       0   648.5      .1       0
  805.53     .06       0  845.53      .1       0
#XS Ineff= 2 , 0
                          665.65         2735.96
Permanent Ineff=
       F       F
Bank Sta=586.6,648.5
XS Rating Curve= 0 ,0
Exp/Cntr=0.3,0.1

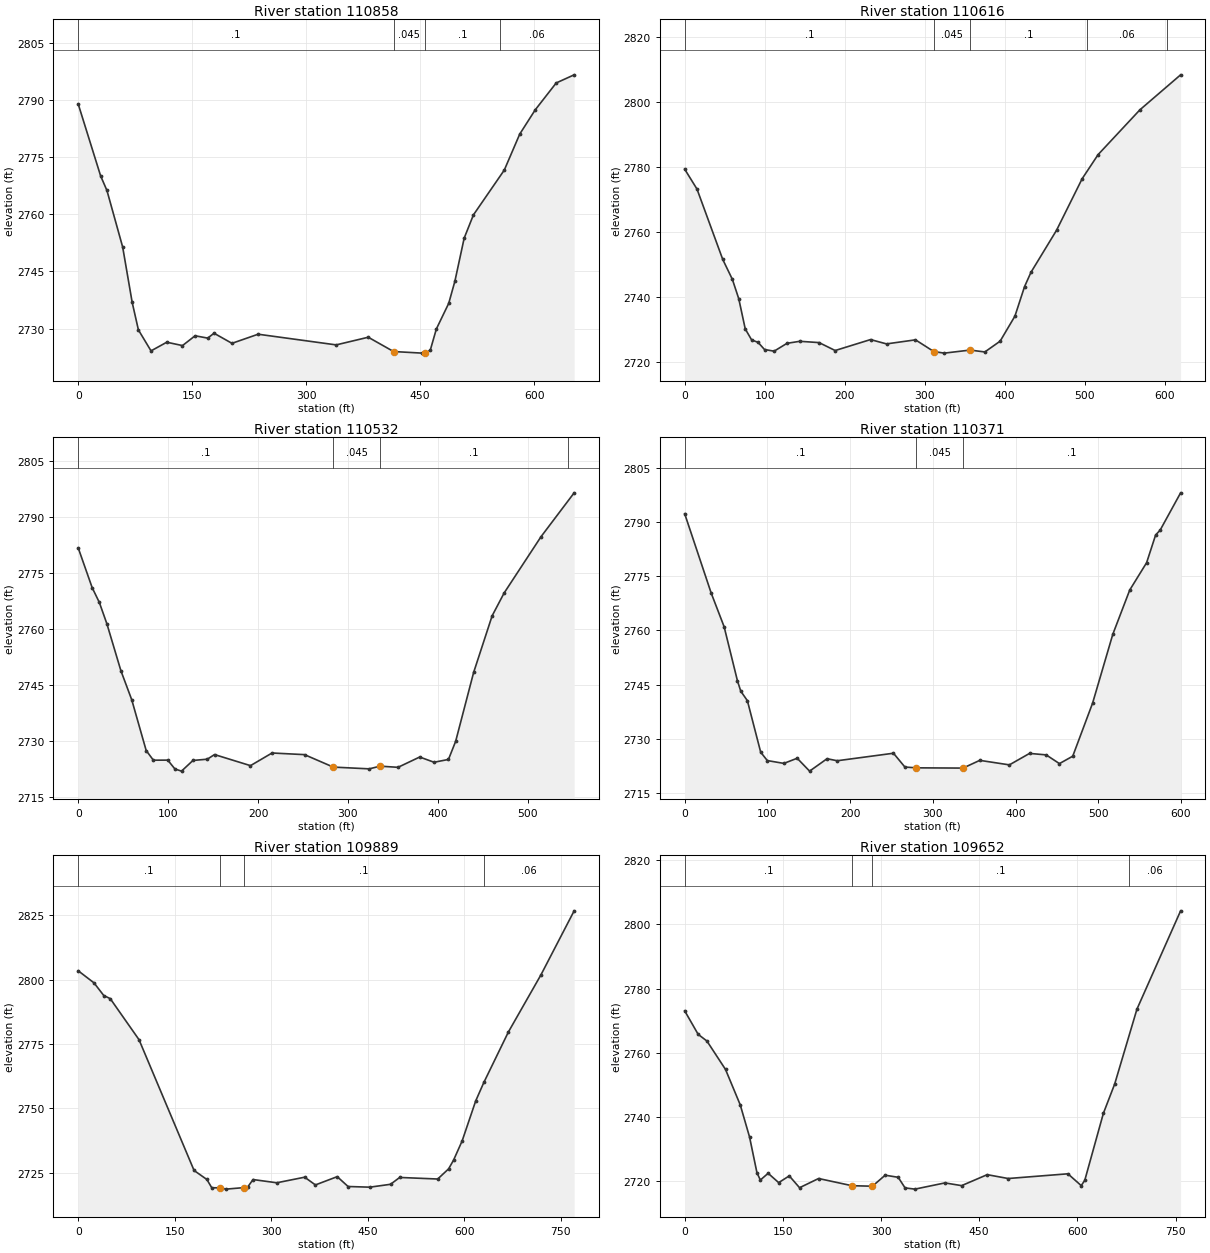
Type RM Length L Ch R = 1 ,110858  ,245.1,241.7,233.5
XS GIS Cut Line= 3
2348923.65669923681024.6307024522349305.46326267 680921.83662768
2349558.77723264680965.891231154
#Sta/Elev= 30
       0 2788.88    29.5 2770.02    37.8  2766.2    58.5 2751.36      71 2736.85
    79.2 2729.63    95.8 2724.13   116.5  2726.4   137.2 2725.52   153.8 2728.09
   170.4 2727.48   178.7 2728.76   202.3 2726.11   236.7  2728.5   339.4  2725.7
   381.6 2727.71   414.9 2723.96   452.5 2723.54     456 2723.59   463.1 2724.24
   471.2 2729.87   487.5 2736.61   495.6 2742.41   507.8  2753.7     520 2759.81
   560.6 2771.56   580.9 2780.99   601.2 2787.33   628.9 2794.41   652.5 2796.54
#Mann= 4 ,-1,0
       0      .1       0   414.9    .045       0     456      .1       0
   555.4     .06       0
Bank Sta=414.9,456
XS Rating Curve= 0 ,0
Exp/Cntr(USF)=0,0
Exp/Cntr=0.3,0.1

Type RM Length L Ch R = 1 ,110616  ,85.1,84.7,86.3
XS GIS Cut Line= 3
2348960.79666919681191.2677027982349331.73216956681158.804649756
2349579.27905073681157.031875609
#Sta/Elev= 30
       0 2779.26    15.4 2773.13    47.6 2751.47    59.6 2745.36    67.6 2739.39
    75.7  2730.1    83.7 2726.71    91.7 2725.97    99.8 2723.76   111.8 2723.25
   127.9 2725.67   143.9 2726.29     168 2725.89   188.1 2723.45   232.3 2726.82
   252.3 2725.49   288.5 2726.74   311.5 2723.12   324.6 2722.65   356.7 2723.59
   375.2 2723.01   394.3 2726.33   412.8 2734.04   424.8  2743.1   432.8  2747.5
   464.8 2760.45   496.8 2776.31   516.8 2783.75     569 2797.52   619.9 2808.29
#Mann= 5 ,-1,0
       0      .1       0   311.5    .045       0   356.7      .1       0
  502.35     .06       0  602.35      .1       0
Bank Sta=311.5,356.7
XS Rating Curve= 0 ,0
Exp/Cntr=0.3,0.1

Type RM Length L Ch R = 1 ,110532  ,158,160.9,163.8
XS GIS Cut Line= 3
2348972.66293224681257.9936080312349417.56817995681242.150148011
2349519.48854578681211.444075084
#Sta/Elev= 30
       0 2781.84    15.5  2771.2    23.5 2767.22    31.9 2761.49    47.5  2748.9
    59.5 2741.16    75.6 2727.53    83.6 2724.94    99.6 2724.96   107.6 2722.58
   114.9 2722.01   127.6 2724.87   143.6 2725.21   151.6 2726.45   191.6 2723.48
   215.6 2726.87   251.7 2726.43   283.7 2723.09   323.7 2722.62   335.7 2723.34
   355.7 2723.03   379.8 2725.79   395.8 2724.39   411.8 2725.14   419.8 2729.99
   439.8 2748.46   460.4 2763.65   473.7 2769.75   514.8 2784.86   551.6  2796.6
#Mann= 4 ,-1,0
       0      .1       0   283.7    .045       0   335.7      .1       0
  545.19     .06       0
Bank Sta=283.7,335.7
XS Rating Curve= 0 ,0
Exp/Cntr(USF)=0,0
Exp/Cntr=0.3,0.1

Type RM Length L Ch R = 1 ,110371  ,457.3,481.5,483.3
XS GIS Cut Line= 3
2348956.61811329 681382.133890732349454.49515475681422.068381519
2349552.37410977 681401.68919717
#Sta/Elev= 30
       0 2792.29    32.1 2770.31    47.7 2761.02    63.8 2746.07    67.8 2743.22
    75.8 2740.58    91.9 2726.33    99.9 2724.02   119.9 2723.24     136 2724.66
     151  2721.1   172.1 2724.53   184.4 2723.97   252.4 2726.05   266.2 2722.23
   279.92722.011   336.5 2721.94   356.7 2724.08   392.5 2722.83   416.9    2726
     437 2725.59     453 2723.18   469.1 2725.23   493.1 2739.91   517.5 2758.93
     538 2771.19   558.4 2778.75   569.3 2786.42   574.7 2787.73   599.5 2798.07
#Mann= 3 ,-1,0
       0      .1       0   279.9    .045       0   336.5      .1       0
Bank Sta=279.9,336.5
XS Rating Curve= 0 ,0
Exp/Cntr=0.3,0.1

Type RM Length L Ch R = 1 ,109889  ,231.2,236.8,240.2
XS GIS Cut Line= 2
2348762.59432344681631.7212342152349493.16649772681877.692770277
#Sta/Elev= 30
       0 2803.49    24.5  2798.8    39.7 2793.88    49.8 2792.66    94.5 2776.71
   180.1 2725.85     200 2722.35   207.6 2719.13   220.3 2719.11   229.7  2718.6
   258.2  2719.2   263.3 2719.38   271.8 2722.32   308.7 2721.07     352 2723.24
   368.7 2720.23   402.6 2723.45   419.5 2719.62   453.3 2719.36   485.5 2720.48
   499.7 2723.14   558.8 2722.53   575.7 2726.47   583.4 2729.84   596.8 2737.35
   617.9 2752.92   630.5 2760.06   668.6 2779.66   719.2 2801.87   770.9  2826.8
#Mann= 4 ,-1,0
       0      .1       0   220.3    .045       0   258.2      .1       0
     630     .06       0
Bank Sta=220.3,258.2
XS Rating Curve= 0 ,0
Exp/Cntr(USF)=0,0
Exp/Cntr=0.3,0.1

Type RM Length L Ch R = 1 ,109652  ,173.5,176.3,176.7
XS GIS Cut Line= 3
2348738.06765381681751.3044665422348906.74418549681905.105913981
2349323.78726973 682231.20688886
#Sta/Elev= 30
       0 2773.08    20.6 2765.74      34 2763.65    62.4 2754.79    84.9 2743.74
    99.1 2733.74   110.4  2722.6   115.6  2720.3   127.5 2722.41   143.6  2719.5
   159.8  2721.6   175.5 2717.91   204.6 2720.78   255.5 2718.54   286.8 2718.38
   306.3 2721.81   326.2 2721.16   336.7 2717.85   351.8 2717.47   397.6 2719.41
   423.1 2718.56   462.2 2721.98   494.3 2720.78   585.5 2722.25   605.8 2718.57
   611.2 2720.17   639.7 2741.11     657 2750.27     691 2773.61   757.7 2804.26
#Mann= 4 ,-1,0
       0      .1       0   255.5    .045       0   286.8      .1       0
  678.27     .06       0
Bank Sta=255.5,286.8
XS Rating Curve= 0 ,0
Exp/Cntr=0.3,0.1

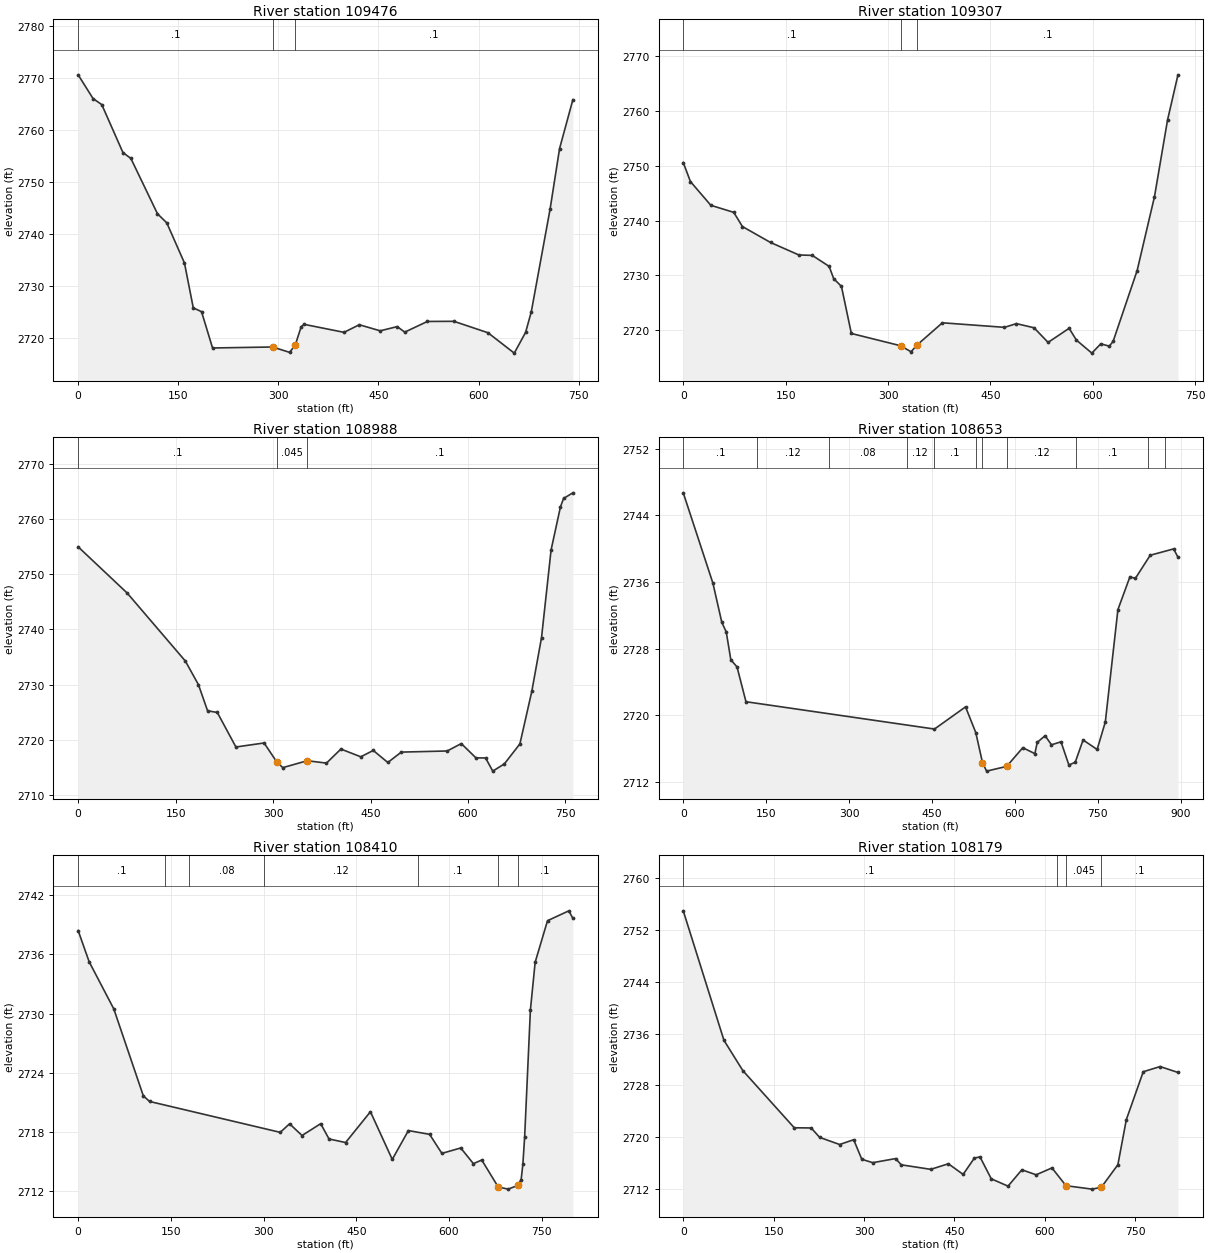
Type RM Length L Ch R = 1 ,109476  ,167,169.4,170.2
XS GIS Cut Line= 3
2348632.28412543681816.7562146282348679.23211945681924.591525407
2349133.04895786682352.440729075
#Sta/Elev= 30
       0 2770.57    22.3 2766.01    35.4 2764.84    67.1 2755.62      79 2754.49
   118.9 2743.84   132.8  2742.1   159.3 2734.38   172.5 2725.75   184.9 2725.01
   201.4 2718.03   291.3 2718.22   316.8 2717.19   325.3 2718.58   334.2 2722.12
   338.8 2722.57   398.4 2721.04   421.3  2722.5   452.6 2721.33   478.1 2722.14
   489.4 2721.08   523.3 2723.13     563 2723.16   614.1 2720.96   653.5 2717.04
   670.5 2721.03     679 2724.98   707.3 2744.82   721.4 2756.39   741.3 2765.78
#Mann= 3 ,-1,0
       0      .1       0   291.3    .045       0   325.3      .1       0
Bank Sta=291.3,325.3
XS Rating Curve= 0 ,0
Exp/Cntr(USF)=0,0
Exp/Cntr=0.3,0.1

Type RM Length L Ch R = 1 ,109307  ,320.3,319.1,319.2
XS GIS Cut Line= 2
2348497.58693496 681921.764689562348953.79946509682485.079558454
#Sta/Elev= 30
       0  2750.6    10.5 2747.13    40.4 2742.79      74  2741.5    86.7 2738.91
   127.9    2736   169.4 2733.72   189.1 2733.64   213.8 2731.63   220.4  2729.4
   231.8 2727.98   246.3 2719.38   318.4 2717.14   333.8 2716.04   342.7 2717.29
   379.7 2721.33   470.7  2720.5   488.2 2721.18     514 2720.42   534.6 2717.75
   565.4 2720.32   576.1 2718.17   598.7 2715.79   611.8 2717.49   624.3 2717.06
   629.9 2717.94   665.1 2730.88   690.5 2744.37   709.6 2758.35   724.9 2766.62
#Mann= 3 ,-1,0
       0      .1       0   318.4    .045       0   342.7      .1       0
Bank Sta=318.4,342.7
XS Rating Curve= 0 ,0
Exp/Cntr=0.3,0.1

Type RM Length L Ch R = 1 ,108988  ,352.2,334.1,326.5
XS GIS Cut Line= 2
2348245.96225807682050.7744166962348667.11530801682685.038103233
#Sta/Elev= 30
       0 2754.94    75.5 2746.58   164.9 2734.31   185.1 2730.04   199.2 2725.31
   214.2    2725   242.8 2718.76   286.2 2719.49   305.4 2716.11     315 2715.03
   352.5 2716.28   382.2 2715.85   404.4 2718.39     435 2716.99   454.2 2718.14
   476.6 2715.96   497.4 2717.84     568 2718.04   589.7 2719.38   612.2  2716.8
   627.1 2716.78   638.1  2714.4   655.9  2715.7   679.9 2719.32   698.2 2728.81
   713.2 2738.55   727.9 2754.38   742.3 2762.15   747.1 2763.68   761.4  2764.7
#Mann= 3 ,-1,0
       0      .1       0   305.4    .045       0   352.5      .1       0
Bank Sta=305.4,352.5
XS Rating Curve= 0 ,0
Exp/Cntr(USF)=0,0
Exp/Cntr=0.3,0.1

Type RM Length L Ch R = 1 ,108653  ,243.1,243.8,248.8
XS GIS Cut Line= 5
2347927.65361575682179.6652561362347935.07601052682263.418687094
2348235.04980235682593.8347265312348346.20982566682642.503107911
2348489.75400129682839.459883907
#Sta/Elev= 30
       0 2746.71    53.7 2735.86    69.8 2731.16    77.8 2730.02    86.1 2726.67
    97.3 2725.82   113.5 2721.64   454.7 2718.36   510.9 2721.02   529.5 2717.93
   541.6 2714.33     549 2713.31   585.4 2713.88   614.5 2716.12   636.4 2715.41
   640.7 2716.76   654.9 2717.56   666.5 2716.47   683.7 2716.83     698 2714.04
   709.5 2714.38   723.7 2717.05   749.1 2715.91   763.9  2719.2   786.7 2732.69
   808.5 2736.64   818.2 2736.43   845.2 2739.22   887.6 2739.98   895.4 2738.98
#Mann= 11 ,-1,0
       0      .1       0  134.08     .12       0  264.08     .08       0
  404.08     .12       0  454.08      .1       0  530.35     .12       0
   541.6    .045       0   585.4     .12       0   711.7      .1       0
   841.7     .12       0   871.7      .1       0
Bank Sta=541.6,585.4
XS Rating Curve= 0 ,0
Exp/Cntr=0.3,0.1

Type RM Length L Ch R = 1 ,108410  ,239.3,230.5,226
XS GIS Cut Line= 3
2347648.31896414682412.0879545012348134.49158341682783.384721652
2348281.79349831682901.226253578
#Sta/Elev= 30
       0 2738.42    17.8 2735.26    57.7 2730.48   105.5 2721.67   115.6 2721.11
     327 2717.98   342.1 2718.85   362.2 2717.66   392.4 2718.86   405.9 2717.31
   432.7 2716.95   472.9 2720.07   508.2 2715.24   534.3 2718.16   568.6 2717.78
   588.5 2715.85     619  2716.4   639.5 2714.81     653 2715.18   679.7 2712.44
   695.9 2712.23     711  2712.6   716.7 2713.18   719.5 2714.73   722.4 2717.51
   731.7 2730.36   739.4 2735.21   759.4 2739.42   793.9 2740.42   800.4 2739.66
#Mann= 7 ,-1,0
       0      .1       0     140     .12       0     180     .08       0
     300     .12       0     550      .1       0   679.7    .045       0
     711      .1       0
Bank Sta=679.7,711
XS Rating Curve= 0 ,0
Exp/Cntr(USF)=0,0
Exp/Cntr=0.3,0.1

Type RM Length L Ch R = 1 ,108179  ,211.5,220,222
XS GIS Cut Line= 2
2347450.34304726682639.2888906222348153.55893982683062.822035162
#Sta/Elev= 30
       0 2754.93    67.5 2734.97    98.9 2730.29   184.2 2721.48   212.3 2721.45
   226.3    2720   259.5  2718.9   282.8 2719.64   296.3 2716.62   314.5  2716.1
   352.4 2716.73   361.7 2715.77   410.7 2715.07   439.9 2715.93   464.4 2714.29
   483.1 2716.81   492.4 2716.99   511.1 2713.61   538.9 2712.48   561.9    2715
   585.6 2714.23   611.8 2715.29   635.1 2712.55   678.2 2712.02   693.7  2712.3
   721.2 2715.78   735.2 2722.73   763.3 2730.12   791.3 2730.92   820.9 2730.01
#Mann= 4 ,-1,0
       0      .1       0     620     .12       0   635.1    .045       0
   693.7      .1       0
Bank Sta=635.1,693.7
XS Rating Curve= 0 ,0
Exp/Cntr=0.3,0.1

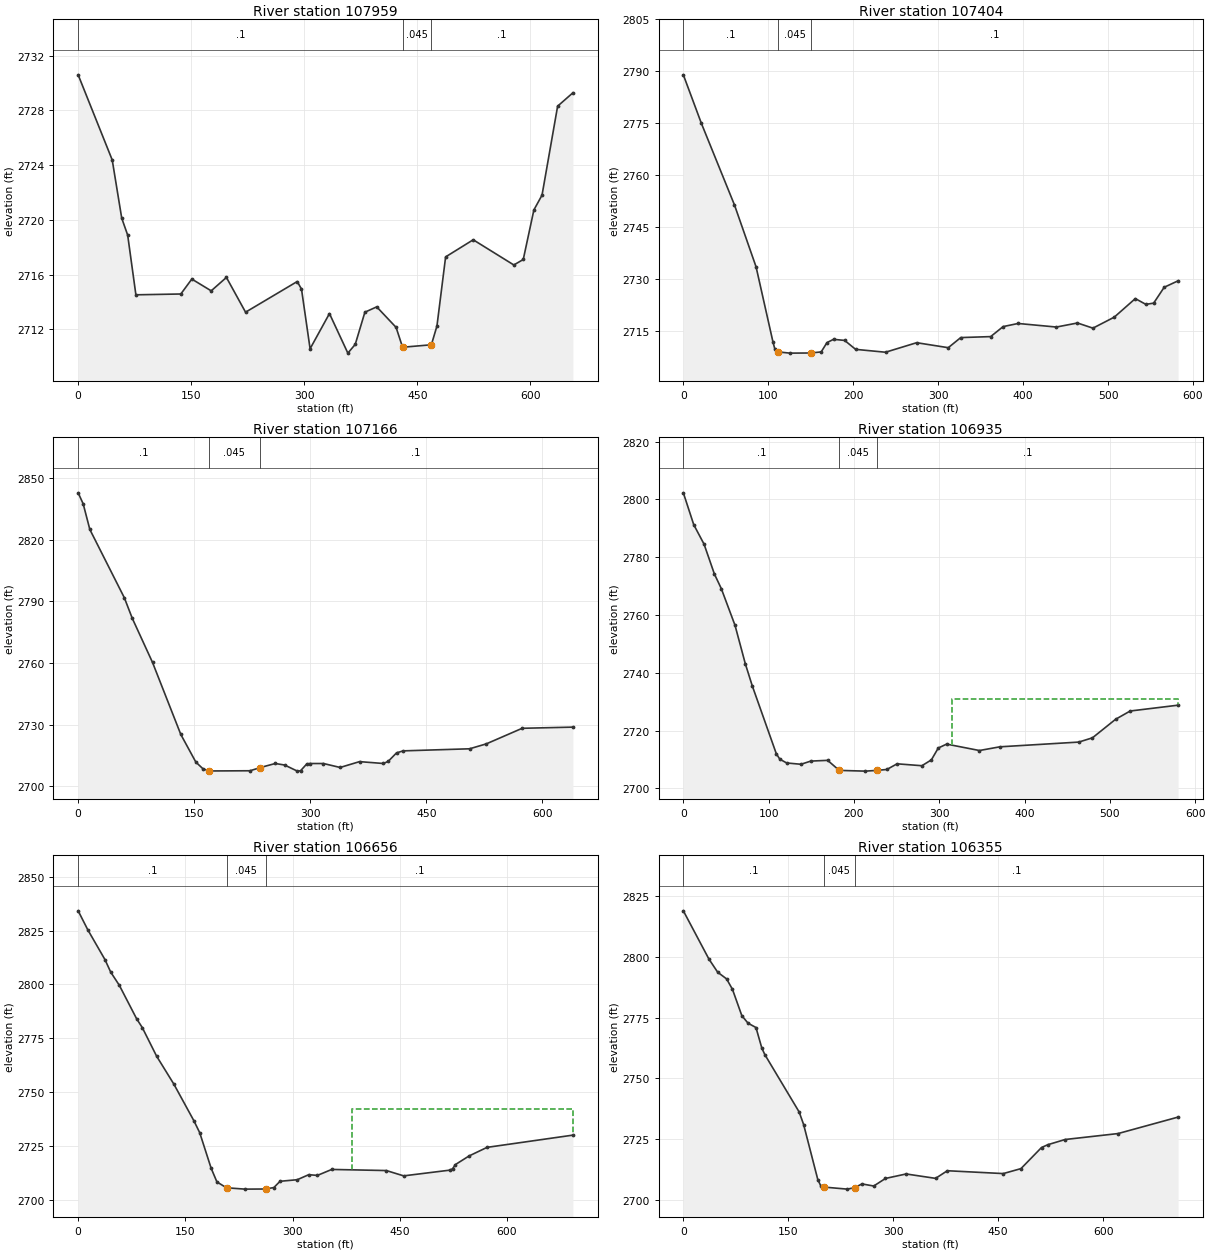
Type RM Length L Ch R = 1 ,107959  ,589,555.5,520.7
XS GIS Cut Line= 3
2347495.96731736682846.0437422922347893.72902133683150.359758313
2348043.69907494683109.121018227
#Sta/Elev= 30
       0  2730.6    45.2 2724.38    57.8 2720.13    65.7 2718.89    76.6 2714.53
   136.2 2714.59   150.8 2715.68   176.5 2714.82   196.7  2715.8   222.1 2713.26
   290.6  2715.5   296.3 2714.95   307.7 2710.59   333.4 2713.16   357.8 2710.27
   367.6 2710.91   380.4 2713.26   396.1 2713.65   421.8 2712.15   430.4  2710.7
   468.6 2710.88     476 2712.25   487.5  2717.3   524.1 2718.55     578 2716.71
   590.5 2717.11   604.6 2720.73   615.4 2721.81   636.1 2728.31   656.4 2729.29
#Mann= 3 ,-1,0
       0      .1       0   430.4    .045       0   468.6      .1       0
Bank Sta=430.4,468.6
XS Rating Curve= 0 ,0
Exp/Cntr(USF)=0,0
Exp/Cntr=0.3,0.1

Type RM Length L Ch R = 1 ,107404  ,242.4,238,234.3
XS GIS Cut Line= 4
2347724.34245683683572.9311574112347809.98460598 683362.84026027
2347903.95858572683196.7893774822348057.78198795683137.658095171
#Sta/Elev= 30
       0 2788.98    21.3 2774.93    60.2 2751.41    85.6 2733.57   105.5 2711.88
   107.7 2709.84     112 2708.98   125.5 2708.64     150 2708.68   162.3 2708.99
   169.1 2711.68   176.8 2712.62   189.9 2712.31   202.8 2709.73     238  2708.9
   274.7 2711.65   311.9 2710.21   326.6 2713.13   361.8 2713.41   376.5  2716.3
   394.1  2717.2   439.2 2716.17     464 2717.34   482.2 2715.85   507.3 2719.02
   532.1 2724.38   544.5 2722.72   553.7 2723.07   566.1 2727.65   582.5 2729.52
#Mann= 3 ,-1,0
       0      .1       0     112    .045       0     150      .1       0
Bank Sta=112,150
XS Rating Curve= 0 ,0
Exp/Cntr(USF)=0,0
Exp/Cntr=0.3,0.1

Type RM Length L Ch R = 1 ,107166  ,241,230.2,208.5
XS GIS Cut Line= 3
     2347968.923      683699.5782348022.97000664683412.223165468
2348148.56715773  683088.6497161
#Sta/Elev= 30
       0 2842.72     6.5 2837.36    15.1  2824.9    59.7 2791.69    69.9 2781.75
    96.1 2760.26   132.7 2725.21   152.1 2711.79   161.2 2708.57   169.3 2707.47
   222.2 2707.57   234.4 2709.01   234.4 2709.03   254.8  2711.1     267 2710.34
   283.3 2707.39   287.4 2707.56   295.6 2710.93   299.9 2711.09   317.1 2711.09
   338.6 2709.17   363.7 2712.01   394.6  2711.1   400.8 2712.16   411.5 2716.26
   420.1 2717.24   505.9 2718.25   527.5 2720.64   573.9 2728.22   639.5 2728.79
#Mann= 3 ,-1,0
       0      .1       0   169.3    .045       0   234.4      .1       0
Bank Sta=169.3,234.4
XS Rating Curve= 0 ,0
Exp/Cntr=0.3,0.1

Type RM Length L Ch R = 1 ,106935  ,268.8,279.4,287.2
XS GIS Cut Line= 4
 2348258.7233815683657.2900717342348239.45389794683510.360259593
 2348210.5496726683432.0779826332348244.27126883683085.227278563
#Sta/Elev= 30
       0 2802.25    12.2 2791.22    24.3 2784.48    36.4 2774.17    44.5 2769.11
    60.6  2756.4    72.7 2743.07    80.8 2735.48     109 2711.98   113.1  2710.1
   121.1 2708.79   137.9 2708.33   149.4 2709.43   169.2 2709.69   182.8 2706.21
   213.4 2705.96   226.9 2706.21   238.6 2706.53   250.6 2708.49   279.7 2707.83
   290.8 2709.85   298.9 2713.96   308.7 2715.31   347.1 2713.09   371.1 2714.37
   463.6 2716.01   479.7 2717.49   506.8  2723.9   523.9 2726.76   580.1 2728.78
#Mann= 3 ,-1,0
       0      .1       0   182.8    .045       0   226.9      .1       0
#XS Ineff= 2 , 0
                          314.75         2731.06
Permanent Ineff=
       F       F
Bank Sta=182.8,226.9
XS Rating Curve= 0 ,0
Exp/Cntr(USF)=0,0
Exp/Cntr=0.3,0.1

Type RM Length L Ch R = 1 ,106656  ,316.8,301,294.2
XS GIS Cut Line= 3
     2348448.009      683682.5632348479.41600664683336.903165468
 2348440.9120321682993.699484225
#Sta/Elev= 30
       0  2834.2    13.4 2825.44    37.5 2811.55    45.6 2805.71    57.6 2799.61
    81.7 2784.13    89.8 2779.93   109.8 2766.67   133.9 2753.71     162 2736.65
   170.1 2731.14   186.1 2714.62   194.2 2708.25   207.6 2705.54   233.4 2704.91
   262.5 2704.97   273.9 2705.65   282.5 2708.55   306.6 2709.28   322.7 2711.62
   334.8 2711.28   354.9 2714.06   431.3 2713.54   455.5 2711.07   519.9 2713.72
   523.9 2714.34   527.9 2716.31   547.1 2720.33   572.2 2724.31   692.4    2730
#Mann= 3 ,-1,0
       0      .1       0   207.6    .045       0   262.5      .1       0
#XS Ineff= 2 , 0
                          382.65         2742.04
Permanent Ineff=
       F       F
Bank Sta=207.6,262.5
XS Rating Curve= 0 ,0
Exp/Cntr=0.3,0.1

Type RM Length L Ch R = 1 ,106355  ,243,242.5,244
XS GIS Cut Line= 2
2348822.08710397683563.904079368 2348603.0227177682891.603031843
#Sta/Elev= 30
       0 2818.91    36.5 2799.09    49.1 2793.64    61.8  2790.9    70.2  2786.6
    83.6 2775.76    92.5 2772.66   103.8 2770.88   112.2 2762.39   116.5 2759.72
   165.5 2736.14   171.9 2730.96   192.2 2708.27   196.4 2705.74     201 2705.22
   234.3 2704.38   244.8 2704.98   255.3 2706.52   272.1 2705.66   288.9 2708.78
   318.4 2710.62   360.5 2708.81   377.3 2711.95   457.2 2710.78   482.5 2712.82
   511.9 2721.51   520.9 2722.66   545.6  2724.8   621.3 2727.25   707.1 2734.03
#Mann= 3 ,-1,0
       0      .1       0     201    .045       0   244.8      .1       0
Bank Sta=201,244.8
XS Rating Curve= 0 ,0
Exp/Cntr(USF)=0,0
Exp/Cntr=0.3,0.1

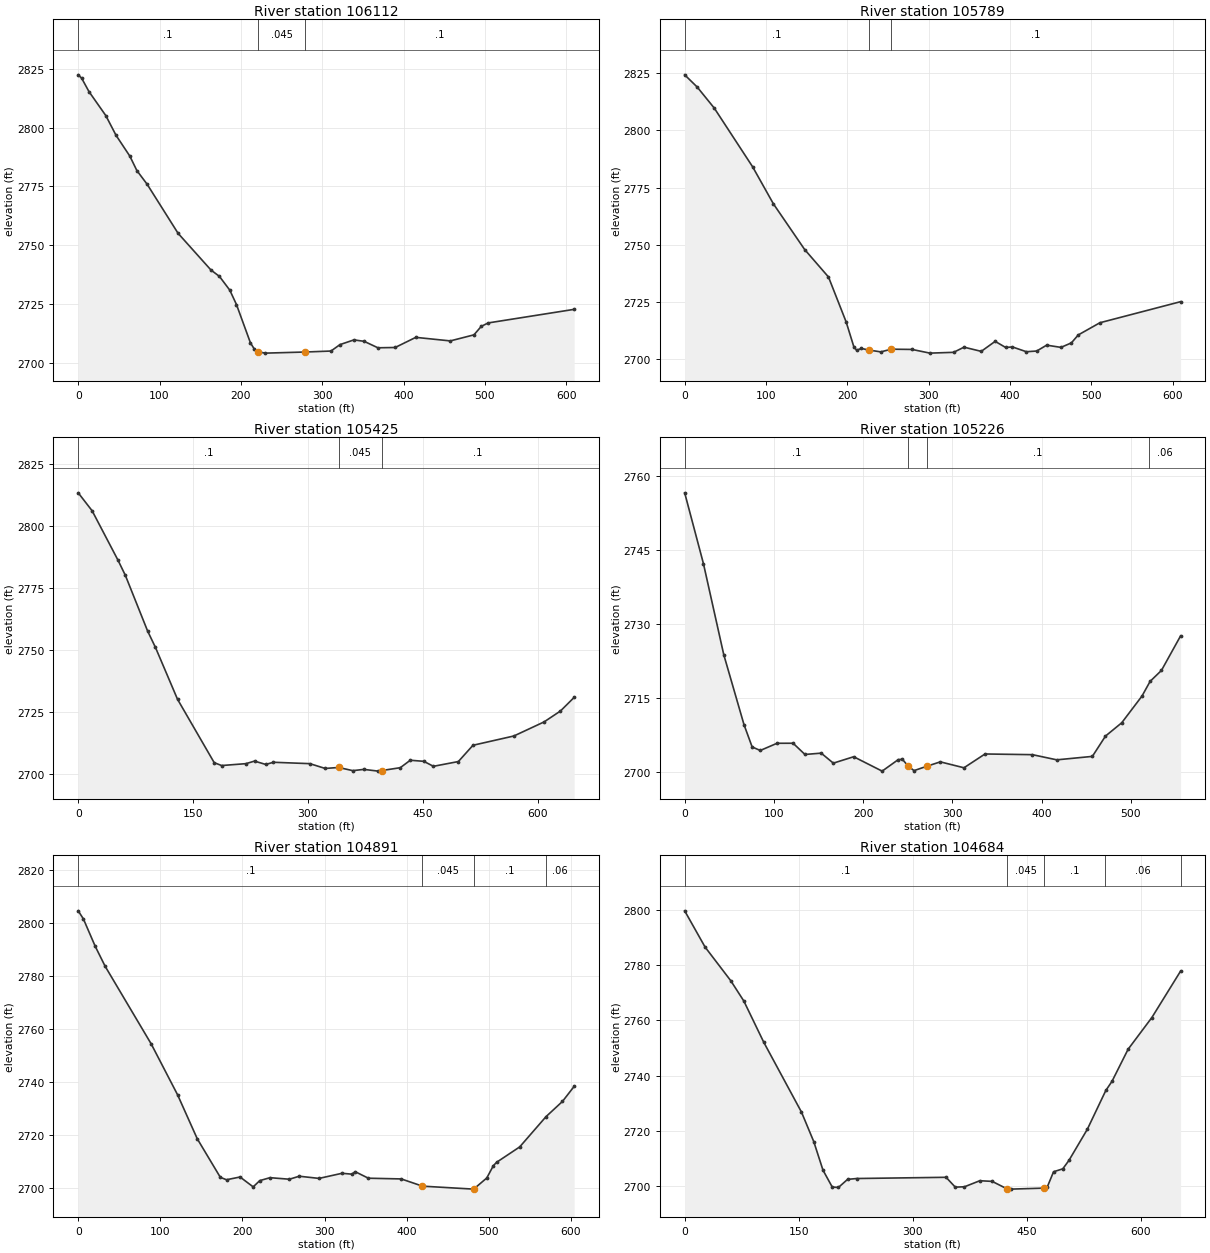
Type RM Length L Ch R = 1 ,106112  ,324.5,323.7,322.5
XS GIS Cut Line= 2
2349052.01305402683477.1414790152348851.10737909 682901.39156526
#Sta/Elev= 30
       0  2822.5     4.2 2821.08    13.2 2815.38    33.9 2805.17    46.6 2796.71
    63.5 2787.89    72.1 2781.77    84.7 2775.96   122.8 2755.05   163.2 2739.45
   173.7  2736.7   186.4 2730.86   194.6 2724.74   211.8 2708.42   216.5 2705.82
   221.4 2704.59   230.2 2704.07   278.8 2704.54   310.8 2704.96   321.9  2707.7
     339  2709.7   351.6 2709.09   368.5 2706.34   389.7 2706.47   415.1 2710.78
   457.5 2709.27   486.6 2711.85   495.6 2715.46   504.1 2716.92   609.8  2722.7
#Mann= 3 ,-1,0
       0      .1       0   221.4    .045       0   278.8      .1       0
Bank Sta=221.4,278.8
XS Rating Curve= 0 ,0
Exp/Cntr=0.3,0.1

Type RM Length L Ch R = 1 ,105789  ,359.3,363.3,367.4
XS GIS Cut Line= 2
2349348.37705957683339.6757483452349139.11769307682766.965903187
#Sta/Elev= 30
       0 2824.25    15.4 2818.91    36.4 2809.71    83.6 2784.05   109.1  2767.9
   147.5 2747.97   176.8 2735.97   198.5 2716.36     208 2705.47   211.3 2704.02
   217.3 2704.76   226.7 2704.07   241.1 2703.27   253.9 2704.45   279.5 2704.34
   301.5 2702.73   330.6 2703.08   343.4 2705.33   364.6  2703.5   381.7 2707.87
   394.5 2705.22     403 2705.42   420.1 2703.34   432.8 2703.65     445 2706.21
   462.6 2705.24   475.4  2707.2   483.9 2710.68   510.5    2716   609.7  2725.2
#Mann= 3 ,-1,0
       0      .1       0   226.7    .045       0   253.9      .1       0
Bank Sta=226.7,253.9
XS Rating Curve= 0 ,0
Exp/Cntr(USF)=0,0
Exp/Cntr=0.3,0.1

Type RM Length L Ch R = 1 ,105425  ,197.6,199.1,204.2
XS GIS Cut Line= 2
2349645.29211112683112.2082827512349282.13760384682576.069795096
#Sta/Elev= 30
       0 2813.47    18.2  2806.2      52 2786.22    61.6  2780.1    90.6 2757.64
   100.9 2750.98   129.7 2730.04   177.6 2704.43   187.3 2703.28     219 2704.04
   230.2 2705.07   244.9 2703.72   254.9  2704.6   302.5 2704.04   322.5  2702.1
     340  2702.5   358.6 2701.21   372.9 2701.72   391.8 2701.02   396.5 2701.26
   420.6 2702.41   433.6 2705.42   451.3 2704.98   463.8 2702.97   496.4 2704.89
   515.5 2711.47   568.9 2715.22   608.3  2720.9   629.7 2725.31   647.6 2730.81
#Mann= 3 ,-1,0
       0      .1       0     340    .045       0   396.5      .1       0
Bank Sta=340,396.5
XS Rating Curve= 0 ,0
Exp/Cntr(USF)=0,0
Exp/Cntr=0.3,0.1

Type RM Length L Ch R = 1 ,105226  ,314.7,335.1,351.1
XS GIS Cut Line= 2
2349742.10073357682947.6512791572349476.99982644682459.110229914
#Sta/Elev= 30
       0 2756.66      21 2742.31    43.8 2723.82    66.5 2709.61    75.6  2705.1
    84.7 2704.38   103.5 2705.84   121.5 2705.85   134.8 2703.57     153 2703.84
   166.6 2701.81   189.4 2703.11   221.3 2700.19   239.3 2702.52     244 2702.59
   250.1 2701.29     257 2700.29   271.7  2701.2   286.5 2702.07     313 2700.87
   336.6 2703.67   389.7 2703.53     417 2702.48   456.9 2703.18   471.6  2707.3
   489.8    2710   512.5 2715.42   521.6  2718.4   534.3 2720.62   555.8 2727.64
#Mann= 4 ,-1,0
       0      .1       0   250.1    .045       0   271.7      .1       0
     520     .06       0
Bank Sta=250.1,271.7
XS Rating Curve= 0 ,0
Exp/Cntr=0.3,0.1

Type RM Length L Ch R = 1 ,104891  ,201.1,207.5,210.6
XS GIS Cut Line= 2
2349894.05051134682957.959353511 2349859.3575111682354.961968464
#Sta/Elev= 30
       0 2804.53     6.3 2801.48    20.8 2791.08    32.8 2783.59    88.9 2754.28
     121 2735.09     145 2718.47   173.1 2703.92   180.6 2703.01   197.1 2704.05
   213.1 2700.32   221.1 2702.68   233.6 2703.79   257.2 2703.21   269.2 2704.34
   293.3 2703.52   321.3 2705.45   333.3 2705.12   337.3 2706.06   353.4 2703.59
   393.4 2703.32   419.3 2700.59   481.6 2699.47   497.6 2703.68   505.6 2708.32
   509.6 2709.61   537.7 2715.41   569.7 2726.82   589.8 2732.59     604 2738.26
#Mann= 4 ,-1,0
       0      .1       0   419.3    .045       0   481.6      .1       0
     570     .06       0
Bank Sta=419.3,481.6
XS Rating Curve= 0 ,0
Exp/Cntr(USF)=0,0
Exp/Cntr=0.3,0.1

Type RM Length L Ch R = 1 ,104684  ,275.2,288.2,293.8
XS GIS Cut Line= 3
2350005.49429324682941.0382790352350055.62666647682612.316143956
2350100.91235024682295.810339123
#Sta/Elev= 30
       0  2799.6    26.8  2786.5    60.6 2774.31    77.8 2766.96     104 2752.04
   153.6 2726.77   169.8 2716.07   181.9 2705.75   194.1 2699.63   202.2 2699.48
   214.3 2702.42   226.4 2702.72   343.8 2703.16   355.9  2699.6     368 2699.73
   388.2 2701.92   404.4 2701.69   424.2 2698.95   428.6 2698.88   473.1 2699.25
   477.1 2699.78   485.2 2705.17   497.3 2706.22   505.4 2709.27   529.6 2720.54
   553.9 2734.58     562 2737.87   583.2 2749.49   614.5 2760.99   652.3  2777.8
#Mann= 5 ,-1,0
       0      .1       0   424.2    .045       0   473.1      .1       0
  552.52     .06       0  652.25      .1       0
Bank Sta=424.2,473.1
XS Rating Curve= 0 ,0
Exp/Cntr=0.3,0.1

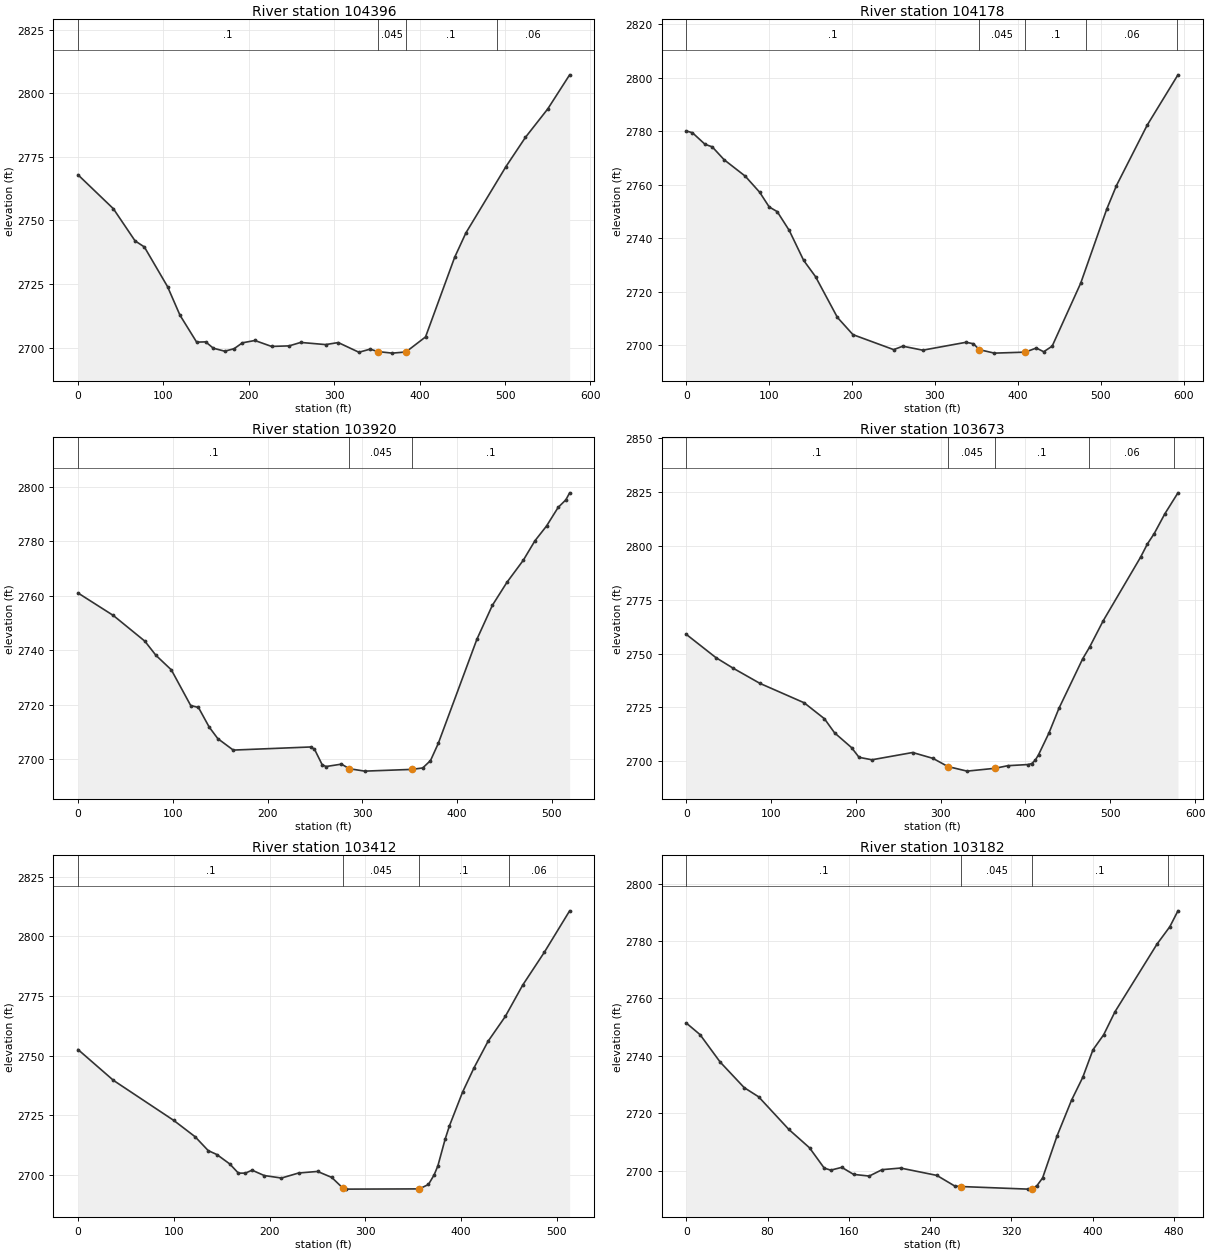
Type RM Length L Ch R = 1 ,104396  ,202.7,217.5,223.2
XS GIS Cut Line= 2
2350122.03308432682895.1815435612350450.79056274682422.695921305
#Sta/Elev= 30
       0 2767.98    41.4 2754.64    66.8 2741.99    77.7 2739.59   104.8    2724
   119.4 2712.73   138.9 2702.14   149.5 2702.24   158.4 2699.75   171.8 2698.57
   182.7 2699.54   192.5 2701.87   207.1 2702.78   226.6 2700.45   247.2 2700.66
   260.7 2702.02   289.9 2701.17   304.7 2701.97   328.9 2698.15   342.1 2699.39
   350.7 2698.43   367.9 2697.81   383.9 2698.26   406.9 2704.19     441 2735.53
   454.1 2745.09     501 2771.19   523.9 2782.74     550 2793.92   575.6 2807.32
#Mann= 4 ,-1,0
       0      .1       0   350.7    .045       0   383.9      .1       0
     490     .06       0
Bank Sta=350.7,383.9
XS Rating Curve= 0 ,0
Exp/Cntr(USF)=0,0
Exp/Cntr=0.3,0.1

Type RM Length L Ch R = 1 ,104178  ,247.6,258.2,262.9
XS GIS Cut Line= 3
2350134.00463445682969.5641341372350411.38374566682786.627909659
2350645.48147571682671.200190758
#Sta/Elev= 30
       0 2780.05     7.4 2779.37    22.5 2775.08    31.3  2774.1    45.7 2769.28
    71.1 2763.17    88.5 2757.17     100 2751.68   109.7 2749.92   124.2 2742.91
   141.6 2731.72   155.9 2725.66   182.3 2710.44   201.1 2703.99   250.2  2698.4
   261.3 2699.68   285.3 2698.19   337.6 2701.14   346.5 2700.59   353.6 2698.39
   371.7 2697.09     409 2697.46   422.4    2699   431.3  2697.6   441.5  2699.7
   475.9 2723.18   507.4 2750.89   519.1 2759.66   556.1 2782.17   593.3    2801
#Mann= 5 ,-1,0
       0      .1       0   353.6    .045       0     409      .1       0
  482.27     .06       0  592.27      .1       0
Bank Sta=353.6,409
XS Rating Curve= 0 ,0
Exp/Cntr=0.3,0.1

Type RM Length L Ch R = 1 ,103920  ,236.3,246.7,255.5
XS GIS Cut Line= 2
2350215.62970026 683071.632409112350724.12996086682969.040251271
#Sta/Elev= 30
       0 2761.01    37.3 2752.75    70.5 2743.33    82.2 2738.13    98.5 2732.77
   118.9 2719.69   127.1 2718.96   138.4 2711.78   147.5 2707.53   163.8 2703.32
   245.4 2704.46   249.5 2703.65   257.6 2697.96   261.7 2697.28     278 2698.16
   286.2 2696.48   302.5 2695.59   352.3 2696.23   363.7 2696.76   371.9 2699.46
   380.1 2705.76   420.9 2744.06   437.1 2756.44   452.5 2764.91   469.8 2773.04
   482.1  2780.2   494.3  2785.6   506.6 2792.46   514.7 2795.22   518.7  2797.8
#Mann= 3 ,-1,0
       0      .1       0   286.2    .045       0   352.3      .1       0
Bank Sta=286.2,352.3
XS Rating Curve= 0 ,0
Exp/Cntr(USF)=0,0
Exp/Cntr=0.3,0.1

Type RM Length L Ch R = 1 ,103673  ,241.3,261.5,267.2
XS GIS Cut Line= 3
 2350169.2893967683240.9703218242350454.57255646      683245.781
2350748.09951936683269.925092743
#Sta/Elev= 30
       0 2758.88    34.9 2748.11    54.9 2743.28    86.9 2736.15   138.9 2727.19
   162.9 2719.77   174.9 2713.22   194.9 2706.38   203.7 2701.89   218.9 2700.75
   266.9 2704.12   290.9  2701.4   308.5 2697.61   331.1 2695.49   364.1 2696.81
   379.2 2698.01   403.3 2698.55   407.3 2698.98   411.4  2700.5   415.4  2703.1
   427.7  2713.2   439.4 2724.56   467.5  2747.6   475.6 2752.98   491.6 2765.16
   535.8 2794.72   543.8 2800.83   551.8 2805.61   564.4 2814.82   579.8  2824.5
#Mann= 5 ,-1,0
       0      .1       0   308.5    .045       0   364.1      .1       0
  475.32     .06       0  575.32      .1       0
Bank Sta=308.5,364.1
XS Rating Curve= 0 ,0
Exp/Cntr=0.3,0.1

Type RM Length L Ch R = 1 ,103412  ,221.4,229.4,235.7
XS GIS Cut Line= 2
2350147.23492837683345.2114966822350603.69568861683580.132669706
#Sta/Elev= 30
       0  2752.6      37 2739.68     100 2722.89   122.3 2716.05     136 2710.23
     145 2708.59   158.5 2704.64   167.5 2700.79   174.8  2700.8   181.8 2702.03
   194.5 2699.78   212.5 2698.74   230.5 2700.86   250.2  2701.5     265 2698.99
   276.9  2694.4     280 2694.09   356.5 2694.19     366 2696.06   371.9 2700.06
   375.8 2703.84   383.4 2715.05   387.9 2720.64   401.6 2734.75   413.5  2744.9
   428.2 2756.05   446.2 2766.45   464.4 2779.62   486.9 2793.32   513.4 2810.73
#Mann= 4 ,-1,0
       0      .1       0   276.9    .045       0   356.5      .1       0
     450     .06       0
Bank Sta=276.9,356.5
XS Rating Curve= 0 ,0
Exp/Cntr(USF)=0,0
Exp/Cntr=0.3,0.1

Type RM Length L Ch R = 1 ,103182  ,262.1,265.5,268.8
XS GIS Cut Line= 3
2350040.04595779683501.9621876952350212.38771375 683611.22114242
2350434.51785324683781.675908881
#Sta/Elev= 30
       0 2751.41    13.5 2747.39    33.3 2737.84      57 2728.92    71.2 2725.73
     101 2714.35   121.3 2707.98   135.8  2700.9   142.2 2700.19   153.1 2701.16
   164.7 2698.71   180.1 2698.13   192.8 2700.36     211 2700.92   246.7 2698.36
   264.3 2694.66   270.9 2694.48   336.5 2693.58   339.9 2693.64   345.3 2694.81
   350.8 2697.46   365.1 2712.15   379.3 2724.54   390.3 2732.46   400.4 2742.08
     411 2747.36   422.1 2755.35   463.5 2778.92   476.1 2784.96   484.1 2790.49
#Mann= 4 ,-1,0
       0      .1       0   270.9    .045       0   339.9      .1       0
  474.06     .06       0
Bank Sta=270.9,339.9
XS Rating Curve= 0 ,0
Exp/Cntr=0.3,0.1