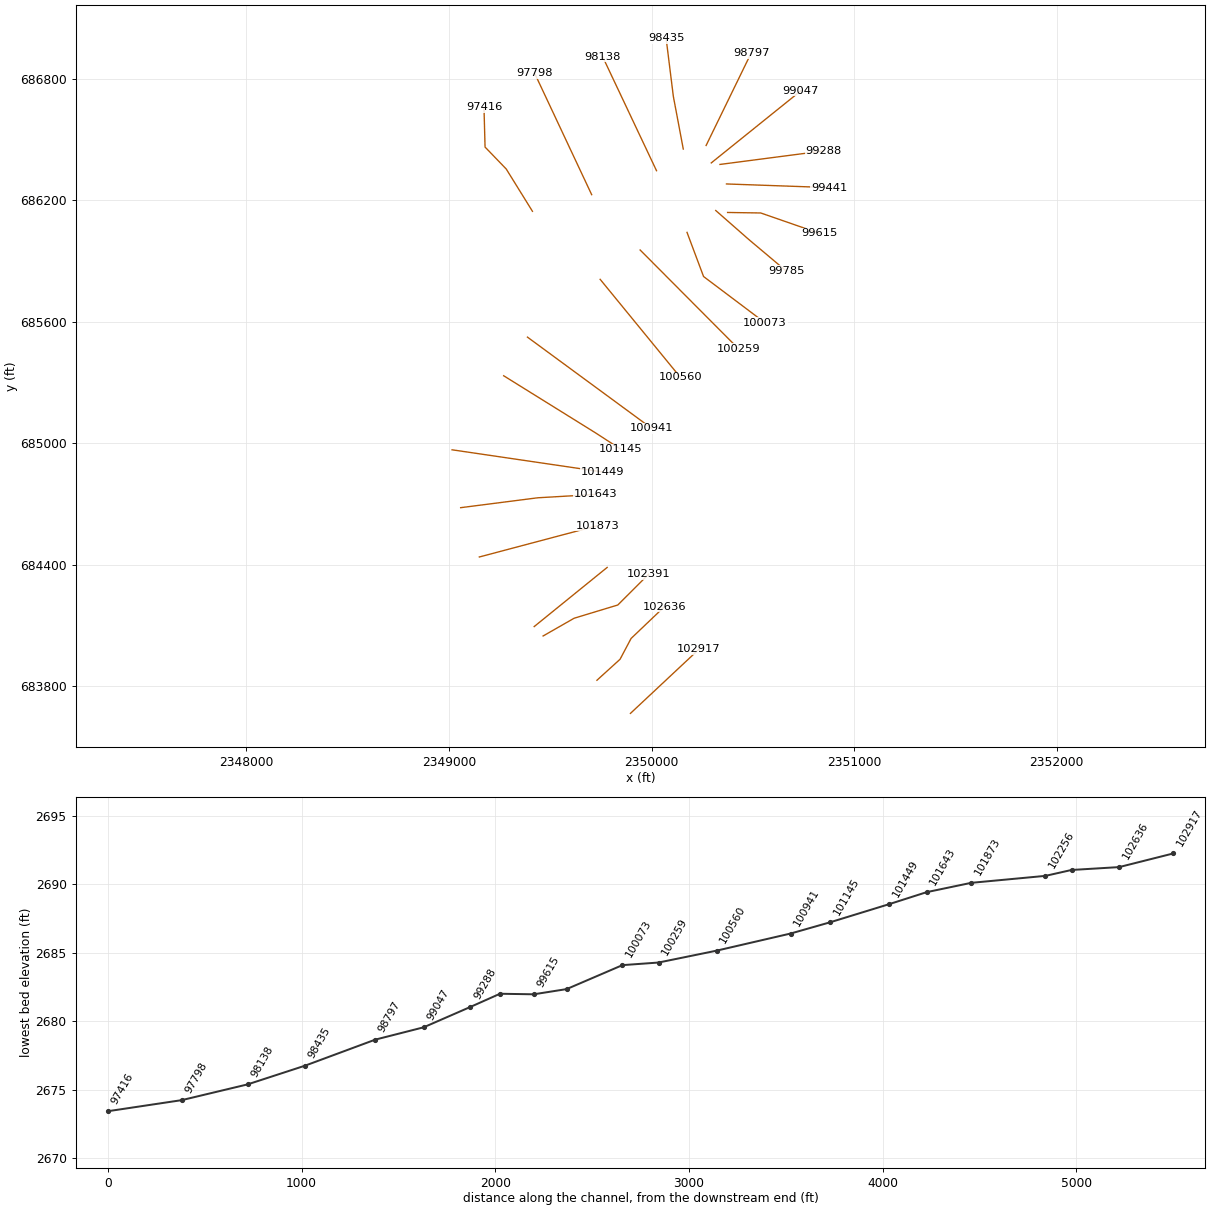
HEC-RAS study GLADYFK.prj: GLADYFK

--- GLADYFK.g01 (geometry) --- (continued)

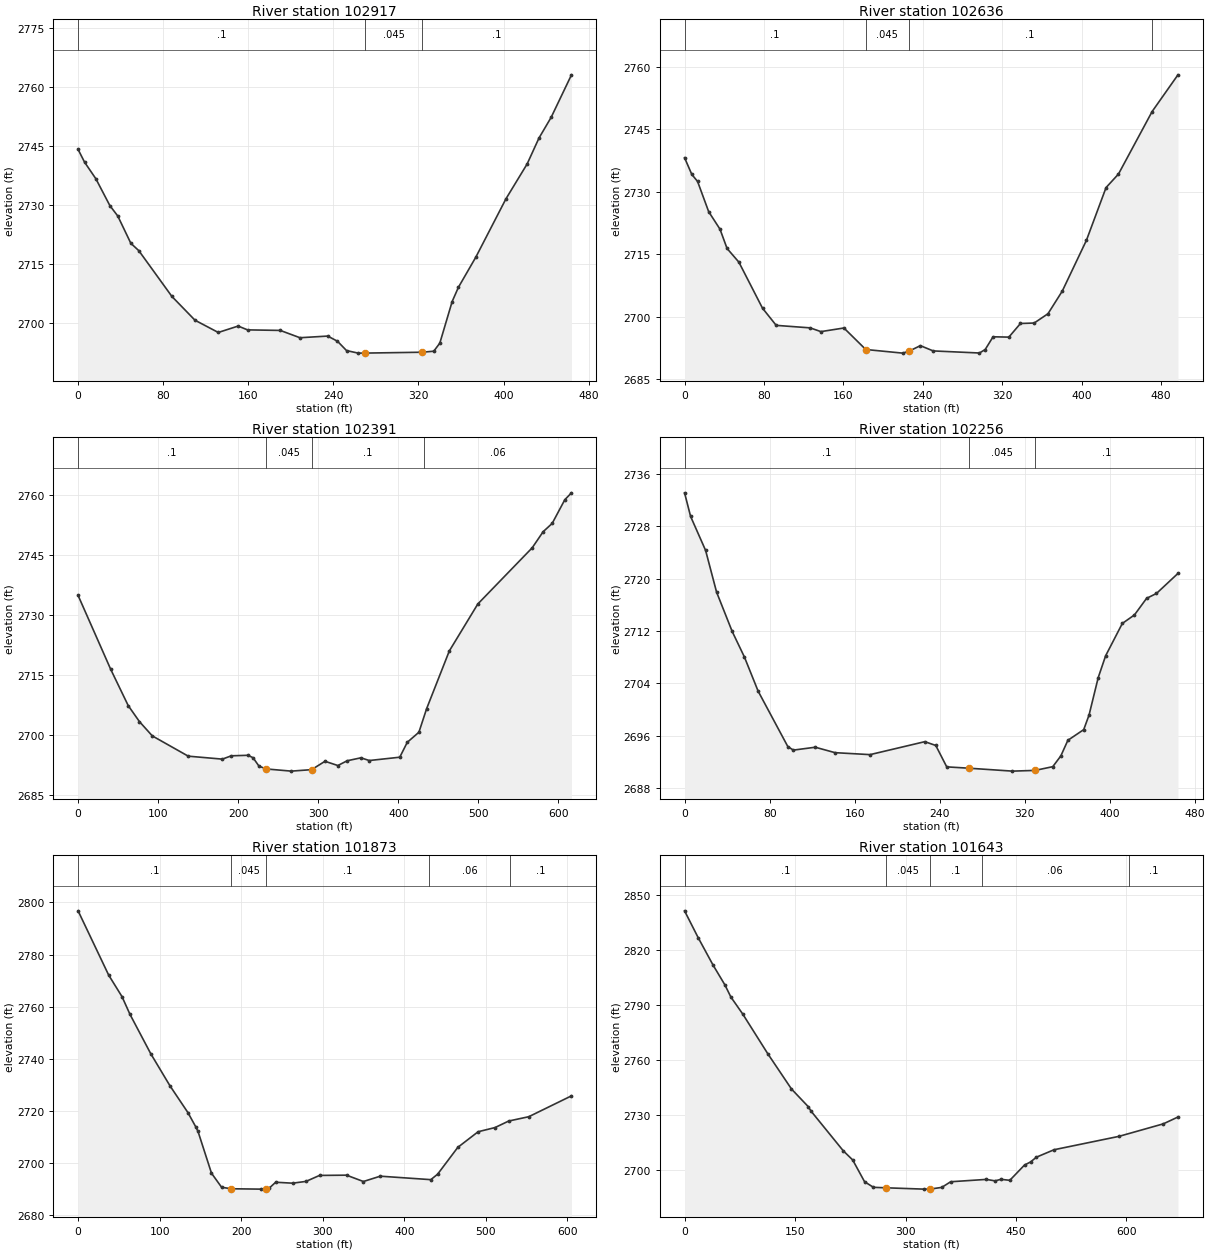
Type RM Length L Ch R = 1 ,102917  ,272,280.4,290.9
XS GIS Cut Line= 2
2349895.95268378683664.7088179822350234.50680465683981.852401564
#Sta/Elev= 30
       0 2744.11     6.1 2740.85    16.7 2736.64    29.9 2729.79    37.3 2727.16
    49.6 2720.21    57.1 2718.33    88.2 2706.68   109.9 2700.63   131.8 2697.51
   150.5 2699.14   159.3 2698.17   190.1 2698.03   208.6 2696.17   234.7 2696.59
   243.9 2695.27   252.4  2692.9   263.4 2692.25   269.8 2692.26   323.7 2692.48
   334.4 2692.74   340.1 2694.79   351.7 2705.38   357.6 2709.01     374  2716.7
   402.3 2731.54   422.2  2740.4   433.3 2746.98   444.8 2752.28   463.9 2763.09
#Mann= 3 ,-1,0
       0      .1       0   269.8    .045       0   323.7      .1       0
Bank Sta=269.8,323.7
XS Rating Curve= 0 ,0
Exp/Cntr(USF)=0,0
Exp/Cntr=0.3,0.1

Type RM Length L Ch R = 1 ,102636  ,273.4,245.7,235
XS GIS Cut Line= 4
2349730.59146632683828.3921146382349844.60890427683932.018523462
2349899.10032461684034.8980684212350062.91523768684191.176189344
#Sta/Elev= 30
       0 2738.13     7.3 2734.12    13.1 2732.44    24.3 2725.18    35.7 2720.98
    42.8 2716.36    54.7 2713.08    78.5 2702.03    92.3 2697.91   126.5 2697.31
   137.3 2696.41   160.5 2697.28   182.5 2692.12   219.7 2691.25   225.6 2691.67
   237.5 2693.04   250.4 2691.78     297 2691.28   302.8 2692.12   310.7 2695.17
   326.6 2695.09   338.3 2698.36   352.1 2698.47     366  2700.7   380.4 2706.13
   404.7  2718.3   424.5 2730.97     437 2734.21   470.9 2749.21   496.9 2758.01
#Mann= 4 ,-1,0
       0      .1       0   182.5    .045       0   225.6      .1       0
  470.49     .06       0
Bank Sta=182.5,225.6
XS Rating Curve= 0 ,0
Exp/Cntr=0.3,0.1

Type RM Length L Ch R = 1 ,102391  ,119.6,134.5,143.8
XS GIS Cut Line= 4
2349464.80950975684047.0945410762349617.95432508684134.818270243
2349833.54654083684200.2393564012349985.20451329 684351.89732886
#Sta/Elev= 30
       0 2734.97    40.8 2716.47    62.6 2707.43    76.6 2703.43    92.7 2699.85
   137.6 2694.78   180.2 2694.04   191.4 2694.87   212.3    2695   218.6 2694.38
   225.9  2692.3   234.7 2691.59   266.3 2691.04   291.7 2691.41   308.4  2693.5
   324.5 2692.44   336.1 2693.63   353.3 2694.37   363.7 2693.69   401.8 2694.52
   411.2 2698.25   425.7 2700.76   435.4 2706.68   463.7 2721.09   499.3 2732.83
   567.2 2746.87   580.9  2750.9   592.2 2752.98     608 2758.91   616.3 2760.62
#Mann= 4 ,-1,0
       0      .1       0   234.7    .045       0   291.7      .1       0
  431.79     .06       0
Bank Sta=234.7,291.7
XS Rating Curve= 0 ,0
Exp/Cntr(USF)=0,0
Exp/Cntr=0.3,0.1

Type RM Length L Ch R = 1 ,102256  ,389.3,383.6,378.5
XS GIS Cut Line= 2
2349420.77360666 684093.59057731 2349780.9787414684385.856335644
#Sta/Elev= 30
       0 2733.12     5.7 2729.51    19.8 2724.32    30.1 2717.96    44.8 2711.94
    56.2 2708.07    69.2 2702.82    97.1 2694.36   102.3 2693.82   122.9 2694.26
   141.5 2693.43   174.4 2693.13   225.9 2695.11   236.2 2694.53   246.5 2691.26
   267.1 2691.06   308.3 2690.61   329.5 2690.72   346.2 2691.29   353.8 2692.94
   360.4 2695.32   375.3 2696.95   380.3 2699.17   388.9 2704.88   395.9 2708.23
   411.6 2713.17     423 2714.47   434.4    2717   443.7 2717.75   463.9 2720.81
#Mann= 3 ,-1,0
       0      .1       0   267.1    .045       0   329.5      .1       0
Bank Sta=267.1,329.5
XS Rating Curve= 0 ,0
Exp/Cntr=0.3,0.1

Type RM Length L Ch R = 1 ,101873  ,231,229.6,228.5
XS GIS Cut Line= 2
2349150.02939673684437.4396299762349734.85425784684592.732107221
#Sta/Elev= 30
       0 2796.74    37.5 2772.12    53.9 2763.84    63.7 2757.03    89.1    2742
   112.7 2729.68   134.7 2719.43   144.3 2713.97   147.1 2712.19   163.6 2696.21
     176 2690.81   187.9 2690.24   223.9  2690.1   230.5 2690.12     234 2690.36
   242.3 2692.74     263 2692.38   279.5 2693.06   296.1 2695.35   329.2 2695.45
   349.9 2693.02   370.6 2695.06   432.6 2693.73   440.9 2695.82   465.7 2706.11
   490.6 2712.09   511.3 2713.69   528.1 2716.19   552.7 2717.85   605.1 2725.85
#Mann= 5 ,-1,0
       0      .1       0   187.9    .045       0   230.5      .1       0
     430     .06       0     530      .1       0
Bank Sta=187.9,230.5
XS Rating Curve= 0 ,0
Exp/Cntr(USF)=0,0
Exp/Cntr=0.3,0.1

Type RM Length L Ch R = 1 ,101643  ,203.2,194.4,186.9
XS GIS Cut Line= 3
2349057.78438203684681.0642236982349437.94380287684729.924671094
2349724.07573646684746.480210416
#Sta/Elev= 30
       0 2841.16    18.5 2826.52    38.7 2811.58    54.8 2800.76    62.9 2794.16
      79 2784.89     113 2763.25   145.2    2744   167.8 2734.45   171.8 2731.92
   215.5 2710.31   228.3 2705.32   244.4 2693.46   256.5  2690.4   273.8 2690.14
     325 2689.42   333.1 2689.44   349.2 2690.36   361.3 2693.44   409.6 2694.72
   421.6 2693.93   429.6 2694.76   441.6 2694.22   461.6 2702.57   469.7 2704.21
   477.7 2706.84   501.7  2710.9   589.9  2718.2     650 2725.01   669.9 2728.74
#Mann= 5 ,-1,0
       0      .1       0   273.8    .045       0   333.1      .1       0
  403.29     .06       0  603.29      .1       0
Bank Sta=273.8,333.1
XS Rating Curve= 0 ,0
Exp/Cntr=0.3,0.1

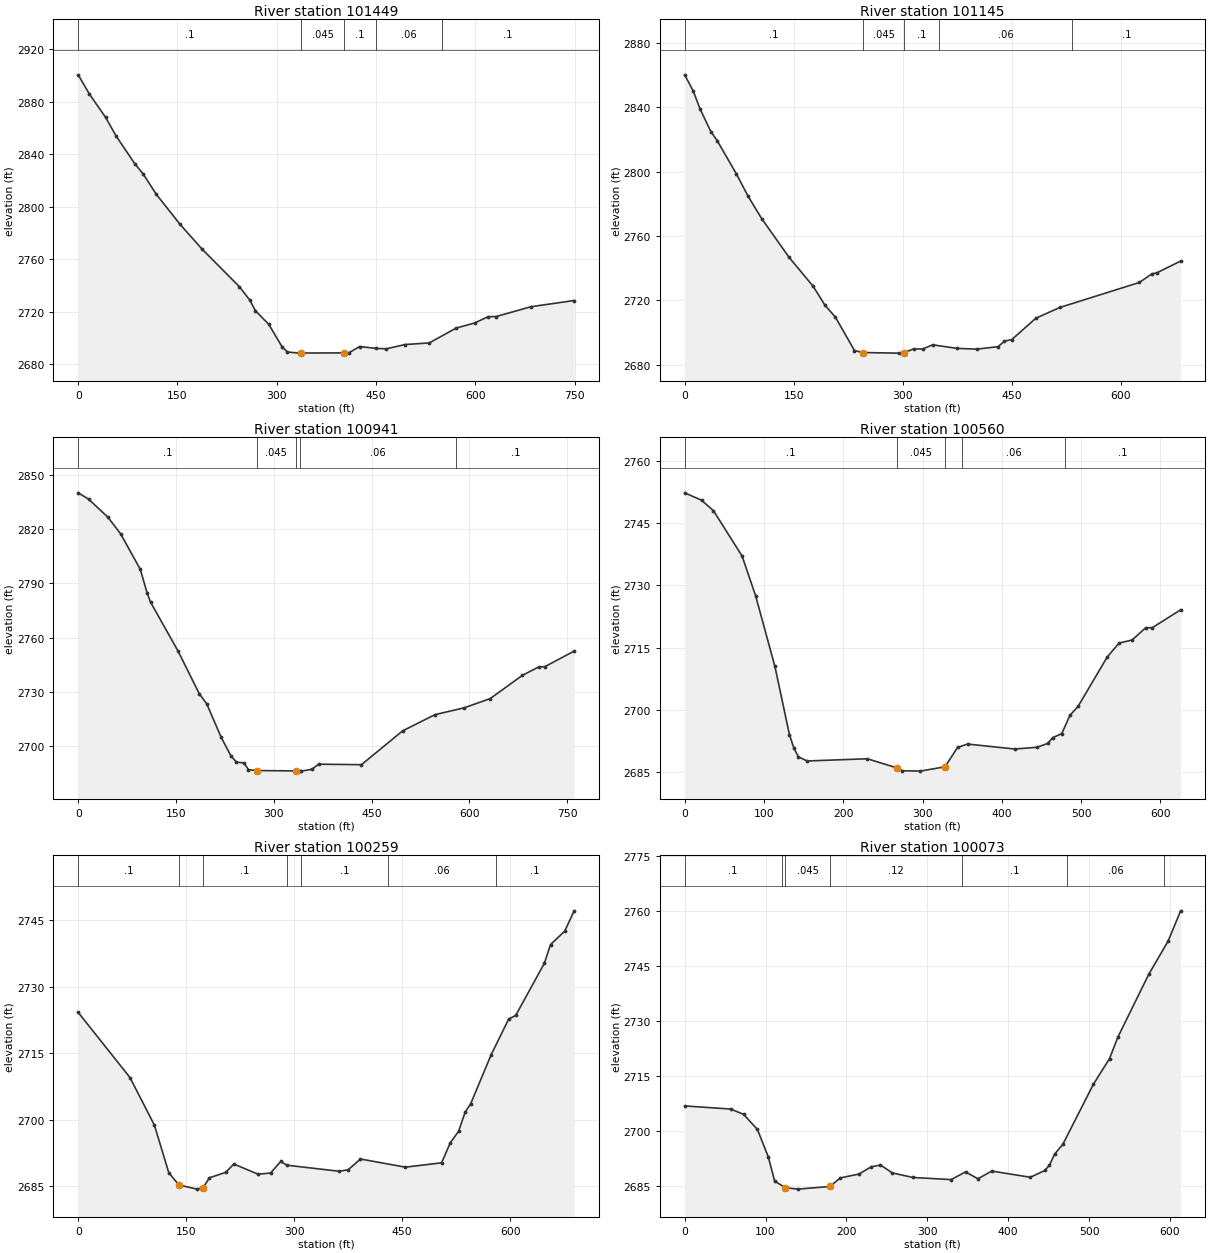
Type RM Length L Ch R = 1 ,101449  ,315,303.7,289.5
XS GIS Cut Line= 2
2349015.35485595684967.0525361192349756.76050553684857.940006558
#Sta/Elev= 30
       0 2900.66      17 2885.95    41.3  2868.3    57.4 2853.92    85.7 2832.75
    97.9 2825.31   118.1 2809.51   153.9 2786.71   186.8 2768.01   243.4 2739.27
   259.7 2728.71   267.7 2720.87   287.9 2710.52   308.1 2693.33   316.2 2689.38
   333.7 2688.54   337.2 2688.61   401.1 2688.73   409.2 2688.84   425.3 2693.56
     450 2692.17   465.8 2691.84   494.1  2695.1   530.5 2696.31   570.9  2707.6
   599.2 2711.55   619.4 2716.32   631.6 2716.43   684.1  2723.9   749.4 2728.65
#Mann= 5 ,-1,0
       0      .1       0   337.2    .045       0   401.1      .1       0
     450     .06       0     550      .1       0
Bank Sta=337.2,401.1
XS Rating Curve= 0 ,0
Exp/Cntr(USF)=0,0
Exp/Cntr=0.3,0.1

Type RM Length L Ch R = 1 ,101145  ,205,203.6,200.8
XS GIS Cut Line= 3
2349270.22288708685332.8540134492349722.74505912685051.245655925
2349847.74791398684970.217629028
#Sta/Elev= 30
       0 2860.04    11.7 2850.06    21.1 2838.93      36 2824.79    44.7 2819.18
    70.9 2798.69    87.1 2784.72   105.9 2770.75   143.6 2746.68   176.6 2728.78
   192.8 2717.09   207.4 2709.47   233.5 2688.83   245.1 2687.58   294.4 2687.22
   302.2 2687.58   314.8 2689.84   327.4 2689.79     341 2692.39   374.5 2690.17
   401.9 2689.72     431 2691.22   439.7 2694.66   449.9 2695.66   482.9 2708.89
   515.8 2715.56   625.3  2731.1   642.5 2736.43   649.1 2737.05     682 2744.39
#Mann= 5 ,-1,0
       0      .1       0   245.1    .045       0   302.2      .1       0
     350     .06       0  532.99      .1       0
Bank Sta=245.1,302.2
XS Rating Curve= 0 ,0
Exp/Cntr=0.3,0.1

Type RM Length L Ch R = 1 ,100941  ,391.1,381.6,376.6
XS GIS Cut Line= 2
2349387.45655933685523.8062125942350000.16537917685073.367308511
#Sta/Elev= 30
       0 2840.04    15.8 2836.58    45.6 2826.58    65.2 2817.31    95.2 2797.81
   105.7 2784.73   111.1 2779.57     153 2752.76   185.5 2729.23     197 2723.61
   219.3 2705.02   234.2 2694.82   242.7 2691.34   254.1 2690.95   261.1 2687.22
   274.2 2686.72   333.5 2686.52     340 2686.44   342.1  2686.4   358.3 2687.42
   368.6 2690.23   434.4 2689.96   497.4 2708.62     547 2717.57     592 2721.36
   631.9 2726.47     681 2739.26   705.9 2743.85   715.8 2744.11   760.5 2752.67
#Mann= 5 ,-1,0
       0      .1       0   274.2    .045       0   333.5      .1       0
     340     .06       0     580      .1       0
Bank Sta=274.2,333.5
XS Rating Curve= 0 ,0
Exp/Cntr(USF)=0,0
Exp/Cntr=0.3,0.1

Type RM Length L Ch R = 1 ,100560  ,289.8,300.6,304.8
XS GIS Cut Line= 2
2349746.38996668685809.3038670762350142.26186042685325.122471363
#Sta/Elev= 30
       0 2752.38    21.3 2750.59    36.3 2748.06    72.4 2737.11    89.5 2727.48
   113.8 2710.43   132.1 2693.99   137.8 2690.66   143.5 2688.59   154.5  2687.6
   230.3 2688.14   268.2  2685.9   274.6 2685.24     297 2685.15   328.3  2686.2
   344.1 2690.87   356.7 2691.69   416.4 2690.49   444.5 2690.92   457.8 2691.84
   464.1 2693.24   475.5 2694.21   485.8 2698.62     496 2700.77   532.9 2712.73
   547.8 2716.09   564.2 2716.82   581.3 2719.78   589.8 2719.81   625.4 2724.12
#Mann= 5 ,-1,0
       0      .1       0   268.2    .045       0   328.3      .1       0
     350     .06       0     480      .1       0
Bank Sta=268.2,328.3
XS Rating Curve= 0 ,0
Exp/Cntr(USF)=0,0
Exp/Cntr=0.3,0.1

Type RM Length L Ch R = 1 ,100259  ,191,186.4,178
XS GIS Cut Line= 2
2349943.66883174685954.3854774672350429.42039647 685465.95759558
#Sta/Elev= 30
       0 2724.18    71.9 2709.48   105.9  2698.7   125.8    2688   139.8 2685.22
   165.2 2684.28   173.7 2684.64   182.2 2686.84   204.8 2688.06   216.2 2689.94
   249.9 2687.65   267.3 2687.92   281.2 2690.52     290 2689.68   362.7 2688.31
   375.1 2688.67   392.1 2691.08   454.5 2689.24   504.7 2690.22   516.9 2694.75
   528.3 2697.33   537.6  2701.7   545.3 2703.61   573.6 2714.62     598  2722.7
   607.7  2723.5   647.4 2735.24   656.1  2739.5   675.7 2742.52   688.9 2747.12
#Mann= 7 ,-1,0
       0      .1       0   139.8    .045       0   173.7      .1       0
     290     .12       0     310      .1       0     430     .06       0
     580      .1       0
Bank Sta=139.8,173.7
XS Rating Curve= 0 ,0
Exp/Cntr(USF)=0,0
Exp/Cntr=0.3,0.1

Type RM Length L Ch R = 1 ,100073  ,270.3,287.9,295
XS GIS Cut Line= 3
2350175.17026617  686041.36578522350256.79793958685823.245936576
2350560.55993736685594.420819309
#Sta/Elev= 30
       0 2706.79    56.9 2705.94    72.8  2704.5    89.9 2700.39   103.5 2692.82
   111.2 2686.31   124.1  2684.5   139.8 2684.09   179.6 2684.81   192.4 2687.15
   215.4  2688.2   230.8 2690.19   242.1 2690.67   256.8 2688.51   282.2 2687.27
   329.4 2686.69   347.3 2688.79   362.6 2686.91   379.6 2689.02   427.4 2687.33
   445.3 2689.18     451 2690.62   457.5 2693.67   467.5 2696.29   505.3 2712.68
   525.3  2719.7   535.5 2725.51   573.8  2742.7   597.7 2751.74   613.2 2760.02
#Mann= 7 ,-1,0
       0      .1       0     120     .12       0   124.1    .045       0
   179.6     .12       0  342.89      .1       0  472.89     .06       0
  592.89      .1       0
Bank Sta=124.1,179.6
XS Rating Curve= 0 ,0
Exp/Cntr(USF)=0,0
Exp/Cntr=0.3,0.1

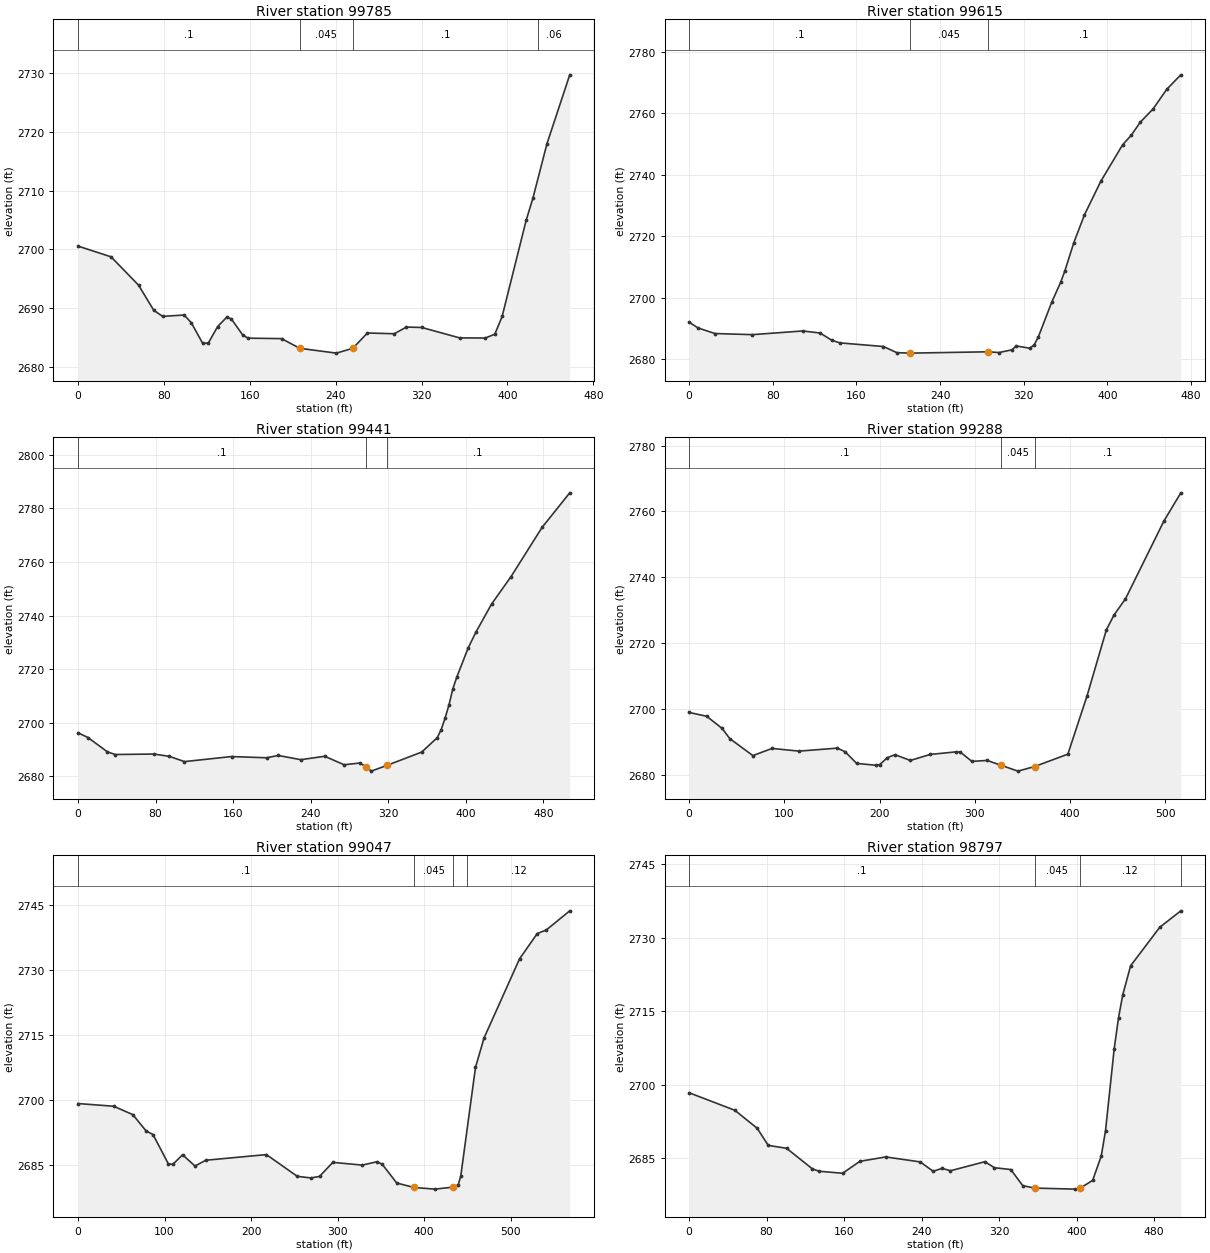
Type RM Length L Ch R = 1 ,99785   ,156.4,169.8,186.5
XS GIS Cut Line= 3
2350316.89095934686149.5037910582350481.23436214686005.205742723
2350664.39971803685851.069187425
#Sta/Elev= 30
       0 2700.57    30.8 2698.74    56.4 2693.92    70.6 2689.63    78.9  2688.6
    98.9 2688.83   105.5 2687.53   116.2 2683.99   121.5 2684.09   130.1 2686.87
   138.6 2688.47   142.8 2688.18   153.4 2685.44   158.4 2684.89   189.6 2684.81
   206.6 2683.16   240.7 2682.34     256 2683.16   269.6 2685.77   294.6 2685.64
     306 2686.78   320.2 2686.71   355.4 2684.94   379.4 2684.91   388.3 2685.56
   395.1 2688.58   417.5 2704.96   423.8 2708.74   436.9 2718.02   458.1 2729.74
#Mann= 4 ,-1,0
       0      .1       0   206.6    .045       0     256      .1       0
   428.7     .06       0
Bank Sta=206.6,256
XS Rating Curve= 0 ,0
Exp/Cntr(USF)=0,0
Exp/Cntr=0.3,0.1

Type RM Length L Ch R = 1 ,99615   ,173.3,174.2,178.8
XS GIS Cut Line= 3
2350375.54660202686139.7199209042350539.21539636686137.201939453
2350828.78326327686036.482681397
#Sta/Elev= 30
       0 2692.03     8.6 2690.15    24.6 2688.34    60.6 2687.97   108.6 2689.17
   125.3  2688.5   136.6 2686.12   144.3 2685.29   185.9 2684.11   198.6 2682.12
   211.3 2681.96   285.5 2682.39   296.4 2682.15   308.7 2683.03   312.9 2684.29
   325.6 2683.57   329.9 2684.54   334.1  2687.3   346.8  2698.5   355.3 2704.96
   359.3 2708.61     368 2717.93   378.1 2726.93   393.8 2737.88   414.6 2749.71
     423 2752.88   431.5 2757.07   443.8 2761.41   456.9 2767.81   470.3 2772.49
#Mann= 3 ,-1,0
       0      .1       0   211.3    .045       0   285.5      .1       0
Bank Sta=211.3,285.5
XS Rating Curve= 0 ,0
Exp/Cntr(USF)=0,0
Exp/Cntr=0.3,0.1

Type RM Length L Ch R = 1 ,99441   ,149.6,152.3,155
XS GIS Cut Line= 2
2350369.93103743686280.6012688552350876.75371122686262.643836603
#Sta/Elev= 30
       0 2696.31    10.3 2694.53    30.3  2689.2    38.3  2688.2    78.3 2688.37
    94.2 2687.51   109.8 2685.55   158.3 2687.44   194.4 2686.98   206.5 2687.84
   229.7 2686.27   254.4 2687.54   274.4 2684.38   290.4 2685.01   297.5 2683.58
   302.4    2682   318.3  2684.1   354.5 2689.12   370.5  2694.5   374.5 2697.47
   378.5 2701.71   382.5 2706.62   386.5 2712.62   390.5 2716.96   402.5 2728.08
   410.5 2733.95   426.5 2744.34   446.5 2754.53   478.5 2772.89   507.1 2785.82
#Mann= 3 ,-1,0
       0      .1       0   297.5    .045       0   318.3      .1       0
Bank Sta=297.5,318.3
XS Rating Curve= 0 ,0
Exp/Cntr(USF)=0,0
Exp/Cntr=0.3,0.1

Type RM Length L Ch R = 1 ,99288   ,225.4,241.5,249.1
XS GIS Cut Line= 2
2350337.78445127686377.0379960852350849.74234786 686443.81363886
#Sta/Elev= 30
       0 2698.88    18.5 2697.71    34.7 2694.02    42.7 2690.93      67 2685.76
    87.1 2687.94   115.4 2687.12   155.7 2688.03   163.8 2686.94   175.9 2683.39
     196 2682.83   200.1    2683   208.1 2685.13   216.2 2686.04   232.3 2684.28
   253.1 2686.11   280.7 2686.91   284.8 2686.83   296.9    2684     313 2684.29
   327.3 2682.84   345.3 2681.04   362.7 2682.43   397.7  2686.2   417.9 2703.97
   438.1 2723.96   446.1 2728.48   458.2 2733.42   498.6  2757.1   516.3 2765.63
#Mann= 3 ,-1,0
       0      .1       0   327.3    .045       0   362.7      .1       0
Bank Sta=327.3,362.7
XS Rating Curve= 0 ,0
Exp/Cntr(USF)=0,0
Exp/Cntr=0.3,0.1

Type RM Length L Ch R = 1 ,99047   ,238,249.8,258.1
XS GIS Cut Line= 2
2350294.85748803686384.6146724362350737.35227374686741.068805374
#Sta/Elev= 30
       0 2699.28    41.2 2698.66    63.3 2696.73    78.7 2692.97    86.7 2692.14
   104.4 2685.37   109.6 2685.26   120.8 2687.47   135.2 2684.88   147.6 2686.21
   217.7 2687.51   253.4  2682.5   269.1 2682.13   279.1 2682.48   294.4 2685.72
   328.5 2685.09   345.8 2685.88   351.6 2685.26   368.3 2680.96   388.2 2679.93
   412.6 2679.55   433.7 2680.02   439.4 2680.57   442.3 2682.58   459.3 2707.62
   469.1 2714.36   510.2 2732.64   530.7 2738.48     541 2739.28   568.2 2743.71
#Mann= 4 ,-1,0
       0      .1       0   388.2    .045       0   433.7      .1       0
     450     .12       0
Bank Sta=388.2,433.7
XS Rating Curve= 0 ,0
Exp/Cntr(USF)=0,0
Exp/Cntr=0.3,0.1

Type RM Length L Ch R = 1 ,98797   ,345.6,362.1,372.1
XS GIS Cut Line= 2
2350269.42350934686470.700380761 2350491.5578337686927.012456716
#Sta/Elev= 30
       0 2698.33    47.2 2694.75    70.3 2691.08    81.7 2687.58   100.6 2686.99
   127.3 2682.78   134.2  2682.3   158.5 2681.89   176.3 2684.33     203 2685.22
   238.5 2684.21   251.9  2682.3   261.2 2682.89   269.7  2682.4   305.3 2684.25
   315.1 2683.02     332 2682.65   344.4 2679.35     357 2678.86   398.7 2678.65
   403.1 2678.78   416.5 2680.44   425.4 2685.42   429.8  2690.6   438.7 2707.24
   443.2 2713.64   447.6 2718.34   455.7 2724.25   485.7  2732.1   507.5 2735.47
#Mann= 4 ,-1,0
       0      .1       0     357    .045       0   403.1     .12       0
  507.51      .1       0
Bank Sta=357,403.1
XS Rating Curve= 0 ,0
Exp/Cntr(USF)=0,0
Exp/Cntr=0.3,0.1

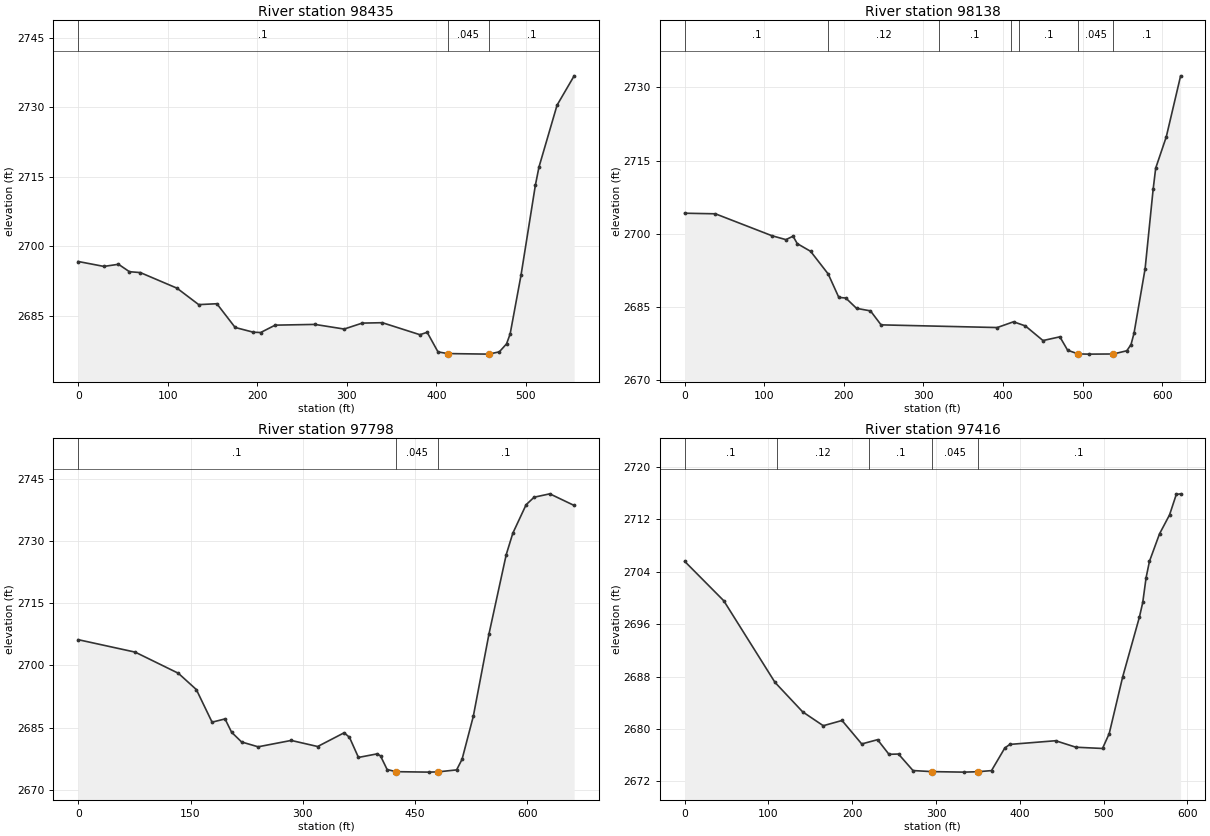
Type RM Length L Ch R = 1 ,98435   ,289.5,297.2,303.8
XS GIS Cut Line= 3
2350156.74272644686452.9456529012350107.67691182686713.143154667
2350071.99268301687000.103828043
#Sta/Elev= 30
       0 2696.73    28.7 2695.67      45 2696.13    57.2 2694.53    69.4 2694.34
   110.3 2690.98   134.6 2687.43   154.9 2687.62   175.3  2682.5   195.6 2681.48
   203.8 2681.41     220    2683   264.4 2683.16   297.1 2682.16   317.2 2683.44
   339.7 2683.53   381.7 2680.94   389.8 2681.46   401.9 2677.23   412.7 2676.87
   458.3 2676.75   458.7 2676.76   470.4 2677.24   478.5 2678.97   482.5  2681.1
   494.6 2693.72   510.7  2713.2   514.7  2717.1   534.9 2730.45     554 2736.78
#Mann= 3 ,-1,0
       0      .1       0   412.7    .045       0   458.7      .1       0
Bank Sta=412.7,458.7
XS Rating Curve= 0 ,0
Exp/Cntr(USF)=0,0
Exp/Cntr=0.3,0.1

Type RM Length L Ch R = 1 ,98138   ,341.5,339.8,340
XS GIS Cut Line= 2
 2350024.5513749686346.1343933192349758.57170642686909.482635238
#Sta/Elev= 30
       0 2704.22    38.6  2704.1   109.5 2699.62   127.2 2698.81   136.1 2699.52
   141.4    2698   158.2 2696.42   180.3 2691.78   193.6    2687   202.4 2686.86
   215.9 2684.75   233.4 2684.23   246.7 2681.37   392.6 2680.82   413.1    2682
     428 2681.15   450.1 2678.16   471.3 2678.92   481.1 2676.17   494.4 2675.42
   507.6 2675.38   538.6 2675.41   555.4 2676.07   560.7 2677.34   564.5 2679.69
   578.4 2692.87   588.5 2709.14   591.7 2713.45     605 2719.86     623 2732.34
#Mann= 7 ,-1,0
       0      .1       0     180     .12       0     320      .1       0
     410     .12       0     420      .1       0   494.4    .045       0
   538.6      .1       0
Bank Sta=494.4,538.6
XS Rating Curve= 0 ,0
Exp/Cntr(USF)=0,0
Exp/Cntr=0.3,0.1

Type RM Length L Ch R = 1 ,97798   ,371.2,381.7,389.2
XS GIS Cut Line= 2
 2349704.5128057686227.6456350182349423.10807675686827.338924802
#Sta/Elev= 30
       0 2706.24    76.1 2703.23   133.7 2698.13   157.8 2694.18   178.8  2686.3
   196.1 2687.09   204.9 2683.86   218.2 2681.52   240.3 2680.35   284.5 2681.89
   319.8 2680.42   355.2 2683.74   362.3 2682.64   374.3 2677.78   399.4 2678.65
   403.8 2678.14   412.6 2674.86   424.5 2674.34   468.7 2674.23     481  2674.3
   505.4 2674.77   512.7 2677.34   527.7 2687.72   548.7 2707.68   571.7 2726.81
   580.5 2731.98   598.2 2738.85   608.9 2740.67   629.9 2741.49   662.4 2738.68
#Mann= 3 ,-1,0
       0      .1       0   424.5    .045       0     481      .1       0
Bank Sta=424.5,481
XS Rating Curve= 0 ,0
Exp/Cntr(USF)=0,0
Exp/Cntr=0.3,0.1

Type RM Length L Ch R = 1 ,97416   ,409.8,386,344.2
XS GIS Cut Line= 4
2349412.18276959686145.5174908692349282.78198891686354.394631471
2349178.24431713686462.9065573392349172.96087797686658.371395438
#Sta/Elev= 30
       0 2705.58    46.7 2699.56   107.8 2687.11   140.8 2682.62   165.4  2680.5
   187.8  2681.3   211.3 2677.72   230.2 2678.37   243.8 2676.14   255.2 2676.18
   272.5 2673.66   294.8  2673.5   332.9 2673.42   349.6 2673.48   366.2 2673.65
   382.1 2677.11   388.1 2677.65   442.7 2678.21   466.9 2677.22   498.7 2677.03
   506.7 2679.31   522.7 2687.93   542.7 2697.06   546.7  2699.3   550.7 2703.09
   554.7 2705.58   566.7 2709.77   578.7 2712.67   586.7 2715.78   591.9 2715.88
#Mann= 5 ,-1,0
       0      .1       0     110     .12       0     220      .1       0
   294.8    .045       0   349.6      .1       0
Bank Sta=294.8,349.6
XS Rating Curve= 0 ,0
Exp/Cntr(USF)=0,0
Exp/Cntr=0.3,0.1