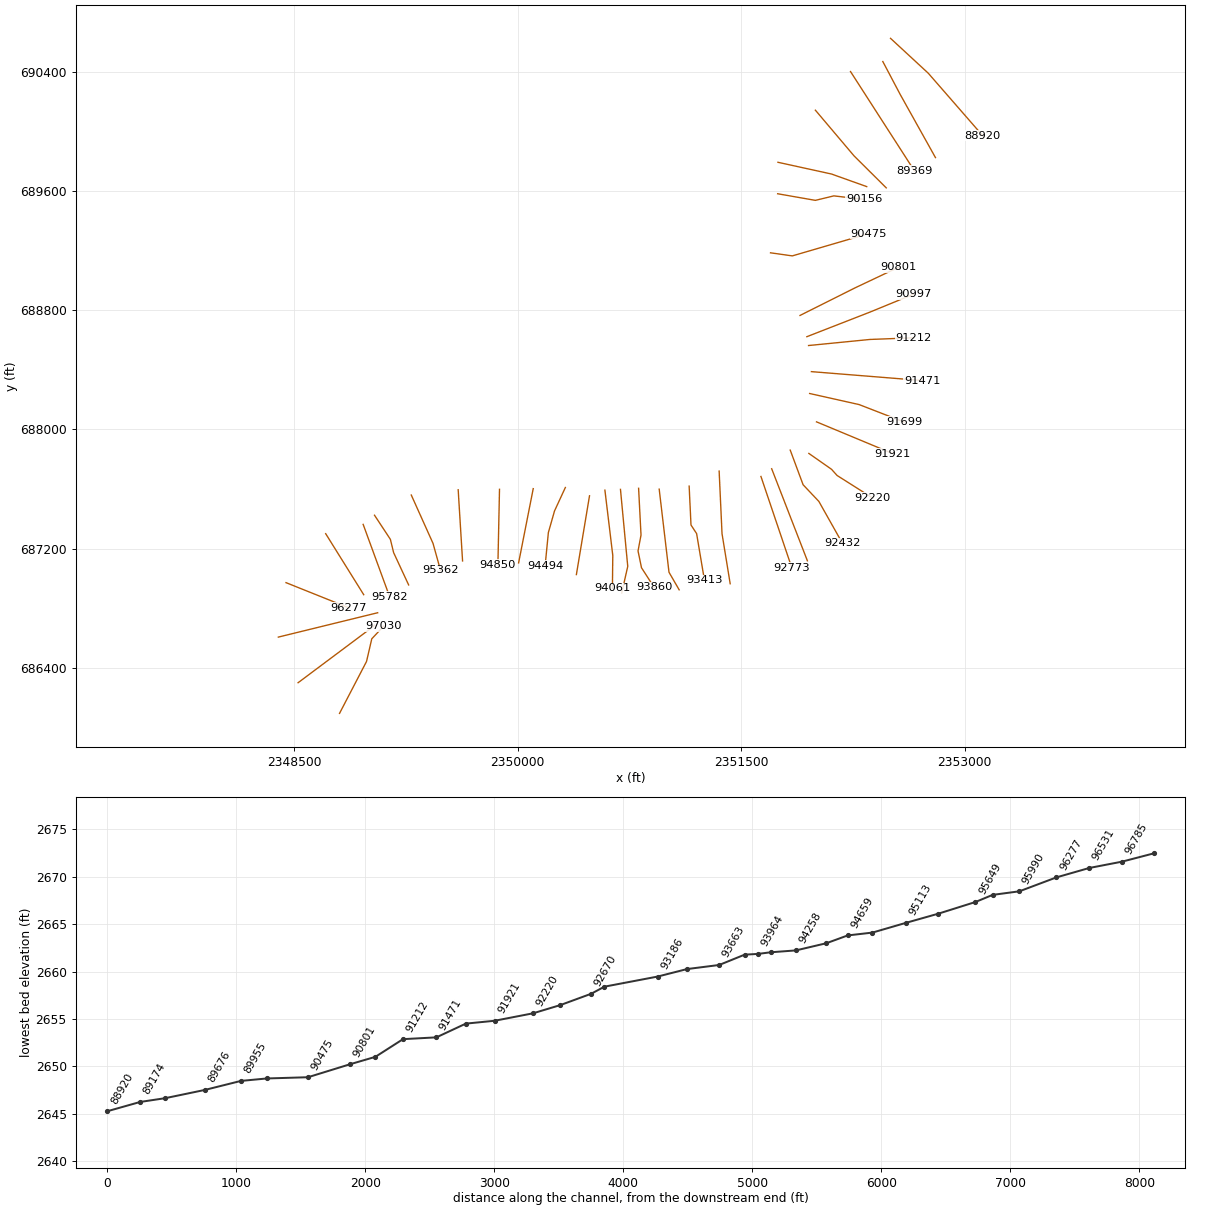
HEC-RAS study GLADYFK.prj: GLADYFK

--- GLADYFK.g01 (geometry) --- (continued)

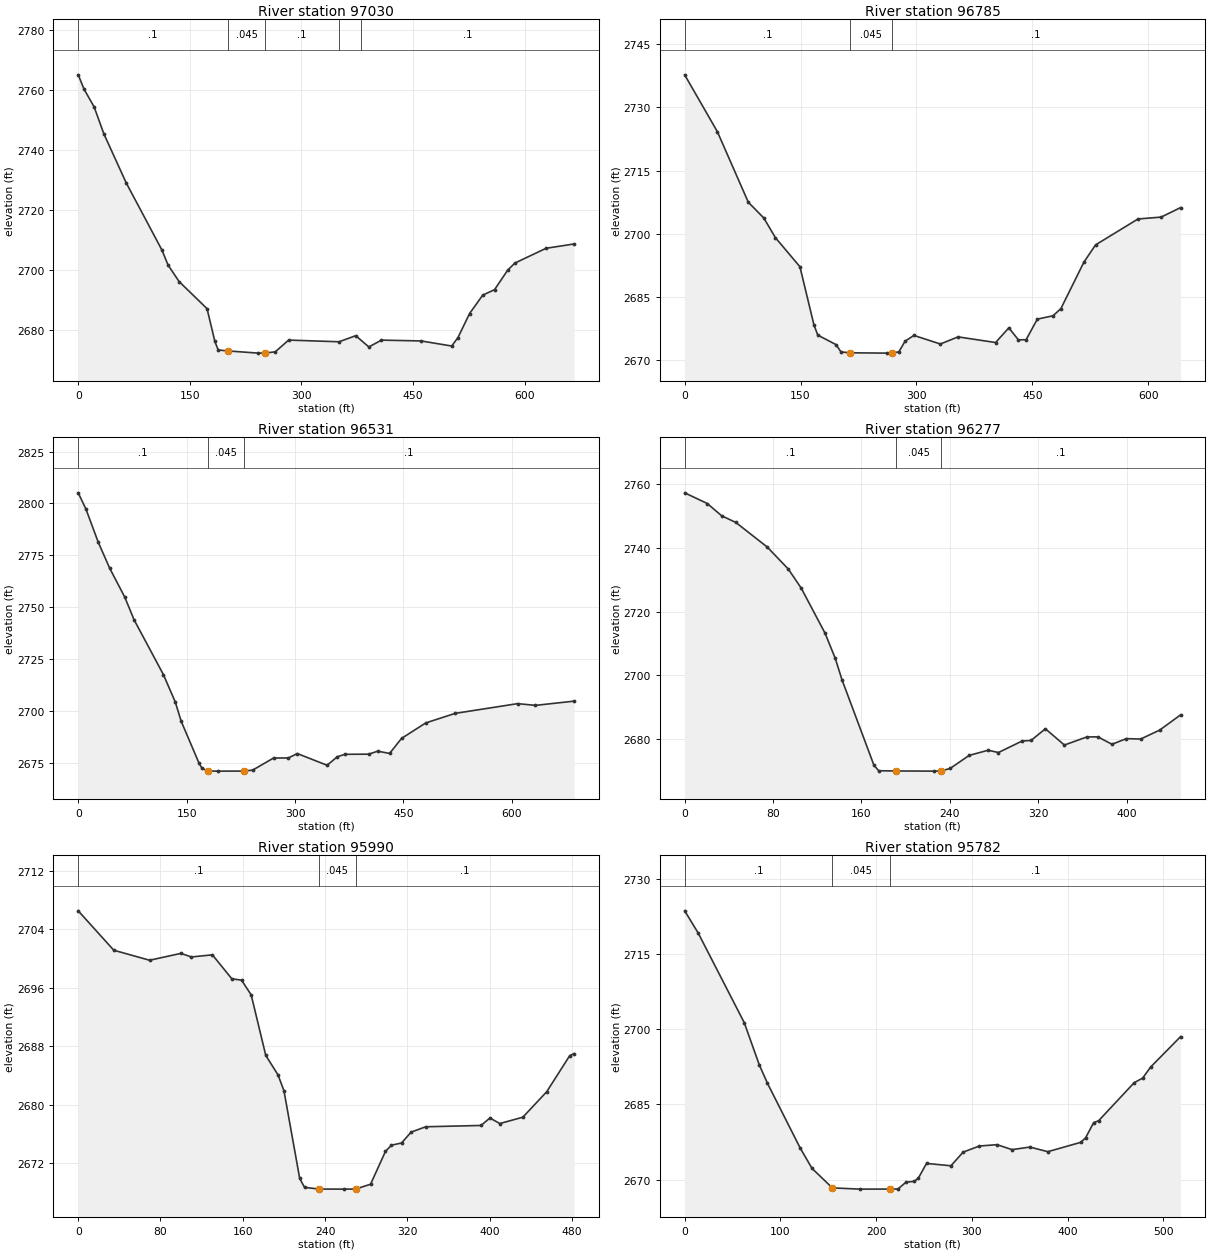
Type RM Length L Ch R = 1 ,97030   ,253.1,245,229.5
XS GIS Cut Line= 4
2348804.24244549686094.2025099272348985.35385132686442.251541979
2349020.68542151686594.618938405  2349101.285566686680.739640732
#Sta/Elev= 30
       0 2765.04     7.9 2760.23    21.4 2754.37    34.5  2745.4    64.4 2729.16
   112.5 2706.78   120.8 2701.76   135.6 2696.28   173.2 2687.26   183.7 2676.35
   188.2 2673.51   200.9 2673.21   242.2 2672.47   251.6  2672.5   264.9 2672.91
   282.9 2676.81   350.6 2676.25   373.1 2678.27   390.7 2674.53   407.7  2676.8
   461.1 2676.52   502.1 2674.83   510.5 2677.64   526.1 2685.63   543.8 2691.76
   559.7 2693.58   577.3 2700.05     587 2702.42     629 2707.35   666.7 2708.78
#Mann= 5 ,-1,0
       0      .1       0   200.9    .045       0   251.6      .1       0
     350     .12       0     380      .1       0
Bank Sta=200.9,251.6
XS Rating Curve= 0 ,0
Exp/Cntr(USF)=0,0
Exp/Cntr=0.3,0.1

Type RM Length L Ch R = 1 ,96785   ,263.1,254.6,242.8
XS GIS Cut Line= 3
2348526.14417425686299.8770596722349030.01870148686676.543919371
2349038.27893963686686.456205153
#Sta/Elev= 30
       0 2737.76    42.3 2724.25    82.4 2707.46   102.4 2703.73   117.4 2699.06
   149.2 2692.13   167.3 2678.34   172.3 2675.88   195.9 2673.63   202.4 2671.88
   213.9 2671.68   262.2  2671.6   268.2 2671.66   277.2 2671.89   285.3 2674.43
   296.7 2675.81     331 2673.77   353.9 2675.46   402.5 2674.12   419.6 2677.61
     432 2674.76     442 2674.79   456.5 2679.68   476.8 2680.48     487 2682.18
   516.9 2693.26   531.9 2697.33   586.8 2703.49   616.8 2703.94     642  2706.2
#Mann= 3 ,-1,0
       0      .1       0   213.9    .045       0   268.2      .1       0
Bank Sta=213.9,268.2
XS Rating Curve= 0 ,0
Exp/Cntr(USF)=0,0
Exp/Cntr=0.3,0.1

Type RM Length L Ch R = 1 ,96531   ,267,253.9,237.8
XS GIS Cut Line= 2
2348393.75757843686606.0919174642349060.08345596686769.461072012
#Sta/Elev= 30
       0 2805.12    10.7 2797.29    27.7 2781.31    43.7 2768.66    64.3  2754.9
    77.3  2743.9   117.8 2717.52   134.3 2704.25   142.5 2694.94   167.2 2674.71
   171.3 2672.25   179.6    2671   193.1 2670.93   229.5 2670.95   241.4 2671.43
   270.2 2677.24   290.8  2677.3   303.1  2679.4   344.3 2673.76   358.5 2677.87
     369 2679.04     402 2679.11   414.3 2680.55   430.8 2679.46   447.3 2686.71
   480.8 2694.17   521.4 2698.77   607.9 2703.47   632.6 2702.64   686.1 2704.68
#Mann= 3 ,-1,0
       0      .1       0   179.6    .045       0   229.5      .1       0
Bank Sta=179.6,229.5
XS Rating Curve= 0 ,0
Exp/Cntr(USF)=0,0
Exp/Cntr=0.3,0.1

Type RM Length L Ch R = 1 ,96277   ,295.4,287.2,271.1
XS GIS Cut Line= 2
2348445.15461581686971.3780045992348861.83774033686804.337633095
#Sta/Elev= 30
       0 2757.31    20.5 2753.95    33.4 2750.12    46.3 2748.01    74.8 2740.27
    93.8 2733.38   105.5 2727.38   127.1 2713.22   136.3 2705.34   142.4 2698.61
   171.3 2671.81   175.6 2670.06   191.7 2669.99   225.5 2669.94   231.7 2669.97
   240.3 2670.78   257.5 2674.88   274.7  2676.5     284 2675.78   305.5 2679.41
   313.5 2679.57   326.5 2683.23   343.7 2678.13   363.9 2680.66   373.9 2680.71
   386.8 2678.37   399.7 2680.14   412.7 2680.01   429.9 2682.81   448.9 2687.61
#Mann= 3 ,-1,0
       0      .1       0   191.7    .045       0   231.7      .1       0
Bank Sta=191.7,231.7
XS Rating Curve= 0 ,0
Exp/Cntr(USF)=0,0
Exp/Cntr=0.3,0.1

Type RM Length L Ch R = 1 ,95990   ,215,207.8,203.6
XS GIS Cut Line= 2
2348711.31784513687299.9519221732348966.46742358686890.611231564
#Sta/Elev= 30
       0 2706.54    34.6 2701.15    69.4 2699.78    99.9 2700.72   110.1 2700.23
   130.5 2700.52   149.4 2697.24   158.8 2697.06   168.2 2695.05   182.4 2686.76
   194.3  2684.1   200.1 2681.92   215.4 2669.93   220.1 2668.71   234.2 2668.48
   258.7 2668.47   269.8 2668.48   284.3 2669.14   298.8 2673.63   304.6 2674.48
   314.4 2674.78   323.8 2676.27   337.9    2677   391.7 2677.18   400.4  2678.2
     410 2677.44   432.4 2678.31   455.6 2681.79     478 2686.73   482.3 2687.01
#Mann= 3 ,-1,0
       0      .1       0   234.2    .045       0   269.8      .1       0
Bank Sta=234.2,269.8
XS Rating Curve= 0 ,0
Exp/Cntr(USF)=0,0
Exp/Cntr=0.3,0.1

Type RM Length L Ch R = 1 ,95782   ,135.4,132.9,131.4
XS GIS Cut Line= 2
2348962.79620663687362.362610427  2349140.850229 686875.92636374
#Sta/Elev= 30
       0 2723.61      14 2719.22    62.2 2701.31    77.9  2692.9    86.5 2689.19
   120.5 2676.34     133 2672.23   154.2 2668.34   182.9 2668.09   214.7  2668.1
   222.8 2668.12   231.3  2669.5   239.8 2669.63   244.1 2670.29   252.6 2673.22
   278.1 2672.75   290.9 2675.48   307.9 2676.69   326.3 2676.96   341.9 2675.97
   360.6 2676.48   379.3 2675.56   413.6 2677.42   418.7 2678.31   427.2 2681.36
   432.3 2681.72   469.5 2689.33   478.3 2690.23   486.8 2692.47     518 2698.52
#Mann= 3 ,-1,0
       0      .1       0   154.2    .045       0   214.7      .1       0
Bank Sta=154.2,214.7
XS Rating Curve= 0 ,0
Exp/Cntr(USF)=0,0
Exp/Cntr=0.3,0.1

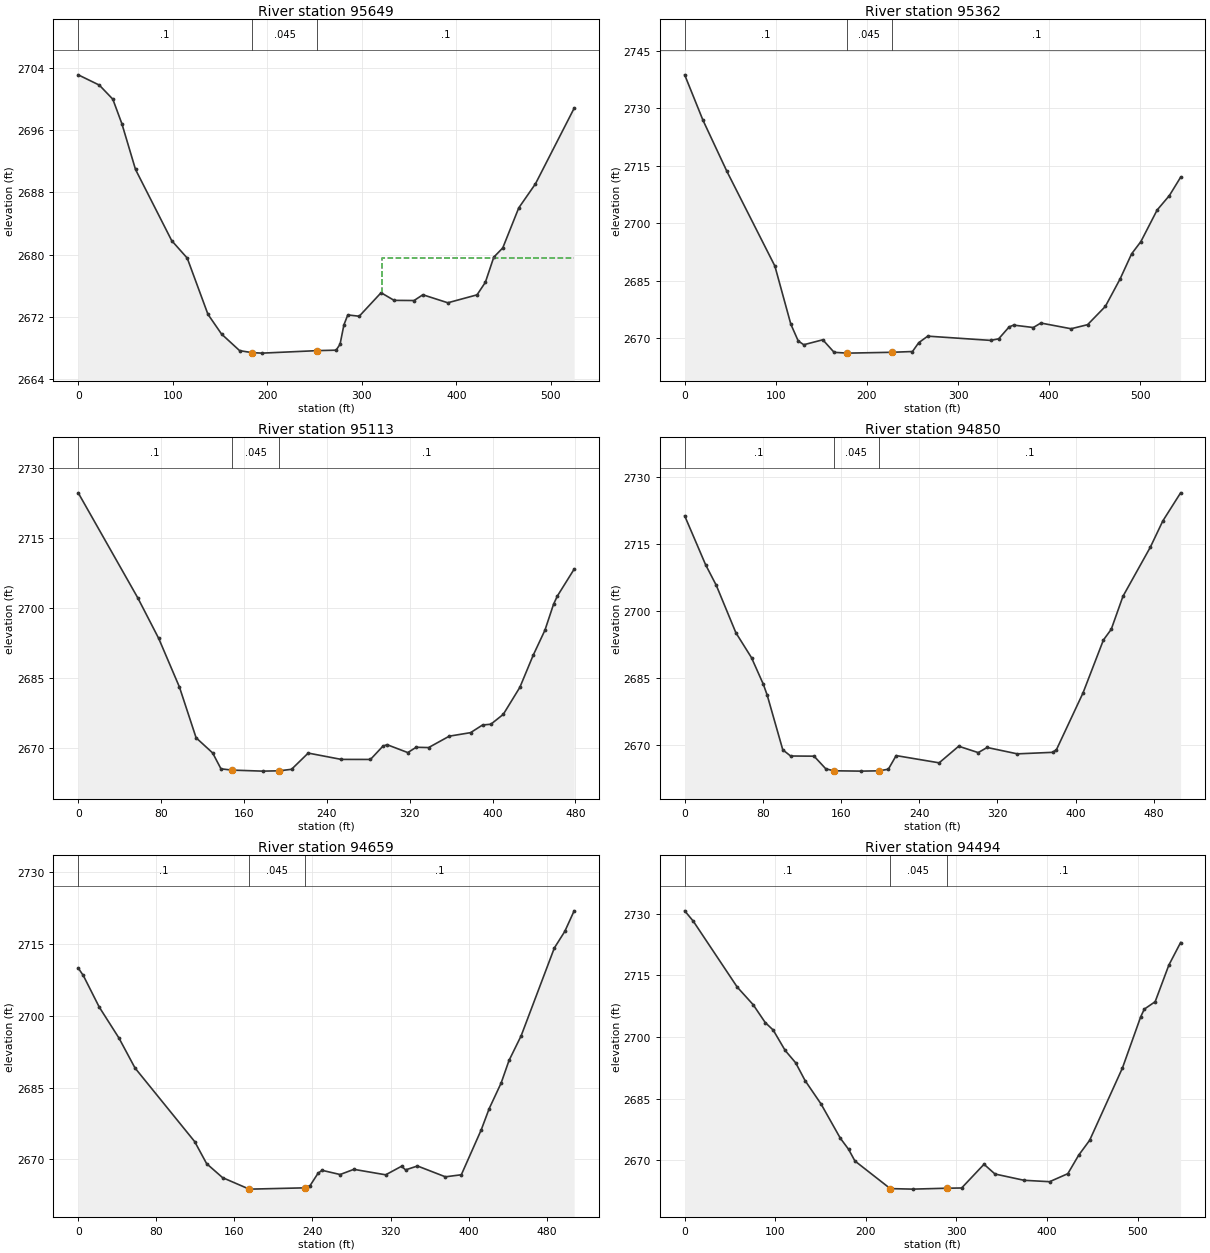
Type RM Length L Ch R = 1 ,95649   ,269.5,286.9,286.9
XS GIS Cut Line= 4
  2349039.006634687423.7704360572349145.43893393687262.066137605
2349167.30034298687172.6331005732349267.98070599686956.082282283
#Sta/Elev= 30
       0  2703.1    22.3 2701.78    36.6 2699.97    46.2 2696.81    60.6 2690.94
    98.9 2681.79   115.3 2679.55   137.2 2672.33   151.6 2669.79   170.7 2667.66
     184  2667.4   194.5 2667.34   252.8 2667.66   272.7 2667.72   276.9 2668.47
     281 2670.97   285.1 2672.25   297.2 2672.08   320.3  2675.1   334.1 2674.12
   355.2  2674.1   364.5 2674.84   390.9 2673.81   421.8 2674.83   430.6 2676.44
   439.5 2679.67     449 2680.86   465.9    2686   483.6  2689.1   524.5 2698.81
#Mann= 3 ,-1,0
       0      .1       0     184    .045       0   252.8      .1       0
#XS Ineff= 2 , 0
                          321.54         2679.52
Permanent Ineff=
       F       F
Bank Sta=184,252.8
XS Rating Curve= 0 ,0
Exp/Cntr(USF)=0,0
Exp/Cntr=0.3,0.1

Type RM Length L Ch R = 1 ,95362   ,260.2,249.2,243.5
XS GIS Cut Line= 3
2349285.67403699687559.4624849172349431.71696117687234.642877687
 2349482.0765902687053.348213186
#Sta/Elev= 30
       0  2738.7      20  2726.9    46.4 2713.49      99 2688.82   116.5 2673.66
   124.6 2669.29   130.7  2668.3   151.6 2669.59     164 2666.32   177.9 2666.12
   179.1 2666.11   227.5 2666.33     250 2666.53   256.9 2668.84   266.8 2670.54
   335.8 2669.43   344.6 2669.84   356.1 2672.95     361 2673.42   382.6 2672.79
   390.9 2673.96   424.1 2672.47   442.2 2673.53   461.7  2678.3   477.9 2685.47
   490.5    2692   500.7 2695.21   518.5 2703.43     532 2707.22   544.3 2711.99
#Mann= 3 ,-1,0
       0      .1       0   177.9    .045       0   227.5      .1       0
Bank Sta=177.9,227.5
XS Rating Curve= 0 ,0
Exp/Cntr(USF)=0,0
Exp/Cntr=0.3,0.1

Type RM Length L Ch R = 1 ,95113   ,264.9,262.6,261.1
XS GIS Cut Line= 2
2349600.42171841687594.7142252362349629.82796569687116.957181034
#Sta/Elev= 30
       0 2724.68    57.6 2702.17    77.7 2693.53    97.7 2683.14   113.8 2672.28
   129.8 2669.03   137.8 2665.64   148.4 2665.37   177.9 2665.15   194.1 2665.22
   205.9 2665.54     222 2669.01   253.9 2667.66   282.1 2667.65   294.1 2670.49
   298.1 2670.81   318.1 2669.12   326.2 2670.25   338.2 2670.19   358.2 2672.63
   378.7 2673.38   390.3 2675.02   398.3 2675.18   410.3  2677.3   426.3 2683.08
   439.1 2689.91   450.5  2695.3   458.8 2700.84   462.4 2702.57   478.7 2708.36
#Mann= 3 ,-1,0
       0      .1       0   148.4    .045       0   194.1      .1       0
Bank Sta=148.4,194.1
XS Rating Curve= 0 ,0
Exp/Cntr(USF)=0,0
Exp/Cntr=0.3,0.1

Type RM Length L Ch R = 1 ,94850   ,196.3,191.8,187.3
XS GIS Cut Line= 2
2349877.70943638687597.5419650022349866.92298719687090.188660013
#Sta/Elev= 30
       0 2721.31    21.4 2710.36    32.4 2705.71    52.4 2695.11    68.4 2689.52
    80.4 2683.61    84.4 2681.17   100.4 2668.88   108.4  2667.5   132.4 2667.46
   144.4 2664.63   152.4 2664.19   180.4 2664.11   199.1 2664.18   208.4 2664.54
   216.4 2667.59   260.4 2665.97   280.4 2669.69   300.4 2668.26   309.5 2669.41
   340.4 2667.98   376.4 2668.32   380.4  2668.9   407.6 2681.62   428.5 2693.49
   436.5 2695.88   448.5 2703.28   476.5 2714.28   489.3 2720.17   507.5 2726.46
#Mann= 3 ,-1,0
       0      .1       0   152.4    .045       0   199.1      .1       0
Bank Sta=152.4,199.1
XS Rating Curve= 0 ,0
Exp/Cntr(USF)=0,0
Exp/Cntr=0.3,0.1

Type RM Length L Ch R = 1 ,94659   ,166.3,164.5,161.6
XS GIS Cut Line= 2
2350104.01800869 687602.268169592350005.81673209687103.707842214
#Sta/Elev= 30
       0 2709.97     5.2 2708.42    21.5 2701.84    41.7 2695.37    58.2  2689.1
   119.3 2673.74   131.6 2669.12   147.9 2666.21   174.5 2663.87   176.4 2663.81
   232.4 2664.08   237.6 2664.56   245.7 2667.12   249.8 2667.74   268.3 2666.86
   282.4 2667.94     315  2666.8   331.3 2668.59   335.4 2667.83   347.6 2668.64
   376.2 2666.38   392.5 2666.81   412.9 2676.19     421  2680.6   433.3 2685.97
   441.4 2690.69   453.8 2695.83   487.8 2714.16   498.5 2717.62   508.1 2721.92
#Mann= 3 ,-1,0
       0      .1       0   174.5    .045       0   232.4      .1       0
Bank Sta=174.5,232.4
XS Rating Curve= 0 ,0
Exp/Cntr(USF)=0,0
Exp/Cntr=0.3,0.1

Type RM Length L Ch R = 1 ,94494   ,237.1,236.5,243.8
XS GIS Cut Line= 4
2350319.57857387687609.8346721592350246.83885317687452.473738245
2350205.62264069687307.739689062 2350183.8838562687085.246830975
#Sta/Elev= 30
       0 2730.73     9.5 2728.21      58 2712.17    75.6 2707.88    88.9 2703.54
    97.7 2701.71   110.9 2696.75   122.5 2693.74   132.9 2689.41   150.5 2683.72
   171.8 2675.38   180.9 2672.69   187.9 2669.84   226.9 2663.12   251.6 2662.99
   289.1 2663.21   305.7 2663.27   330.4 2669.04   342.5 2666.67   374.6 2665.14
   402.8  2664.8   422.9 2666.75   434.9 2671.26     447 2674.88   483.2 2692.49
   503.3 2704.91   507.3  2706.8   519.3 2708.61   534.4 2717.52   547.4 2723.02
#Mann= 3 ,-1,0
       0      .1       0   226.9    .045       0   289.1      .1       0
Bank Sta=226.9,289.1
XS Rating Curve= 0 ,0
Exp/Cntr(USF)=0,0
Exp/Cntr=0.3,0.1

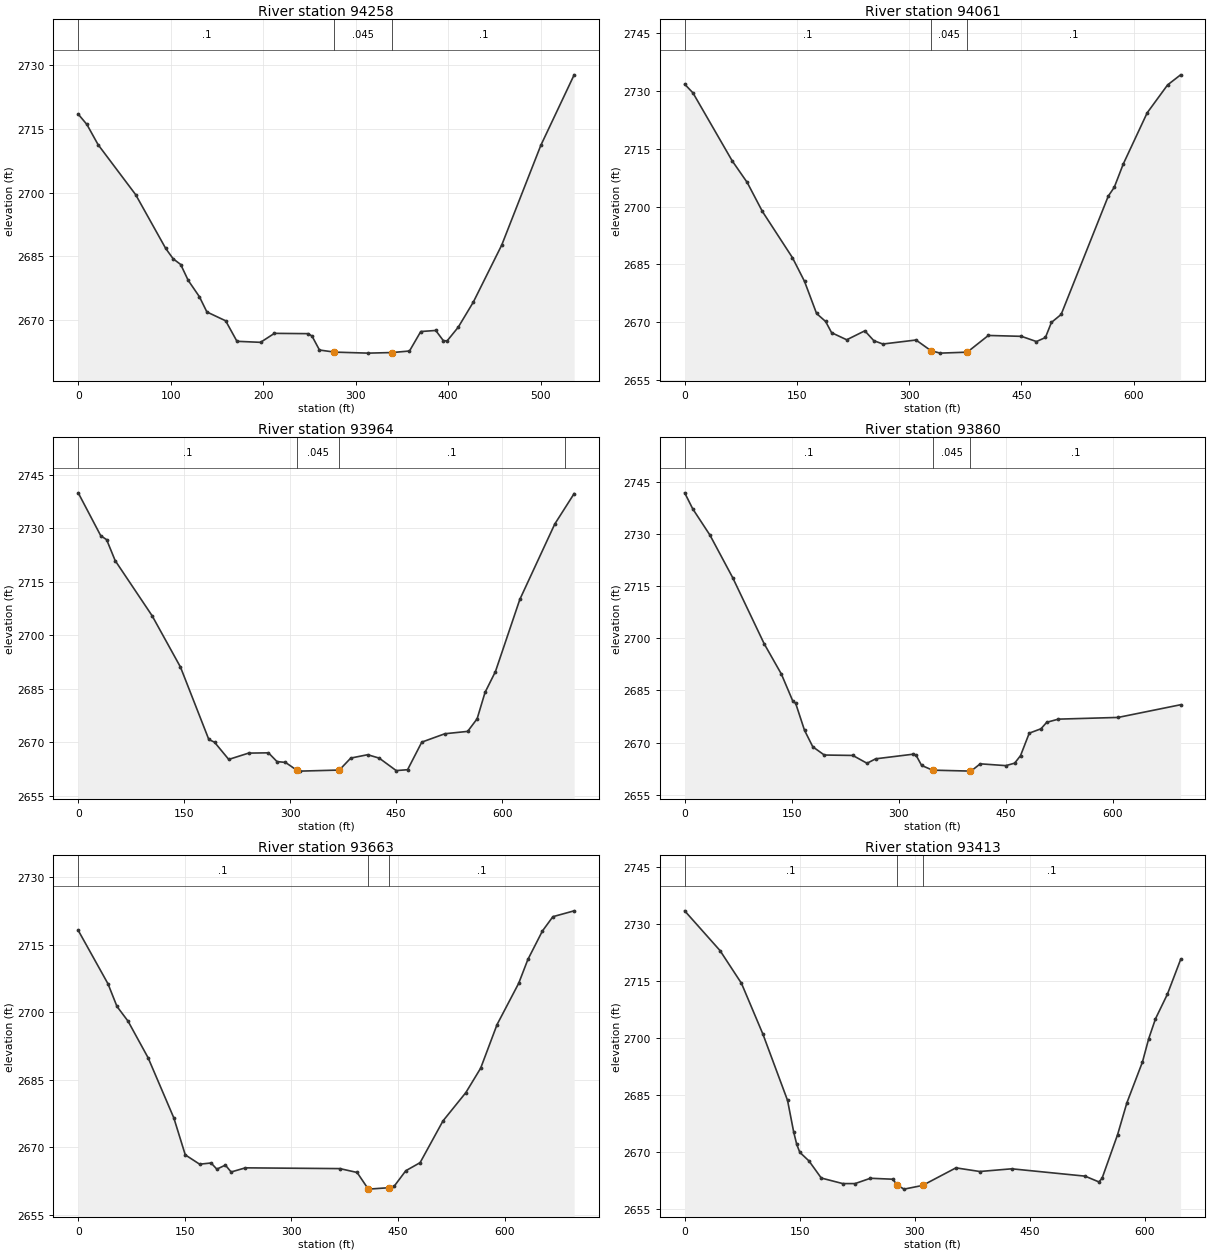
Type RM Length L Ch R = 1 ,94258   ,191.9,196.8,206.8
XS GIS Cut Line= 2
 2350481.7152264687554.426522014 2350393.5858756687025.650417221
#Sta/Elev= 30
       0 2718.44     9.4    2716    21.5 2711.25    62.1  2699.5    94.5 2686.88
   102.6 2684.42   110.8 2683.07   118.9 2679.34     131  2675.5   139.1 2671.91
   159.4 2669.83   171.6 2665.01   197.1 2664.77   212.1 2666.88   248.6 2666.81
   252.7 2666.25   260.8 2662.96     277 2662.47   313.5 2662.23   339.6 2662.37
   358.1 2662.73   370.3 2667.31   386.5 2667.56   394.6 2665.19   398.7 2665.09
   410.8 2668.33   427.1 2674.23   457.8 2687.64   500.1 2711.11   536.1 2727.68
#Mann= 3 ,-1,0
       0      .1       0     277    .045       0   339.6      .1       0
Bank Sta=277,339.6
XS Rating Curve= 0 ,0
Exp/Cntr(USF)=0,0
Exp/Cntr=0.3,0.1

Type RM Length L Ch R = 1 ,94061   ,97.3,96.9,94.8
XS GIS Cut Line= 3
2350584.95246591687592.1962437852350637.83007639687154.067471242
2350635.31209494 686932.48510352
#Sta/Elev= 30
       0 2731.73    11.1 2729.46    63.5 2711.86    83.6 2706.25   103.8 2698.77
   144.1 2686.75   160.2 2680.62   176.3  2672.3   188.4 2670.23   196.4 2667.32
   216.6 2665.49   240.8 2667.81   252.8 2665.26   264.9 2664.39   309.2 2665.43
   329.2 2662.66   341.5 2662.03   377.7 2662.28   405.9 2666.61   450.2 2666.38
   470.2 2665.03   482.2 2666.08   490.2 2669.98   503.2 2672.05   566.2 2702.72
   574.2    2705   586.2 2711.03   618.2  2724.3   645.5 2731.54   662.9 2734.15
#Mann= 3 ,-1,0
       0      .1       0   329.2    .045       0   377.7      .1       0
Bank Sta=329.2,377.7
XS Rating Curve= 0 ,0
Exp/Cntr(USF)=0,0
Exp/Cntr=0.3,0.1

Type RM Length L Ch R = 1 ,93964   ,108.2,104.1,90.6
XS GIS Cut Line= 3
 2350689.4258711687597.1980102682350738.22824189687080.566015955
2350697.84007296686902.184936485
#Sta/Elev= 30
       0 2739.87    31.9 2727.84    40.2 2726.74    52.3 2720.87   104.5 2705.44
   144.7 2691.03   184.8 2670.74   192.9 2669.96     213 2665.14   241.1 2666.91
   269.2 2666.99   281.3 2664.54   293.3  2664.3   309.4 2662.11   313.4 2661.86
   369.5 2662.16   385.7 2665.52   409.6 2666.46   425.9 2665.51     450 2662.01
   466.1 2662.26   486.2 2669.99   518.9 2672.34   551.1    2673   564.5 2676.53
   575.7 2683.93   590.4 2689.76   624.9 2709.98   674.4 2731.13   701.8 2739.66
#Mann= 4 ,-1,0
       0      .1       0   309.4    .045       0   369.5      .1       0
  688.93     .12       0
Bank Sta=309.4,369.5
XS Rating Curve= 0 ,0
Exp/Cntr(USF)=0,0
Exp/Cntr=0.3,0.1

Type RM Length L Ch R = 1 ,93860   ,191.1,197.3,196.8
XS GIS Cut Line= 5
2350811.08912748687604.4709982592350827.28726068687290.833611581
2350807.26409245687184.1235916482350830.57311445687071.258853555
2350915.68822899686939.276074607
#Sta/Elev= 30
       0  2741.8    11.3 2737.19    35.3 2729.68    67.4 2717.36   111.4  2698.4
   135.5 2689.68   151.5 2681.93   155.5 2681.28   167.9 2673.53   179.5 2668.78
   195.6 2666.41   235.6 2666.29   255.5 2664.04   267.6 2665.32   319.8 2666.64
   323.9 2666.46     332 2663.42   347.3 2662.06   400.4 2661.79   401.2 2661.78
   414.1 2663.88   450.1 2663.36   462.4 2664.08   470.6 2666.24   482.8  2672.7
   499.2 2673.95   507.3 2675.82   523.7 2676.73   607.3 2677.22   694.9 2680.87
#Mann= 3 ,-1,0
       0      .1       0   347.3    .045       0   400.4      .1       0
Bank Sta=347.3,400.4
XS Rating Curve= 0 ,0
Exp/Cntr(USF)=0,0
Exp/Cntr=0.3,0.1

Type RM Length L Ch R = 1 ,93663   ,241.2,249.1,254.2
XS GIS Cut Line= 3
2350949.27453629687598.7657604932351015.01881451687041.206908882
2351083.22903872686923.295868535
#Sta/Elev= 30
       0 2718.19    41.9 2706.31    54.5 2701.29    70.1 2698.01    98.3 2689.88
   134.5 2676.51   150.6  2668.3   170.8 2666.23   186.9  2666.5     195 2665.13
     207 2666.03   215.1  2664.5   235.2 2665.42   368.1 2665.25   392.3 2664.39
   407.6  2660.8   408.4 2660.69   436.6    2661   444.6 2661.37   460.8 2664.78
   480.9 2666.57   513.1 2675.85   545.3 2682.15   566.1 2687.57   589.2 2697.27
   619.6 2706.43   632.5 2711.72     653 2718.06   667.7 2721.23   697.6 2722.53
#Mann= 3 ,-1,0
       0      .1       0   407.6    .045       0   436.6      .1       0
Bank Sta=407.6,436.6
XS Rating Curve= 0 ,0
Exp/Cntr=0.3,0.1

Type RM Length L Ch R = 1 ,93413   ,235.9,227.3,215.3
XS GIS Cut Line= 4
2351150.26174672687619.1924858362351162.69622302687358.068483469
 2351200.2946384  687300.68406022351252.84617622686988.142813449
#Sta/Elev= 30
       0 2733.52    46.1 2723.06    74.1 2714.43   102.1 2701.04   134.2 2683.62
   142.2 2675.31   146.2 2672.03   150.2 2669.95   162.2 2667.67   178.2 2663.18
   206.2 2661.72   222.3 2661.72   242.3 2663.12   271.4 2662.87   277.6 2661.27
   286.2 2660.26   310.3 2661.23   353.9 2665.86     385  2664.9   426.7 2665.61
   522.3 2663.68   540.4 2662.16   544.5  2663.1   564.8 2674.62   576.9 2682.99
   597.2 2693.72   605.3 2699.81   614.2 2705.09   629.7 2711.55     647 2720.71
#Mann= 3 ,-1,0
       0      .1       0   277.6    .045       0   310.3      .1       0
Bank Sta=277.6,310.3
XS Rating Curve= 0 ,0
Exp/Cntr(USF)=0,0
Exp/Cntr=0.3,0.1

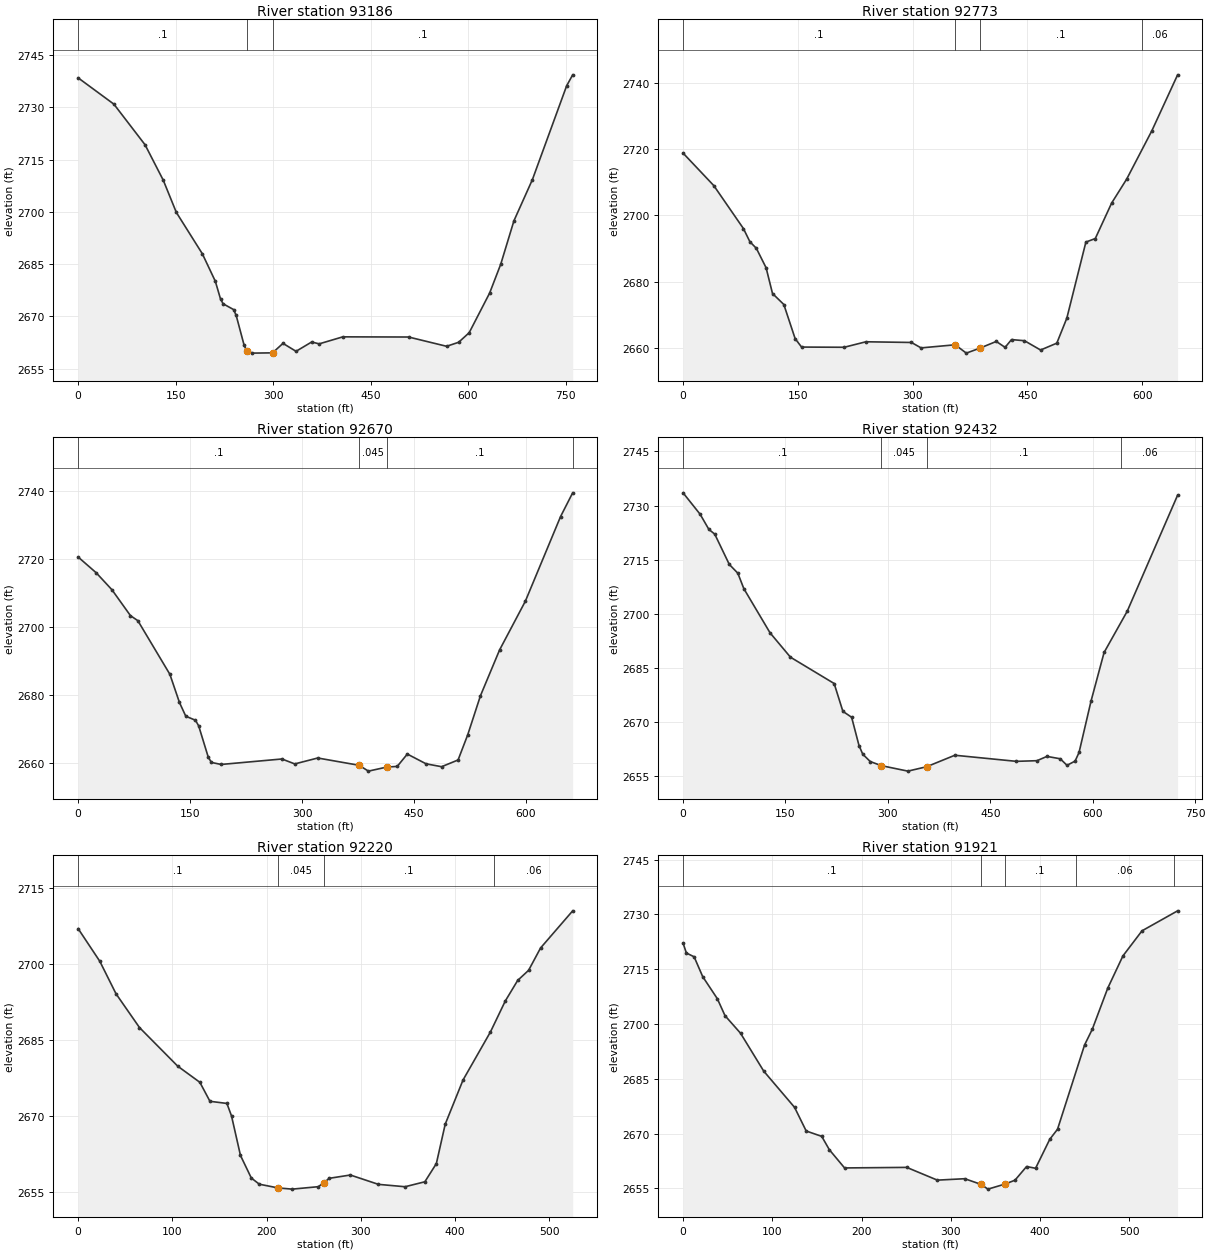
Type RM Length L Ch R = 1 ,93186   ,406.4,413.2,412.3
XS GIS Cut Line= 3
2351351.47566647687720.0848080592351370.86261908687300.117522513
2351425.60733294 686964.00976244
#Sta/Elev= 30
       0 2738.42      55 2730.88     103 2719.22     131 2709.06   151.1 2699.83
   191.1 2687.97   211.1 2680.08   219.1 2674.99   223.1 2673.62   239.2 2671.96
   243.2 2670.28   255.2 2661.88   259.2 2660.13   267.2 2659.47   299.2 2659.55
   315.2 2662.27   335.3 2659.99   359.3 2662.66   370.9 2662.13   407.3 2664.14
   508.5 2664.09     567 2661.43   585.5 2662.58   601.7 2665.32   633.2  2676.7
   650.3 2684.98   670.6 2697.43     699 2709.23   751.7 2736.14     761 2739.29
#Mann= 3 ,-1,0
       0      .1       0   259.2    .045       0   299.2      .1       0
Bank Sta=259.2,299.2
XS Rating Curve= 0 ,0
Exp/Cntr=0.3,0.1

Type RM Length L Ch R = 1 ,92773   ,102.1,103,103.5
XS GIS Cut Line= 2
2351632.02968887687683.9244987672351838.95587013687071.575818529
#Sta/Elev= 30
       0 2718.83    40.2    2709    78.9 2696.03    87.3 2692.07    95.8 2690.06
   108.5  2684.2   116.9 2676.41   131.7 2673.09   146.5 2662.76   154.9 2660.23
   210.6 2660.17     239 2661.83   298.5 2661.62   311.1 2659.98   355.7 2660.92
   370.2  2658.4   387.8 2659.89   409.4 2661.93   420.9 2660.14   429.3 2662.49
   446.2 2662.15   467.3 2659.34   488.5 2661.41   501.6 2668.97   526.5 2691.95
   538.8 2693.02   560.2 2703.75   579.8 2710.97   612.7 2725.57   646.4 2742.48
#Mann= 4 ,-1,0
       0      .1       0   355.7    .045       0   387.8      .1       0
     600     .06       0
Bank Sta=355.7,387.8
XS Rating Curve= 0 ,0
Exp/Cntr(USF)=0,0
Exp/Cntr=0.3,0.1

Type RM Length L Ch R = 1 ,92670   ,238.3,237.9,243.6
XS GIS Cut Line= 2
2351704.06481031687735.7253372312351943.72004858687118.063426543
#Sta/Elev= 30
       0 2720.61    24.2 2715.98    45.3 2710.98    70.1 2703.37      80 2701.89
   122.9 2686.12   135.7 2677.85   144.2  2673.8   157.2 2672.61   161.5 2670.94
   174.4  2661.7   178.6 2660.21   191.5 2659.61     273 2661.22   290.2 2659.77
     321 2661.51   376.3 2659.37   388.9 2657.65   413.2 2658.83   427.5 2659.04
     441 2662.67   466.1  2659.8   486.9 2658.95     509 2660.93   521.9 2668.32
     539 2679.84   564.6 2693.29   599.1 2707.61   646.3 2732.51   662.5 2739.49
#Mann= 4 ,-1,0
       0      .1       0   376.3    .045       0   413.2      .1       0
  662.53     .06       0
Bank Sta=376.3,413.2
XS Rating Curve= 0 ,0
Exp/Cntr=0.3,0.1

Type RM Length L Ch R = 1 ,92432   ,216.1,212,217.7
XS GIS Cut Line= 4
2351828.61115019687860.6586485282351914.79197246687628.541278462
2352020.74858849687516.3519203052352179.03013482687235.344636918
#Sta/Elev= 30
       0 2733.55      25 2727.61    37.8 2723.42    46.4 2722.11    67.7 2713.72
    80.2 2711.29      89 2707.01   127.4 2694.77   157.3 2688.02   221.3 2680.73
   234.1 2673.02   246.9 2671.38   257.7 2663.55   263.2 2661.15   274.2 2659.11
   290.6 2657.97   329.3 2656.46   356.8 2657.68   398.1 2660.86   488.2 2659.17
   518.4 2659.35     533 2660.54   552.5 2659.88   562.4 2658.07   574.2 2659.24
     580 2661.62   597.6 2675.88   616.7 2689.33   650.5 2700.72   724.4  2732.9
#Mann= 4 ,-1,0
       0      .1       0   290.6    .045       0   356.8      .1       0
  641.92     .06       0
Bank Sta=290.6,356.8
XS Rating Curve= 0 ,0
Exp/Cntr(USF)=0,0
Exp/Cntr=0.3,0.1

Type RM Length L Ch R = 1 ,92220   ,292.3,298.6,300.5
XS GIS Cut Line= 4
2351953.55453244687838.527059236 2352105.4823021687732.150851575
2352142.99131647687690.5433859472352382.45627823687538.931571757
#Sta/Elev= 30
       0  2706.9      23 2700.47    40.2 2694.07    65.1 2687.42   105.7 2679.81
   129.2 2676.63   139.9 2672.89   157.9 2672.47   162.8    2670   172.3 2662.22
   183.8 2657.78   192.3 2656.56   212.1 2655.83   227.2 2655.59   254.9 2656.07
   260.7 2656.84   266.5 2657.72   288.9 2658.37   318.7 2656.53     347 2656.06
     368 2657.04   380.2 2660.62   389.6 2668.38   408.5 2677.08   437.6 2686.55
   453.4 2692.66   466.5  2696.7   478.1 2698.69   490.8 2703.09   524.9 2710.41
#Mann= 4 ,-1,0
       0      .1       0   212.1    .045       0   260.7      .1       0
  441.49     .06       0
Bank Sta=212.1,260.7
XS Rating Curve= 0 ,0
Exp/Cntr=0.3,0.1

Type RM Length L Ch R = 1 ,91921   ,228.6,222.7,222
XS GIS Cut Line= 2
2352004.74767193688050.4711342282352516.45451568687837.259949331
#Sta/Elev= 30
       0 2722.12     3.7 2719.43    12.4 2718.38      22 2712.96    38.4 2706.92
      47 2702.28    64.4 2697.47    90.4  2687.1     125 2677.17     138 2670.71
   155.4 2669.24     164 2665.57     181  2660.6   250.7 2660.75     285 2657.26
   315.7 2657.65     334  2656.1   341.7  2654.8   360.5 2656.16     372 2657.24
     385 2660.98   395.1 2660.51     411 2668.44   419.7 2671.19     450 2694.25
   458.7 2698.58     476 2709.81     493 2718.63   514.4  2725.5   554.3 2730.97
#Mann= 5 ,-1,0
       0      .1       0     334    .045       0   360.5      .1       0
     440     .06       0     550      .1       0
Bank Sta=334,360.5
XS Rating Curve= 0 ,0
Exp/Cntr(USF)=0,0
Exp/Cntr=0.3,0.1

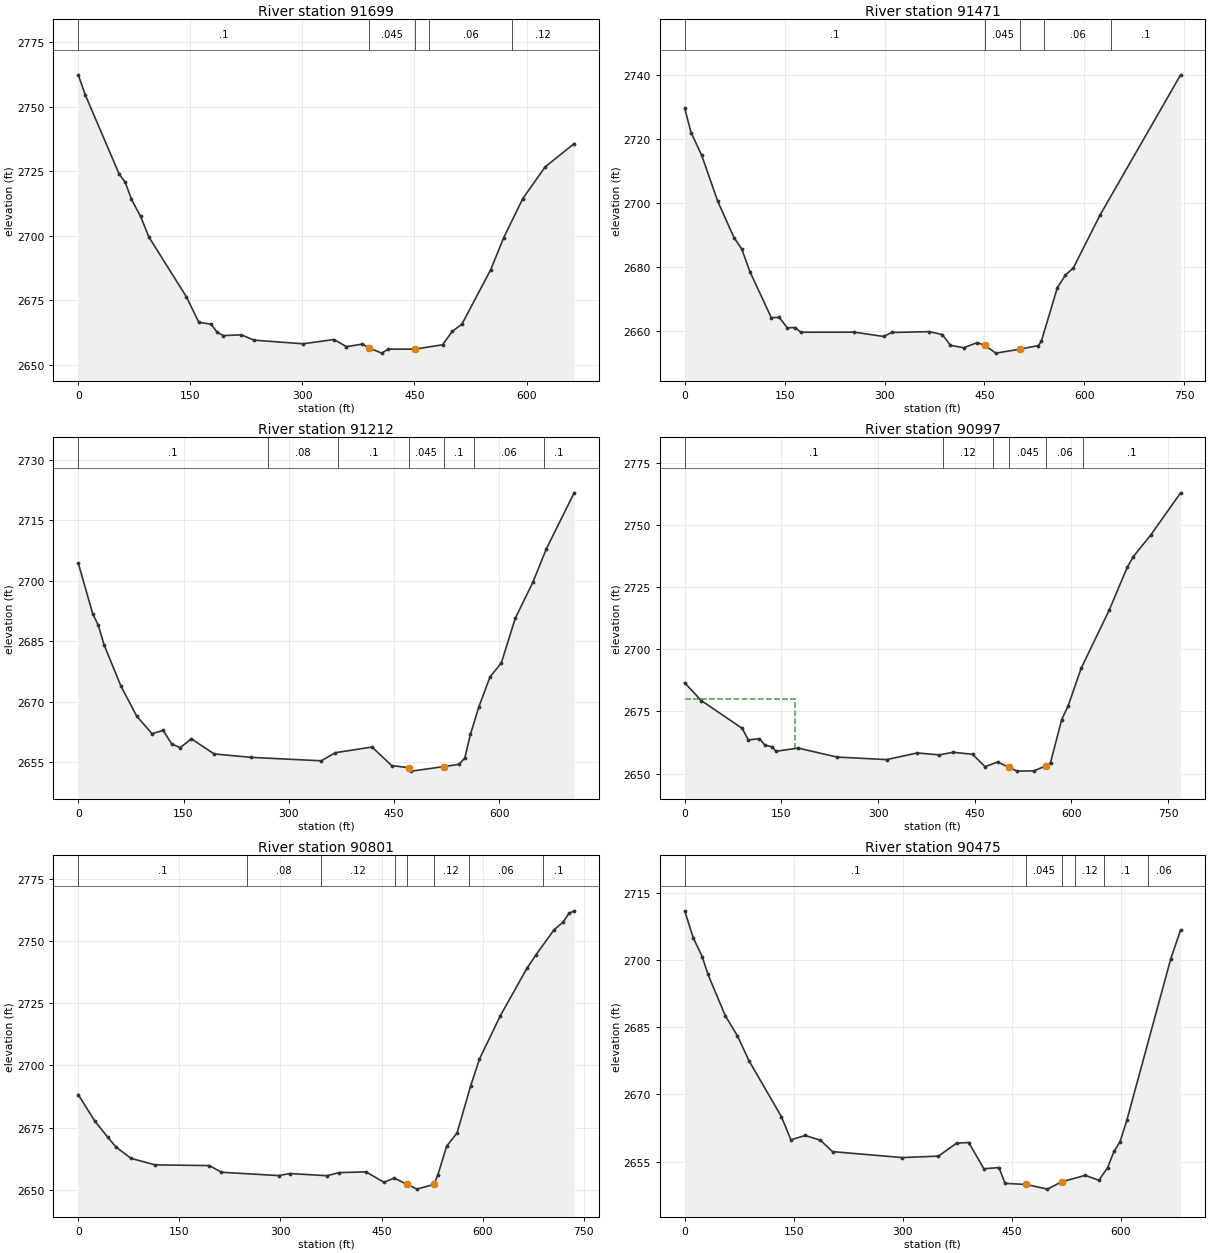
Type RM Length L Ch R = 1 ,91699   ,219.6,228.1,234.7
XS GIS Cut Line= 3
2351958.67022258688240.6593153262352290.54190888688166.404666125
2352592.19781776 688049.34433225
#Sta/Elev= 30
       0 2762.38     9.7 2754.44    54.8 2723.91      63  2720.7    71.2 2714.15
    83.5 2707.47    94.6 2699.51   144.9 2676.28   161.4 2666.43   177.8 2665.73
     186 2662.57   194.2 2661.31   218.5 2661.58   235.2 2659.53   300.8 2658.12
   342.3 2659.77     359 2657.01   380.4    2658     389 2656.52   406.2  2654.5
   414.8 2656.04   450.5 2656.04   487.6 2657.74   500.6 2662.93   513.5 2665.73
   552.1 2686.89   569.2 2699.12     595 2714.43     625 2726.72   663.7 2735.73
#Mann= 5 ,-1,0
       0      .1       0     389    .045       0   450.5      .1       0
  470.08     .06       0  580.08     .12       0
Bank Sta=389,450.5
XS Rating Curve= 0 ,0
Exp/Cntr=0.3,0.1

Type RM Length L Ch R = 1 ,91471   ,254.4,258.8,260.6
XS GIS Cut Line= 2
2351970.63388234688387.3448063652352712.60880578688327.645674594
#Sta/Elev= 30
       0 2729.67     9.6 2722.07    25.6 2714.92    49.7 2700.52      74 2689.22
    85.8 2685.57    97.9 2678.55     130 2664.15     142 2664.23     154 2660.97
   166.1 2661.06   174.1 2659.59   254.4 2659.61   298.5 2658.26   310.5 2659.51
   367.4 2659.77   386.8 2658.86   398.8  2655.5   418.9 2654.73     439 2656.34
     451 2655.44     467 2653.05   503.2 2654.28   530.8 2655.42   535.3 2656.72
   559.3 2673.48   571.4 2677.45   583.4 2679.71   623.5 2696.27   744.4 2740.14
#Mann= 5 ,-1,0
       0      .1       0     451    .045       0   503.2      .1       0
     540     .06       0     640      .1       0
Bank Sta=451,503.2
XS Rating Curve= 0 ,0
Exp/Cntr(USF)=0,0
Exp/Cntr=0.3,0.1

Type RM Length L Ch R = 1 ,91212   ,200.2,214.6,220.8
XS GIS Cut Line= 3
2351951.62640807688562.518222583 2352363.3547234688603.263074194
2352655.86179894688614.500863767
#Sta/Elev= 30
       0 2704.48    20.6  2691.9    28.7 2688.99    36.7 2684.23    60.8 2673.97
    83.4 2666.47   105.1 2662.15   121.1 2662.94   133.2 2659.59   145.3 2658.69
   161.3 2660.87   193.5 2657.13   245.7 2656.28   346.2 2655.42   366.3 2657.43
   418.6 2658.83   446.6 2654.23   470.9 2653.71   474.6 2652.86   520.8 2653.98
   542.7 2654.57   550.7 2656.12   558.7 2661.94   570.7 2668.77   586.7 2676.24
   602.7 2679.66   622.7 2690.78   647.7 2699.69   666.9 2707.97   706.5 2721.85
#Mann= 7 ,-1,0
       0      .1       0     270     .08       0     370      .1       0
   470.9    .045       0   520.8      .1       0  563.74     .06       0
  663.74      .1       0
Bank Sta=470.9,520.8
XS Rating Curve= 0 ,0
Exp/Cntr=0.3,0.1

Type RM Length L Ch R = 1 ,90997   ,193.2,196.3,196.1
XS GIS Cut Line= 3
2351940.13929868688621.7791052812352366.83296499688788.128827538
2352654.82706175688906.407662087
#Sta/Elev= 30
       0 2686.54    25.8 2679.38    89.1 2668.23    98.8 2663.56     116 2664.03
   124.5 2661.46   135.5 2660.79   141.7 2658.98   176.1 2660.26   236.2 2656.65
   313.4 2655.63   360.7 2658.31   394.8 2657.53   416.5 2658.57   446.5 2657.77
   465.9 2652.78   485.4 2654.67   502.5 2652.59   515.6 2650.99   541.6 2651.11
     561 2653.13   567.5 2654.46   584.8 2671.71   594.7 2677.17   615.1 2692.43
   658.3 2715.67   686.6 2733.06   695.8 2737.28   723.2 2746.11   769.3 2762.99
#Mann= 6 ,-1,0
       0      .1       0     400     .12       0  477.97      .1       0
   502.5    .045       0     561     .06       0  617.97      .1       0
#XS Ineff= 2 , 0
           171.4  2680.1
Permanent Ineff=
       F       F
Bank Sta=502.5,561
XS Rating Curve= 0 ,0
Exp/Cntr(USF)=0,0
Exp/Cntr=0.3,0.1

Type RM Length L Ch R = 1 ,90801   ,329.2,325.7,320.1
XS GIS Cut Line= 3
2351894.26703286688764.4290513562352260.34721001 688947.91742295
 2352555.0751855689087.496609251
#Sta/Elev= 30
       0 2688.26    24.5 2677.65    43.7 2671.15    55.8 2667.22    78.2  2662.6
     114 2659.97   194.5 2659.68   212.4    2657   297.4 2655.66   314.1 2656.49
     369  2655.6   386.9 2656.85     427 2657.15   453.6 2652.93   468.5 2654.67
   487.2 2652.24   502.2 2650.21   527.4  2652.1   533.5 2656.01   546.5 2667.48
     562 2672.87   581.9 2691.58   595.2 2702.57   626.2 2720.02   665.6 2739.08
   679.3  2744.6   705.8 2754.56   719.1 2757.63     728 2761.19   735.6 2762.18
#Mann= 8 ,-1,0
       0      .1       0     250     .08       0     360     .12       0
  469.49      .1       0   487.2    .045       0   527.4     .12       0
  579.49     .06       0  689.49      .1       0
Bank Sta=487.2,527.4
XS Rating Curve= 0 ,0
Exp/Cntr=0.3,0.1

Type RM Length L Ch R = 1 ,90475   ,319.9,319.2,315.3
XS GIS Cut Line= 3
2351696.34830824 689184.692079122351842.49300547689164.027669706
2352356.17895134689313.918418209
#Sta/Elev= 30
       0 2710.95    11.9 2704.88    24.1 2700.73    32.1 2696.75      56 2687.51
    72.5 2683.08    88.7 2677.45   133.1 2665.03   146.2 2659.85     166 2660.81
   186.9 2659.75   203.5 2657.21   299.4 2655.88   349.4 2656.21   374.4 2659.11
     391 2659.24   411.9 2653.39   432.7 2653.65     441 2650.13   470.2 2649.88
   499.4 2648.84     519 2650.48   551.5 2651.91   570.2 2650.81   582.1  2653.6
     591 2657.25   599.4 2659.46   608.7 2664.22   669.2 2700.28   682.7 2706.71
#Mann= 6 ,-1,0
       0      .1       0   470.2    .045       0     519      .1       0
   537.6     .12       0   577.6      .1       0   637.6     .06       0
Bank Sta=470.2,519
XS Rating Curve= 0 ,0
Exp/Cntr(USF)=0,0
Exp/Cntr=0.3,0.1

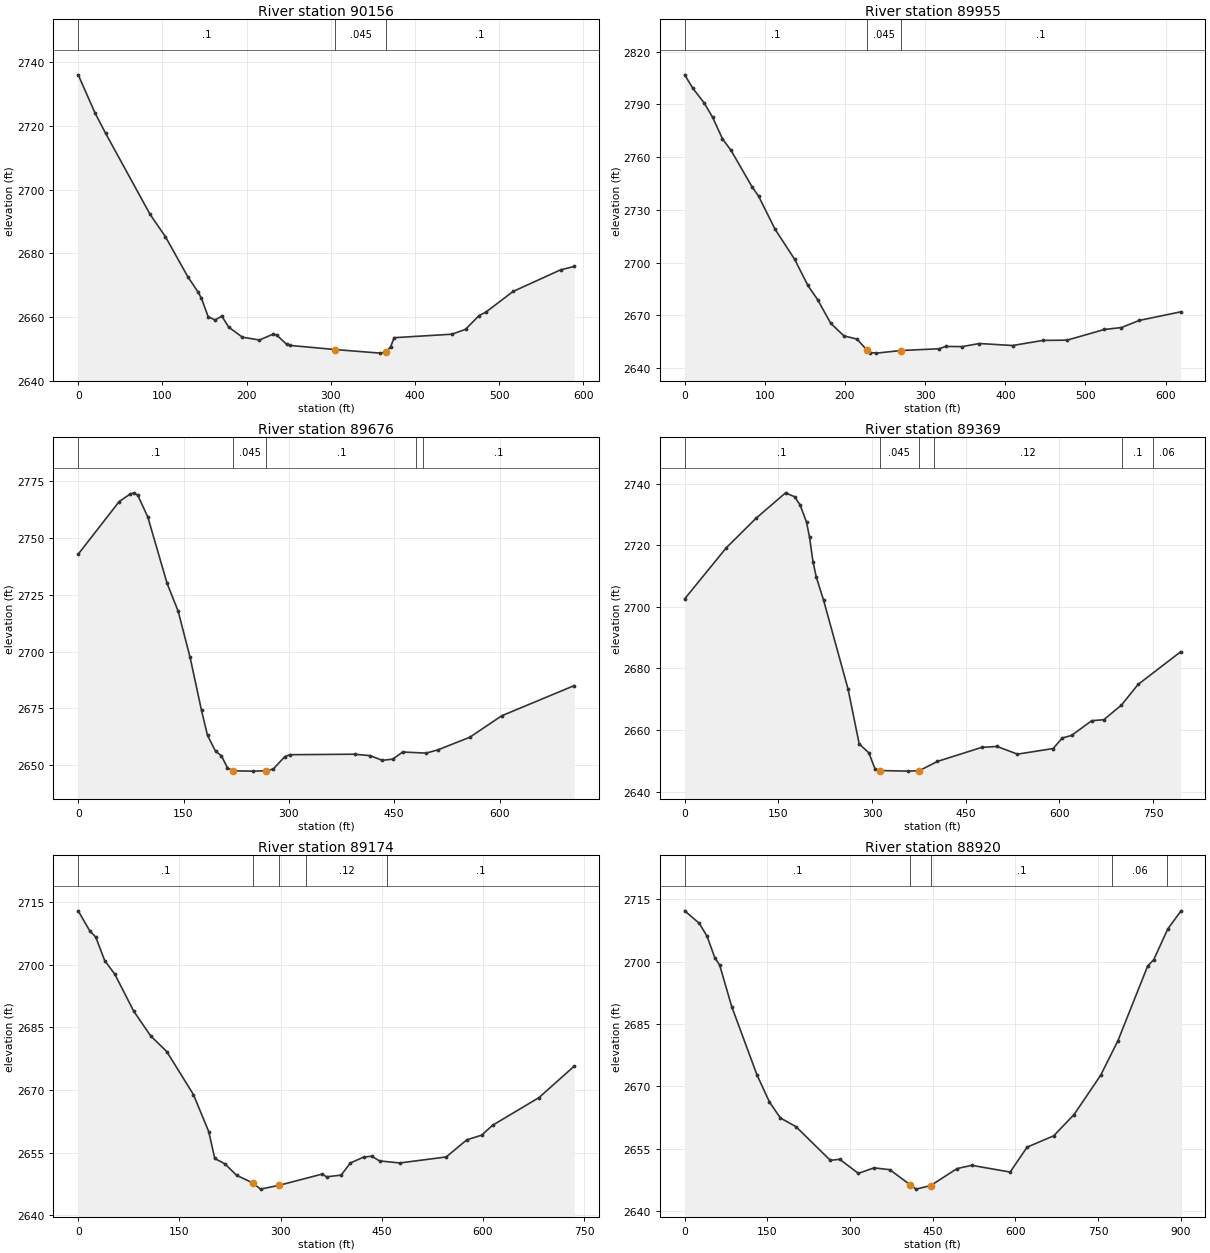
Type RM Length L Ch R = 1 ,90156   ,211.1,201.1,196.4
XS GIS Cut Line= 4
2351744.10899578689580.9874378252351997.26146598689536.660157251
2352121.17363829689566.6808384922352324.32337805689543.104870049
#Sta/Elev= 30
       0 2736.03      20 2724.04    32.6 2717.66    85.3 2692.27   103.6 2685.23
     130 2672.75   142.2 2667.95   146.3 2665.94   154.4 2660.09   162.5 2659.13
   170.6 2660.31   178.7 2656.87     195 2653.71   215.3 2652.83   231.5 2654.67
   235.6 2654.42   247.8 2651.42   251.8 2651.12   305.3 2649.83   358.8 2648.71
   365.82649.095   371.1 2650.75   375.2 2653.55   443.9 2654.65     460 2656.18
   476.1 2660.51   484.2 2661.58   516.4 2668.05     573 2674.85     589  2675.9
#Mann= 3 ,-1,0
       0      .1       0   305.3    .045       0   365.8      .1       0
Bank Sta=305.3,365.8
XS Rating Curve= 0 ,0
Exp/Cntr=0.3,0.1

Type RM Length L Ch R = 1 ,89955   ,294.4,278.9,266.7
XS GIS Cut Line= 3
 2351746.1254653689792.1304013452352105.25151249689713.467202439
2352341.72376645 689629.03557322
#Sta/Elev= 30
       0 2806.82    10.3 2799.08    24.4 2790.78    34.9 2782.61    47.1 2770.44
    57.9 2763.77      84 2743.13    92.2 2737.78   112.7    2719   137.2 2701.82
   153.6 2687.03   165.9 2678.83   182.2 2665.43   198.7 2658.26     215 2656.44
   227.3 2650.21   231.4 2648.79   239.3 2648.45   269.6 2649.93   317.4 2650.94
   325.6 2652.25   346.1 2652.16   367.6 2653.92     409 2652.79   447.2  2655.7
   476.9 2655.82   523.5  2661.9   544.9 2663.02   567.3 2667.09   618.7 2671.93
#Mann= 3 ,-1,0
       0      .1       0   227.3    .045       0   269.6      .1       0
Bank Sta=227.3,269.6
XS Rating Curve= 0 ,0
Exp/Cntr(USF)=0,0
Exp/Cntr=0.3,0.1

Type RM Length L Ch R = 1 ,89676   ,311.2,306.9,306
XS GIS Cut Line= 3
2351997.25708184690141.7766350122352256.44888217  689835.4582013
2352472.80836824689620.505967262
#Sta/Elev= 30
       0 2742.74    58.4 2765.87    74.1 2769.16    79.4 2769.68    84.8  2768.6
      99 2759.16   126.5 2729.98   142.3 2717.75   159.3 2697.44   175.6 2674.12
   184.1  2663.2   195.5 2656.27     204  2654.2   212.5 2648.91     221 2647.62
   249.4  2647.5     268 2647.65   277.8 2648.43   294.2 2653.89   301.8 2654.71
   393.8 2654.93   415.8 2654.29   432.9 2652.25   447.9 2652.77   462.1  2655.9
   495.3 2655.41   512.3 2656.85   557.7 2662.39   603.1 2671.81   706.2 2685.03
#Mann= 5 ,-1,0
       0      .1       0     221    .045       0     268      .1       0
  481.26     .12       0  491.26      .1       0
Bank Sta=221,268
XS Rating Curve= 0 ,0
Exp/Cntr=0.3,0.1

Type RM Length L Ch R = 1 ,89369   ,196.9,194.9,195.5
XS GIS Cut Line= 2
2352232.88772745690401.266562036 2352662.7214762 689733.48913094
#Sta/Elev= 30
       0 2702.62    66.7 2719.23   114.3 2728.82   161.6 2737.08   176.1  2735.8
   184.8 2733.14   195.1 2727.58   199.9 2722.68   205.6 2714.57   210.8 2709.66
   222.4 2702.22   261.7 2673.24   279.5 2655.47     295 2652.56   304.6 2647.43
   312.1 2646.83   356.9 2646.63   375.6 2646.77   404.7 2649.78   475.8 2654.36
   500.2 2654.65   532.9 2652.15     590 2653.97   604.7  2657.4   619.5 2658.22
   651.8 2663.02   671.2 2663.34   699.4 2668.09     726 2674.79   794.2 2685.41
#Mann= 6 ,-1,0
       0      .1       0   312.1    .045       0   375.6      .1       0
     400     .12       0     700      .1       0     750     .06       0
Bank Sta=312.1,375.6
XS Rating Curve= 0 ,0
Exp/Cntr(USF)=0,0
Exp/Cntr=0.3,0.1

Type RM Length L Ch R = 1 ,89174   ,249.4,254.6,257.1
XS GIS Cut Line= 3
2352449.88273287690468.2092154682352565.69998363690248.682582656
2352803.01983306689823.679666125
#Sta/Elev= 30
       0  2712.9      17 2708.13      26 2706.61    39.2    2701    54.3  2697.7
    82.1 2688.91   107.4 2682.94   131.2 2679.19   170.8 2668.87   193.4 2660.02
   202.4 2653.57   217.1 2652.32   234.9 2649.53   258.5 2647.73   270.2 2646.23
     298 2647.16   361.4 2649.83   368.1 2649.18   389.7 2649.59   403.4  2652.5
   423.1 2653.91   434.9 2654.12   446.6 2652.99   476.7  2652.5   545.4 2653.94
     576 2658.05   597.9 2659.15   614.1 2661.53   682.9 2668.16     735 2675.68
#Mann= 5 ,-1,0
       0      .1       0   258.5    .045       0     298      .1       0
   338.2     .12       0   458.2      .1       0
Bank Sta=258.5,298
XS Rating Curve= 0 ,0
Exp/Cntr=0.3,0.1

Type RM Length L Ch R = 1 ,88920   ,238,249,260.1
XS GIS Cut Line= 3
2352501.53382042690623.8590390682352754.82870808690389.753158052
2353119.41983425689971.432813284
#Sta/Elev= 30
       0 2712.24    26.4 2709.25    40.6 2706.13    54.7 2700.94    63.5 2699.17
    85.3 2689.21   131.1 2672.78   153.8 2666.23   173.6 2662.38   201.9 2660.29
   264.2 2652.19   281.4 2652.43   315.1 2649.04   343.4 2650.37   372.2 2649.93
   409.3 2646.27     420 2645.25   446.5 2646.12   494.2  2650.2   520.8 2650.98
   590.5 2649.36   621.3 2655.36   669.5 2658.08   706.5 2663.21   754.5 2672.61
   786.1 2680.99   840.1 2698.98   850.9 2700.45   876.6 2707.89   899.8  2712.1
#Mann= 5 ,-1,0
       0      .1       0   409.3    .045       0   446.5      .1       0
  774.91     .06       0  874.91      .1       0
Bank Sta=409.3,446.5
XS Rating Curve= 0 ,0
Exp/Cntr(USF)=0,0
Exp/Cntr=0.3,0.1