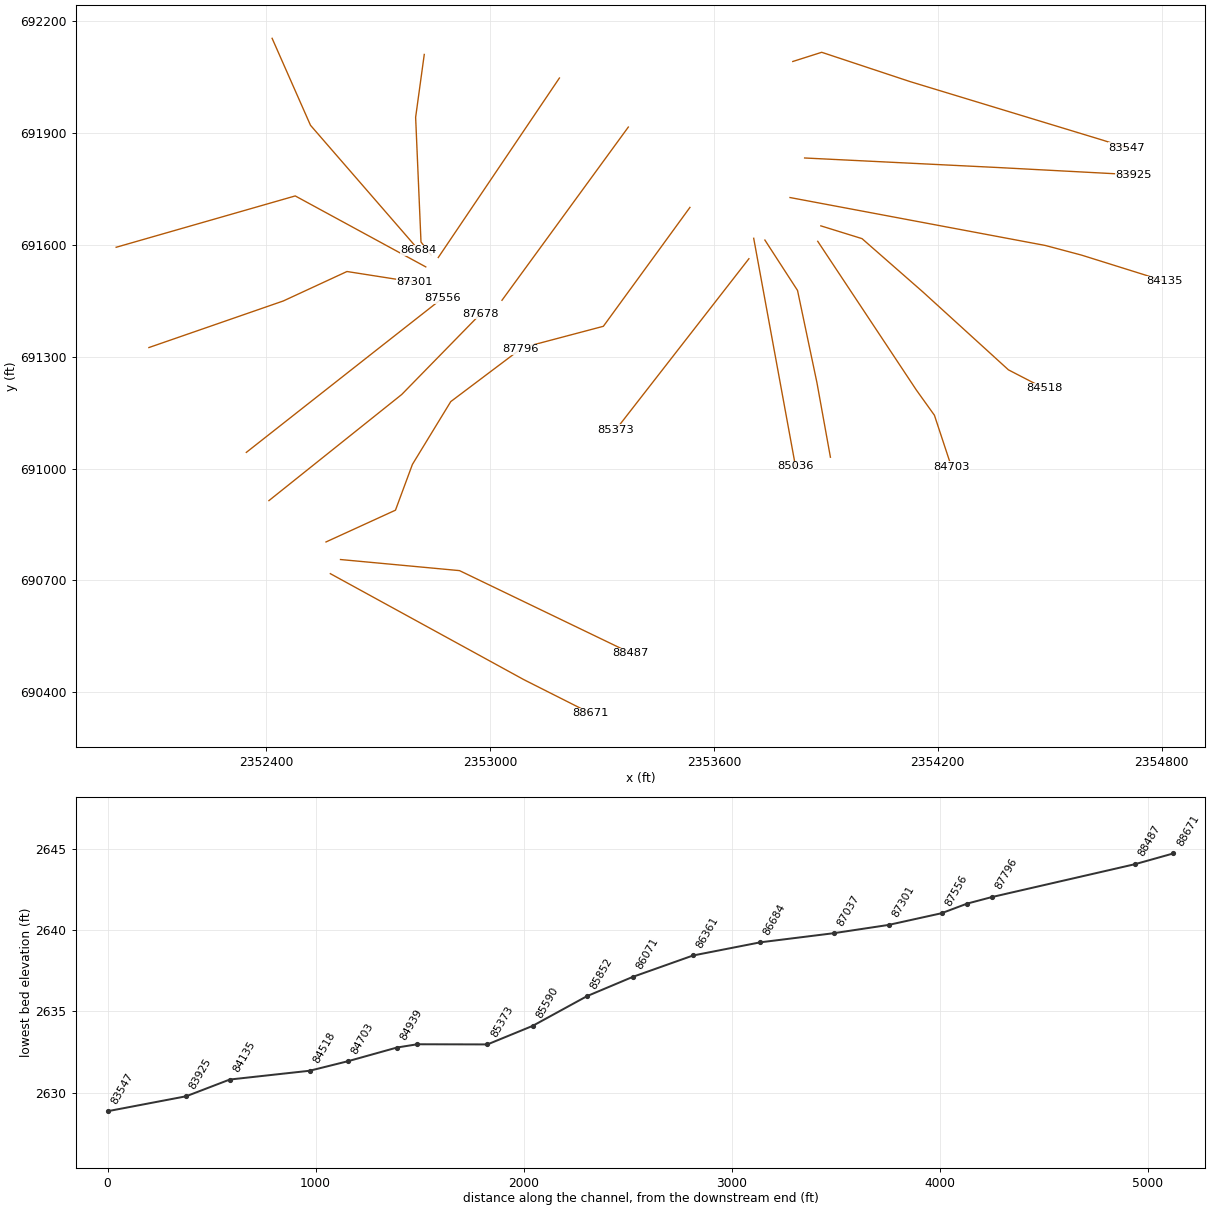
HEC-RAS study GLADYFK.prj: GLADYFK

--- GLADYFK.g01 (geometry) --- (continued)

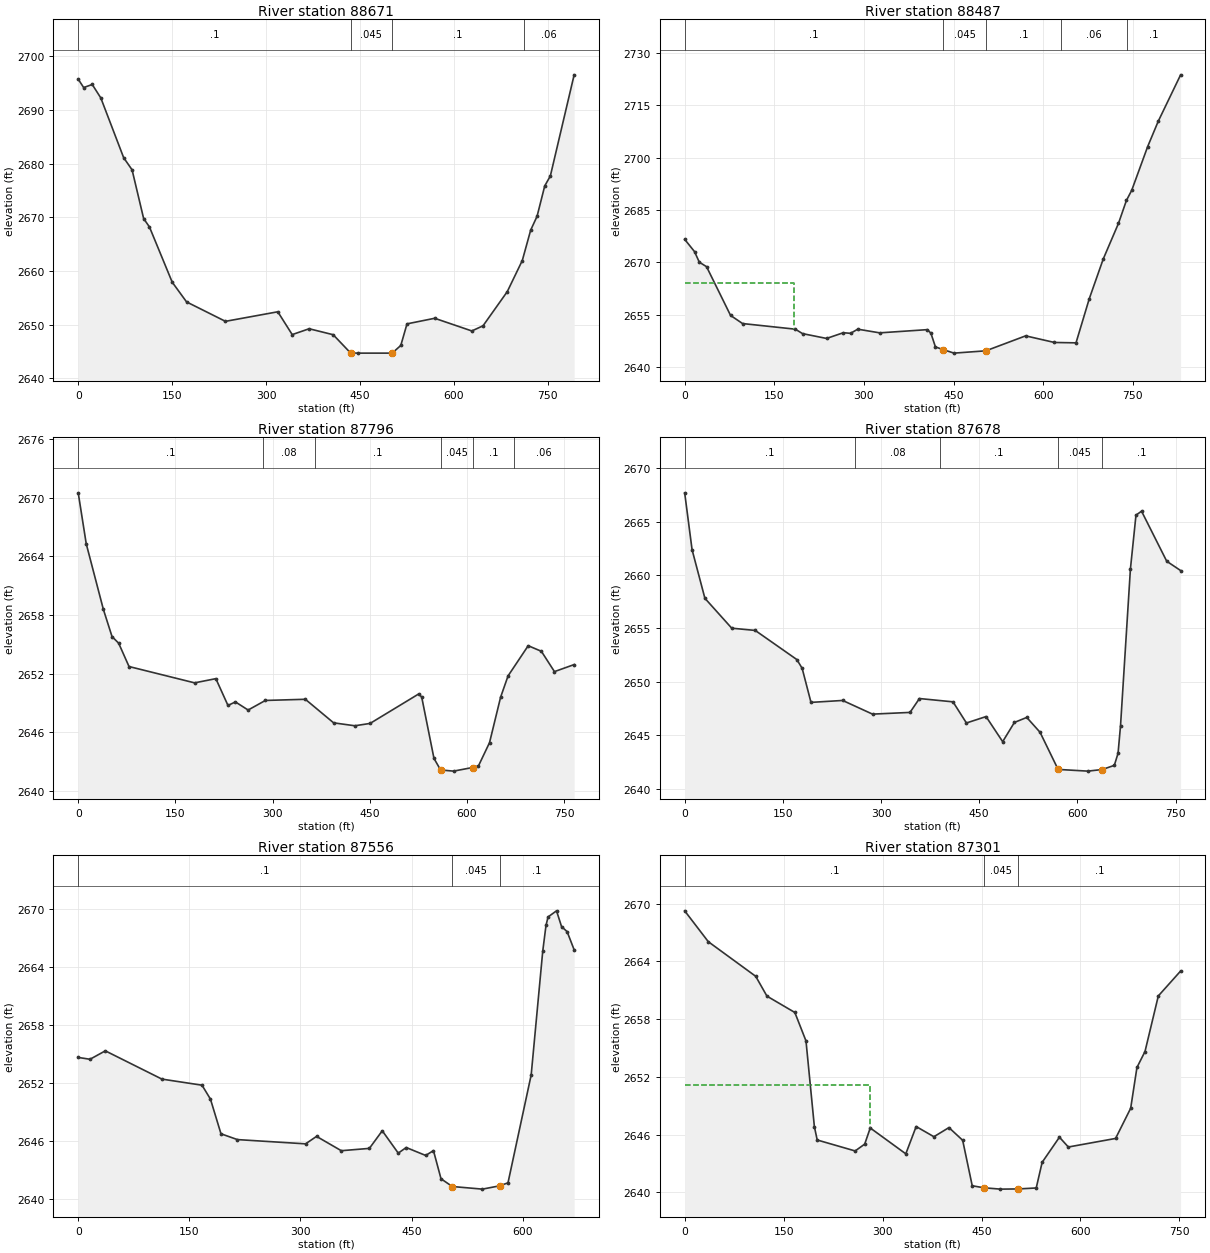
Type RM Length L Ch R = 1 ,88671   ,180.9,183.9,184
XS GIS Cut Line= 3
     2352572.507      690718.1952353091.06303984690433.962582734
2353270.10996016690343.582218594
#Sta/Elev= 30
       0 2695.74     8.7 2694.18    22.4 2694.75    36.1 2692.24    72.6 2681.11
      86 2678.86   104.5 2669.77   113.7 2668.23   150.1 2657.93     173 2654.26
   235.1 2650.64   318.7 2652.42   341.7 2648.17   368.8 2649.26   407.1 2648.15
   434.9 2644.75   446.6 2644.72   501.3 2644.72   515.1 2646.15     525 2650.17
   569.2 2651.21   628.5 2648.85   646.4 2649.81   685.1 2656.17   709.1 2661.97
   722.5 2667.63   732.7 2670.21   744.9 2675.85   753.9 2677.72   791.9 2696.55
#Mann= 4 ,-1,0
       0      .1       0   434.9    .045       0   501.3      .1       0
  711.34     .06       0
Bank Sta=434.9,501.3
XS Rating Curve= 0 ,0
Exp/Cntr=0.3,0.1

Type RM Length L Ch R = 1 ,88487   ,664.5,690.4,731.4
XS GIS Cut Line= 3
 2352599.7378427 690756.096084872352918.58303534690726.359227525
2353377.85227655690504.984845071
#Sta/Elev= 30
       0 2676.61    16.5 2673.09    24.5 2670.07    36.6 2668.79    76.8 2654.85
    96.9 2652.52   185.2 2650.91   197.3 2649.64   237.5 2648.26   265.6  2649.9
   277.6 2649.72   289.7 2650.91   326.4 2649.86   406.4 2650.78   412.2 2649.72
   419.7 2645.84     433 2645.05   450.8 2644.06   504.1 2644.72   570.7    2649
   618.9 2647.11     655    2647   677.2 2659.62   700.6 2670.99   726.1 2681.18
   739.4 2687.74   748.3 2690.65   774.9 2703.12   792.6 2710.37   830.1 2723.67
#Mann= 5 ,-1,0
       0      .1       0     433    .045       0   504.1      .1       0
  630.23     .06       0  740.23      .1       0
#XS Ineff= 2 , 0
          183.72 2663.99
Permanent Ineff=
       F       F
Bank Sta=433,504.1
XS Rating Curve= 0 ,0
Exp/Cntr(USF)=0,0
Exp/Cntr=0.3,0.1

Type RM Length L Ch R = 1 ,87796   ,111.9,117.8,122.3
XS GIS Cut Line= 5
2352560.89306585 690803.218788832352747.00644538690888.408499603
2352792.44313544691011.2558467852352895.09639815 691179.53988402
2353080.81127748691319.457693076
#Sta/Elev= 30
       0  2670.5    12.4 2665.28    38.8 2658.58    52.2 2655.79    62.4 2655.12
    78.4 2652.73   179.6 2651.06   212.4 2651.49   231.1 2648.75   242.6 2649.11
   262.2 2648.28   288.8 2649.26   350.5 2649.38   394.1 2646.97   426.9 2646.67
   450.4 2646.91   525.3 2649.92     530 2649.62     549 2643.33   559.2 2642.15
   579.2 2642.03   608.6  2642.4   617.6 2642.56   634.7 2644.94   651.8 2649.59
   663.3 2651.77   694.4 2654.86   714.7 2654.29   734.9 2652.21   765.3 2652.93
#Mann= 6 ,-1,0
       0      .1       0  284.68     .08       0  365.66      .1       0
   559.2    .045       0   608.6      .1       0  672.79     .06       0
Bank Sta=559.2,608.6
XS Rating Curve= 0 ,0
Exp/Cntr=0.3,0.1

Type RM Length L Ch R = 1 ,87678   ,125.4,122.6,118
XS GIS Cut Line= 3
2352408.00951256690914.1089561032352763.77747044691198.640227608
2352974.97605202691414.838320725
#Sta/Elev= 30
       0  2667.7    11.3 2662.37    30.9 2657.82    71.9 2655.02   107.8 2654.81
   171.4 2652.08   179.5 2651.26     193 2648.07   241.4 2648.25     287 2646.97
   344.3 2647.13   358.7 2648.43     410 2648.12   430.5 2646.14   460.5 2646.74
   485.9 2644.39   503.8 2646.19   522.7 2646.66     543 2645.27   570.6 2641.79
     616 2641.63     638 2641.78   656.5 2642.17   662.2  2643.3     666  2645.9
   681.1 2660.57   689.6 2665.61   698.1 2665.98   736.6 2661.29   757.8 2660.42
#Mann= 5 ,-1,0
       0      .1       0     260     .08       0     390      .1       0
   570.6    .045       0     638      .1       0
Bank Sta=570.6,638
XS Rating Curve= 0 ,0
Exp/Cntr=0.3,0.1

Type RM Length L Ch R = 1 ,87556   ,263.3,254.9,258
XS GIS Cut Line= 3
2352347.37861585691043.3646252912352700.02215323691320.939014595
2352873.51187274691457.198338425
#Sta/Elev= 30
       0 2654.65    15.9 2654.46    36.6 2655.33     113 2652.41   167.1 2651.78
   178.5 2650.34   192.7 2646.76   214.8 2646.16   306.9 2645.72   321.7 2646.49
   355.1 2645.01     393 2645.25   410.4 2647.07     432 2644.76   442.7 2645.34
     469 2644.52   479.5 2645.02   489.7 2642.11   504.9 2641.31   545.6 2641.04
   568.7 2641.38   580.1 2641.69   611.4 2652.84     627 2665.63   631.4 2668.29
   634.2 2669.17   645.6  2669.8   652.4 2668.17   659.9 2667.65   669.4 2665.77
#Mann= 3 ,-1,0
       0      .1       0   504.9    .045       0   568.7      .1       0
Bank Sta=504.9,568.7
XS Rating Curve= 0 ,0
Exp/Cntr(USF)=0,0
Exp/Cntr=0.3,0.1

Type RM Length L Ch R = 1 ,87301   ,268.7,264.3,259
XS GIS Cut Line= 4
2352086.38794095691324.4870678552352446.35393726691449.353321319
2352617.06951817691528.3702473392352797.54027513691500.080236789
#Sta/Elev= 30
       0 2669.26    35.8 2666.05   107.7 2662.45   124.7 2660.39     167 2658.69
   183.9 2655.73   196.6 2646.82   200.9 2645.43   258.4 2644.29   272.9    2645
   281.3 2646.68   335.2 2643.99   350.9 2646.83   377.8 2645.77   400.6 2646.72
   421.4  2645.4   435.9 2640.67   453.5 2640.46   478.7 2640.32   505.8 2640.34
   532.9 2640.44   541.9 2643.11   568.1 2645.72   581.6  2644.7   653.2 2645.59
   676.1 2648.73   685.6 2652.97   697.8 2654.63     718 2660.41   751.8    2663
#Mann= 3 ,-1,0
       0      .1       0   453.5    .045       0   505.8      .1       0
#XS Ineff= 2 , 0
          281.29 2651.17
Permanent Ineff=
       F       F
Bank Sta=453.5,505.8
XS Rating Curve= 0 ,0
Exp/Cntr(USF)=0,0
Exp/Cntr=0.3,0.1

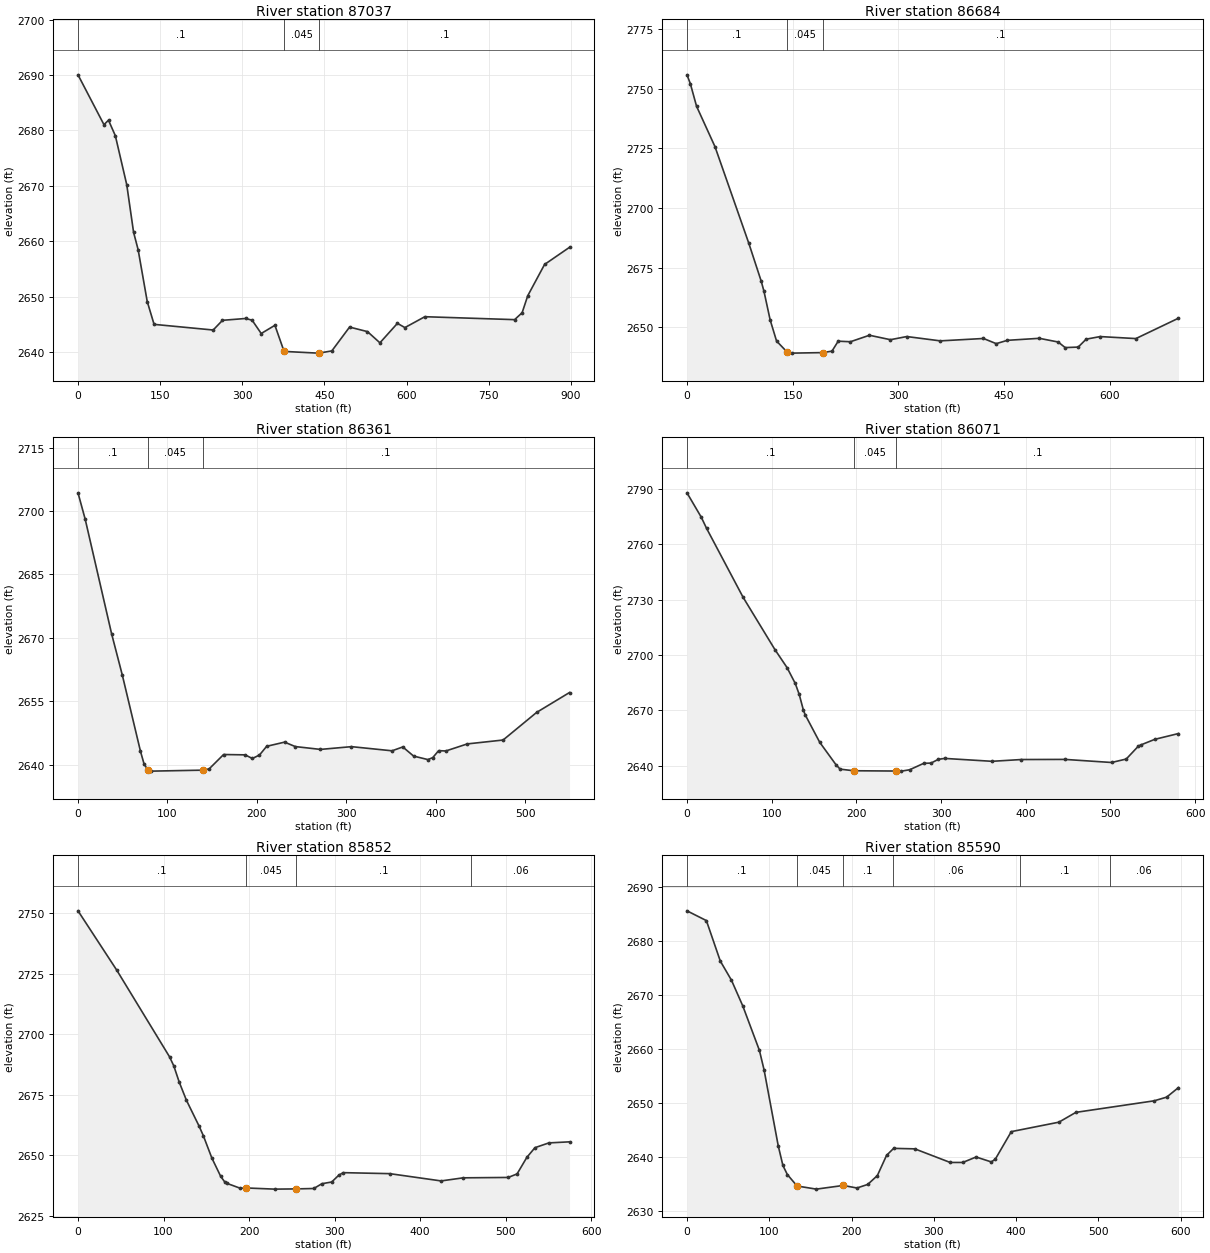
Type RM Length L Ch R = 1 ,87037   ,395.2,352.2,317.7
XS GIS Cut Line= 3
 2351998.6381344691593.3560516622352478.42377557691731.032763691
2352828.14342159691540.785276253
#Sta/Elev= 30
       0 2690.02    47.4 2681.03    55.7 2681.83    68.2 2679.03      89  2670.2
   101.5  2661.6   109.8 2658.47   126.4 2649.12   138.9    2645   246.8 2643.98
   263.8 2645.73     306 2646.06   317.9 2645.75   334.5 2643.35   359.5 2644.83
   376.2 2640.12   437.6 2639.81   440.2 2639.82   463.4 2640.21   495.8 2644.51
   528.5 2643.69   551.2 2641.67   583.1 2645.18   596.8 2644.42   633.2 2646.38
   797.1 2645.85   810.8  2647.1   821.1 2650.17   851.8 2655.81   897.3  2658.9
#Mann= 3 ,-1,0
       0      .1       0   376.2    .045       0   440.2      .1       0
Bank Sta=376.2,440.2
XS Rating Curve= 0 ,0
Exp/Cntr(USF)=0,0
Exp/Cntr=0.3,0.1

Type RM Length L Ch R = 1 ,86684   ,340,323.2,311.3
XS GIS Cut Line= 3
2352416.51226244692153.5946160442352519.30633721 691920.47233933
2352809.59348402691585.687188526
#Sta/Elev= 30
       0 2755.74     4.8 2752.03    13.6 2742.59    39.8 2725.65    87.9 2685.15
   105.4 2669.38   109.3 2665.17   118.1 2653.17   127.2 2644.31   142.7 2639.54
   149.1 2639.25   192.8 2639.47   205.9 2640.08   214.7 2644.25   232.1 2644.02
   259.1 2646.73   288.9 2644.87   312.1 2646.19   359.7 2644.38     421 2645.38
   439.1 2643.22     455 2644.61   500.3 2645.45   527.1  2643.9     537 2641.57
   555.5 2641.78   566.8 2645.09   586.7 2646.18   637.4 2645.34   697.9 2653.87
#Mann= 3 ,-1,0
       0      .1       0   142.7    .045       0   192.8      .1       0
Bank Sta=142.7,192.8
XS Rating Curve= 0 ,0
Exp/Cntr(USF)=0,0
Exp/Cntr=0.3,0.1

Type RM Length L Ch R = 1 ,86361   ,305.1,290.5,277.8
XS GIS Cut Line= 4
2352824.14447594692110.3596145382352801.01580911691941.850756252
2352815.41236403691607.4770642752352842.68104668 691572.37883201
#Sta/Elev= 30
       0 2704.29     8.1    2698    37.5 2670.99    49.6  2661.1    69.8 2643.15
    73.9 2640.08    77.9  2638.8    81.9 2638.44   139.5 2638.67   146.5 2638.96
   162.7 2642.37   186.8 2642.29   194.8 2641.43   202.8 2642.25   210.8 2644.31
   230.8  2645.3   242.8 2644.25   270.9 2643.58   305.6 2644.23   350.9 2643.25
   362.9 2644.16     375    2642     391 2641.17   396.4 2641.64     403 2643.28
     411 2643.21     435 2644.88     475  2645.8   512.5 2652.34   549.2 2657.04
#Mann= 3 ,-1,0
       0      .1       0    77.9    .045       0   139.5      .1       0
Bank Sta=77.9,139.5
XS Rating Curve= 0 ,0
Exp/Cntr(USF)=0,0
Exp/Cntr=0.3,0.1

Type RM Length L Ch R = 1 ,86071   ,219.7,219,217.8
XS GIS Cut Line= 2
2353186.25633912692047.1793236992352861.71650761691565.965090767
#Sta/Elev= 30
       0 2787.87    16.9 2774.65    23.1 2768.67    66.3 2731.26   103.9 2702.92
   118.2 2693.18   127.9 2684.59   132.5 2678.73   137.5 2670.13   139.6 2667.63
   156.8 2652.71   176.1  2640.5   180.9 2638.19   196.9 2637.32     247 2637.17
   253.3 2637.12   262.9 2637.85   279.6 2641.35   288.2 2641.48   296.8  2643.5
   304.2 2644.01   360.2 2642.44   394.8  2643.4   446.3 2643.47   501.4  2641.8
   518.7 2643.67   533.1 2650.69     536 2651.32   552.4 2654.34   580.4 2657.48
#Mann= 3 ,-1,0
       0      .1       0   196.9    .045       0     247      .1       0
Bank Sta=196.9,247
XS Rating Curve= 0 ,0
Exp/Cntr(USF)=0,0
Exp/Cntr=0.3,0.1

Type RM Length L Ch R = 1 ,85852   ,260.8,261.4,260.8
XS GIS Cut Line= 2
2353370.90831223691915.6847367932353032.37969487 691451.25704687
#Sta/Elev= 30
       0 2750.99    45.4 2726.42     107 2690.66     112 2686.91   118.3 2680.24
   126.8 2672.67   141.7 2661.91   146.6 2657.99   156.5 2648.81   166.9 2641.19
   171.4    2639   174.4 2638.29   189.8 2636.29   196.1 2636.43   229.9 2635.94
   254.6 2636.03   275.7  2636.2   285.2 2638.18   296.6 2638.88     305 2641.72
   310.1 2642.75   364.5 2642.34   424.6 2639.33   450.4 2640.61     503 2640.77
   513.4 2642.23   524.8 2649.06   534.3 2653.08   550.6 2655.05   574.7 2655.49
#Mann= 4 ,-1,0
       0      .1       0   196.1    .045       0   254.6      .1       0
     460     .06       0
Bank Sta=196.1,254.6
XS Rating Curve= 0 ,0
Exp/Cntr(USF)=0,0
Exp/Cntr=0.3,0.1

Type RM Length L Ch R = 1 ,85590   ,224.4,217.2,216.1
XS GIS Cut Line= 3
2353535.97598515691700.2574348412353304.02660863691381.480728702
2353107.66797413691329.500882193
#Sta/Elev= 30
       0 2685.66    23.6 2683.85    40.5 2676.36    54.1  2672.8    67.9 2668.02
      88 2659.83    93.7 2656.21   110.9 2642.15   116.6 2638.49     122 2636.81
   133.8 2634.69   157.2 2634.11     190 2634.79   206.6 2634.32   219.7 2634.98
   231.4 2636.62   242.6 2640.37   251.2 2641.66   276.9 2641.57   319.9 2639.05
   335.2 2639.05   351.4 2640.06   369.9 2639.15   374.8 2639.67   394.2 2644.76
     452 2646.51   472.7 2648.33   567.9 2650.47     583 2651.15   597.4 2652.92
#Mann= 6 ,-1,0
       0      .1       0   133.8    .045       0     190      .1       0
     250     .06       0  404.23      .1       0  514.23     .06       0
Bank Sta=133.8,190
XS Rating Curve= 0 ,0
Exp/Cntr(USF)=0,0
Exp/Cntr=0.3,0.1

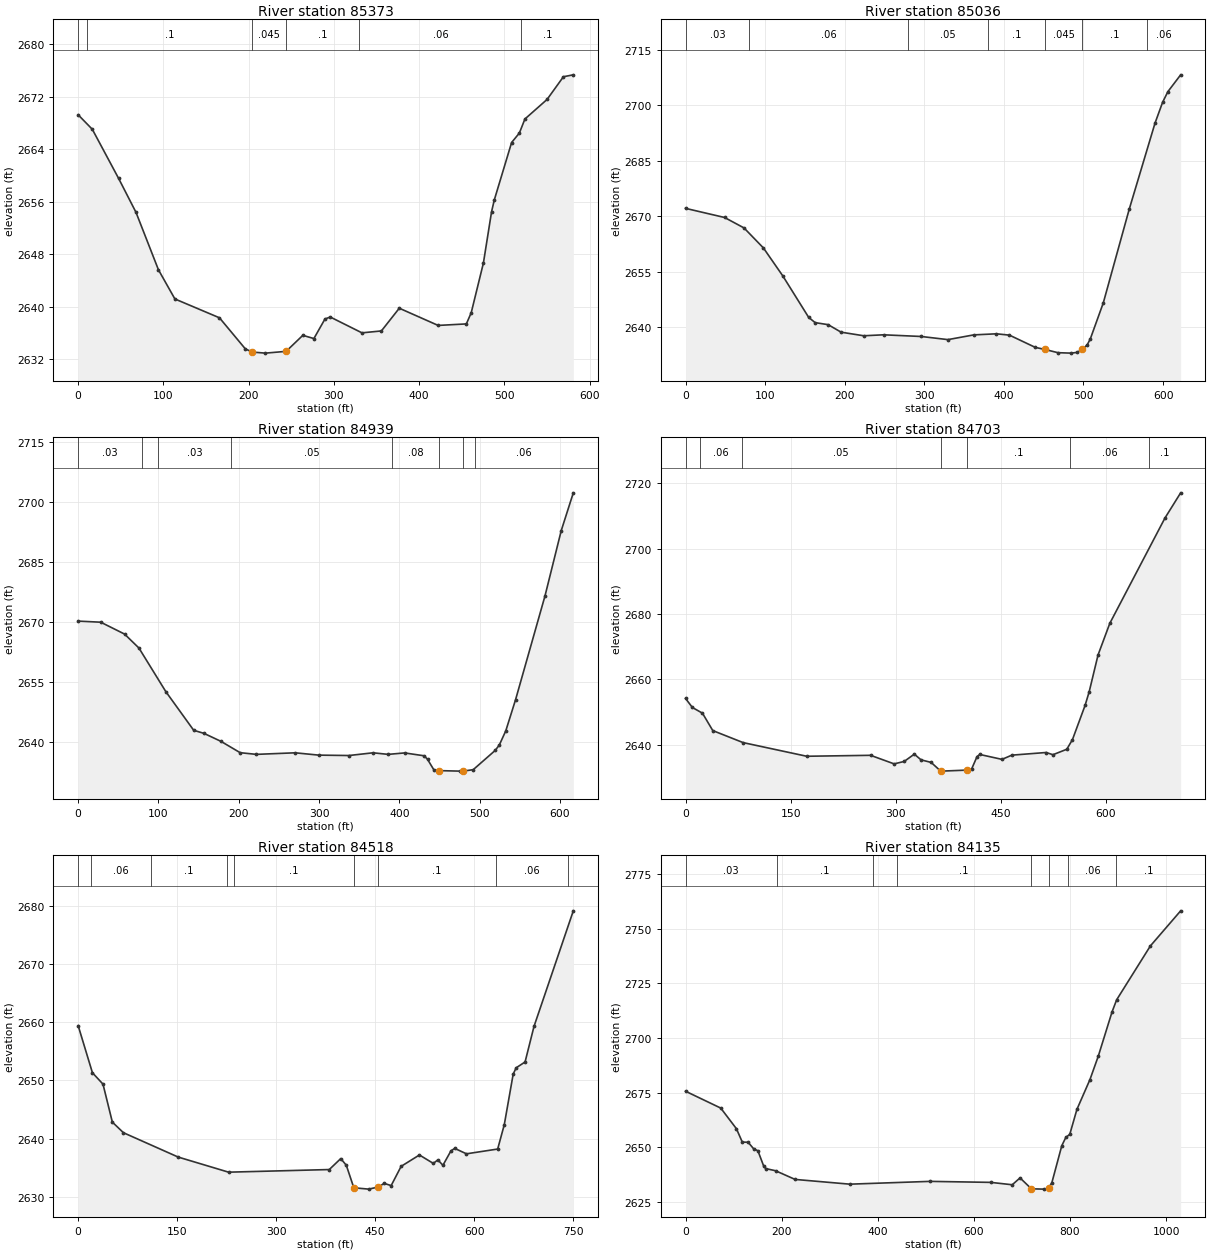
Type RM Length L Ch R = 1 ,85373   ,334.9,336.8,372
XS GIS Cut Line= 2
2353693.98163456 691562.637708732353337.28544296691104.008846669
#Sta/Elev= 30
       0 2669.27    16.6 2667.06    47.5 2659.57    67.9  2654.4    94.2 2645.66
   113.5 2641.22   165.8 2638.35   196.2 2633.61   204.5 2633.13   219.7 2632.97
     244 2633.24   263.6 2635.68   276.6 2635.19   289.6 2638.17   295.8 2638.47
     333 2636.06   355.8 2636.35   376.8 2639.81   422.4 2637.19   455.5 2637.42
   461.2 2639.12   475.5 2646.69   485.1 2654.52   488.3 2656.31   508.6 2665.05
   517.7 2666.49   524.2 2668.63   550.2 2671.61   569.4 2675.07     581 2675.36
#Mann= 6 ,-1,0
       0     .03       0      10      .1       0   204.5    .045       0
     244      .1       0     330     .06       0     520      .1       0
Bank Sta=204.5,244
XS Rating Curve= 0 ,0
Exp/Cntr(USF)=0,0
Exp/Cntr=0.3,0.1

Type RM Length L Ch R = 1 ,85036   ,97.7,97.7,99.8
XS GIS Cut Line= 2
2353706.83718873691617.4434442722353818.91435753691005.562684886
#Sta/Elev= 30
       0  2672.1    49.1 2669.63    73.5 2666.81    97.9 2661.39   122.3 2653.82
   154.8 2642.62   162.9 2641.22   179.2 2640.67   195.5 2638.64   223.9 2637.67
   248.8 2637.93     296 2637.48   329.7 2636.63   362.2 2637.91   390.7  2638.2
     407 2637.84   439.5 2634.53   451.6 2633.97   467.9  2633.1   484.2 2632.98
   492.3 2633.18   498.72634.094   504.5 2635.14   508.6 2636.83   524.9 2646.56
   557.4 2671.81   589.9 2695.14   599.4 2700.75     606 2703.62   622.1 2708.18
#Mann= 7 ,-1,0
       0     .03       0      80     .06       0     280     .05       0
     380      .1       0   451.6    .045       0   498.7      .1       0
     580     .06       0
Bank Sta=451.6,498.7
XS Rating Curve= 0 ,0
Exp/Cntr(USF)=0,0
Exp/Cntr=0.3,0.1

Type RM Length L Ch R = 1 ,84939   ,227.7,235.2,240.6
XS GIS Cut Line= 4
2353736.78592468691612.7325437612353824.26679962691477.621117971
 2353876.3734706691229.7755744132353912.37840374691030.427099681
#Sta/Elev= 30
       0 2670.28    28.1 2670.01    57.8 2667.04    75.7 2663.55   109.1 2652.68
   143.9 2642.99   156.7 2642.22   177.8 2640.23   201.8 2637.39     222 2636.97
   270.3 2637.36   299.7 2636.78   337.2 2636.68   367.3 2637.36   386.2 2636.97
   406.7 2637.33   431.1 2636.61   435.2 2635.73   443.3 2633.03     449 2632.91
   475.8 2632.78   479.7 2632.79   492.1 2633.14   519.4 2637.94   524.6  2639.3
   532.7 2642.86   544.9 2650.66   581.5 2676.56   601.8 2692.93   616.8 2702.35
#Mann= 8 ,-1,0
       0     .03       0      80     .06       0     100     .03       0
  190.96     .05       0  390.96     .08       0     449    .045       0
   479.7      .1       0  494.22     .06       0
Bank Sta=449,479.7
XS Rating Curve= 0 ,0
Exp/Cntr(USF)=0,0
Exp/Cntr=0.3,0.1

Type RM Length L Ch R = 1 ,84703   ,181.3,185.1,190.6
XS GIS Cut Line= 4
2353878.38459529691609.3493163372354142.65424634691210.561905729
 2354191.0647003691142.9436402782354236.53258442691005.177648353
#Sta/Elev= 30
       0 2654.19     9.8 2651.42    24.2 2649.67    38.9 2644.35    82.2 2640.67
     173 2636.49   264.1 2636.78   297.7 2634.16   312.1 2634.91   326.5 2637.14
   336.1 2635.39   350.5 2634.61   364.1 2631.96   365.1 2631.94   401.5 2632.25
   408.3 2632.59     416 2636.38   419.9 2637.04   451.6 2635.54   465.7 2636.83
   514.5 2637.64   524.4 2636.97   544.1 2638.63   552.2 2641.59   570.2 2652.05
   576.1 2656.27   588.7 2667.49   605.5 2677.18   684.2 2709.41   706.6 2717.12
#Mann= 7 ,-1,0
       0     .03       0      20     .06       0      80     .05       0
   364.1    .045       0   401.5      .1       0   548.4     .06       0
  661.56      .1       0
Bank Sta=364.1,401.5
XS Rating Curve= 0 ,0
Exp/Cntr=0.3,0.1

Type RM Length L Ch R = 1 ,84518   ,379.3,383.8,394.6
XS GIS Cut Line= 5
 2353886.6975407691650.7849642372353997.05104348691616.535763593
2354160.26380855691473.4626547792354389.43630316691264.627941531
2354485.07098453691215.236306507
#Sta/Elev= 30
       0  2659.4    21.6 2651.32    37.6 2649.37    51.8 2642.85    68.6 2641.03
   151.6 2636.85   227.9 2634.26   380.5 2634.71   397.9 2636.59   406.3 2635.45
   417.7 2631.58   440.3 2631.35   454.5 2631.71   463.7 2632.33   474.3 2631.96
   489.4 2635.26   517.1 2637.21   538.1 2635.77   545.1 2636.37   552.7 2635.44
   564.9 2637.92   570.6 2638.34   588.4 2637.41   635.7 2638.23   645.7 2642.41
   659.2 2651.09   663.7 2652.17   677.2 2653.17   690.7 2659.26   750.3 2679.11
#Mann= 9 ,-1,0
       0     .03       0      20     .06       0     110      .1       0
  225.55     .05       0  235.55      .1       0   417.7    .045       0
   454.5      .1       0  632.59     .06       0  742.64      .1       0
Bank Sta=417.7,454.5
XS Rating Curve= 0 ,0
Exp/Cntr(USF)=0,0
Exp/Cntr=0.3,0.1

Type RM Length L Ch R = 1 ,84135   ,207.1,209.7,214.9
XS GIS Cut Line= 4
2353804.12643547691726.725485545 2354488.4817648691598.127139995
2354585.36640644691572.2997959652354808.29670322691502.490573382
#Sta/Elev= 30
       0 2675.63    73.3 2667.91   105.9 2658.47   118.1 2652.36   130.3 2652.26
   141.8 2649.26   150.6 2648.36   162.8 2641.28   166.9 2640.22   187.3 2639.23
     228 2635.25   341.9 2633.08   508.8 2634.36   635.2  2633.9   679.8 2632.81
     696 2635.95   719.7 2630.95   745.4 2630.81   755.7 2631.19   762.3 2633.82
   782.9  2650.7   791.2 2654.45   799.5  2655.9   814.4 2667.34   841.5 2680.97
   858.8 2691.67   887.5 2711.98   897.1 2717.51   967.2 2742.14  1030.2 2758.21
#Mann= 8 ,-1,0
       0     .03       0     190      .1       0     390     .06       0
     440      .1       0   719.7    .045       0   755.7      .1       0
  796.33     .06       0   896.6      .1       0
Bank Sta=719.7,755.7
XS Rating Curve= 0 ,0
Exp/Cntr=0.3,0.1

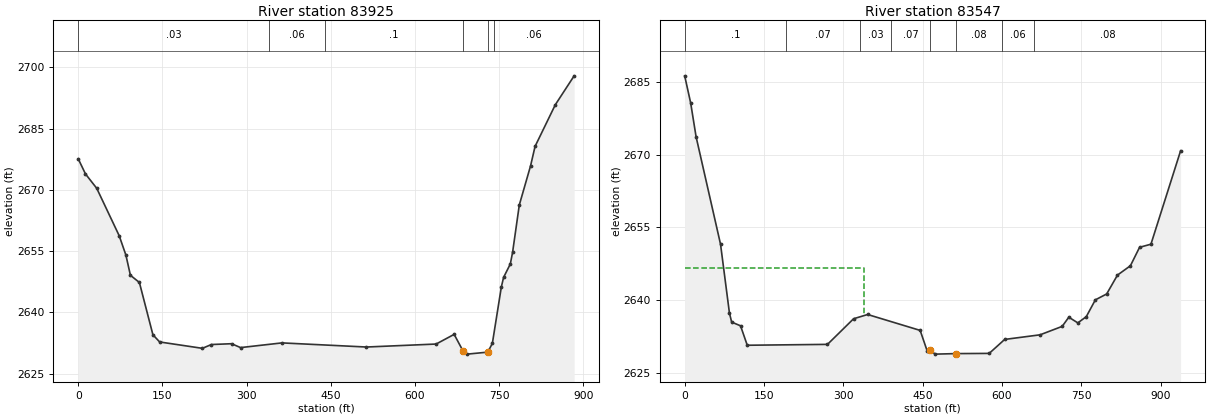
Type RM Length L Ch R = 1 ,83925   ,390,377.9,379
XS GIS Cut Line= 3
2353843.26179873691832.7795104742354364.22287291691807.042810712
2354725.67868072691787.818474225
#Sta/Elev= 30
       0 2677.62    12.9 2673.92      33 2670.39      73 2658.78      85 2654.02
      93 2649.09     109 2647.33   133.1 2634.52   145.1 2632.76   221.2  2631.2
   237.2 2632.13   273.2 2632.33   289.3 2631.38     363 2632.53   513.5 2631.52
   637.7 2632.25   669.8 2634.62   685.8  2630.5     693 2629.78   729.8 2630.27
   737.9 2632.43   753.9 2646.24   757.9 2648.58   769.9 2651.87   773.9  2654.7
   785.9 2666.32   805.9 2675.87     814 2680.67     850 2690.85   883.6 2697.94
#Mann= 6 ,-1,0
       0     .03       0     340     .06       0     440      .1       0
   685.8    .045       0   729.8      .1       0   741.6     .06       0
Bank Sta=685.8,729.8
XS Rating Curve= 0 ,0
Exp/Cntr(USF)=0,0
Exp/Cntr=0.3,0.1

Type RM Length L Ch R = 1 ,83547   ,82.3,84.8,76.3
XS GIS Cut Line= 5
2353811.59027864692091.5241221752353889.03909908692116.159448156
2354125.66868117692037.6309886652354641.42806916691880.742867143
2354706.19402611691860.163364185
#Sta/Elev= 30
       0 2686.23    11.3 2680.65    21.6 2673.65    67.8 2651.51    84.6 2637.34
    88.8 2635.46   105.6  2634.7   118.3 2630.69     270 2630.87   319.3 2636.15
   345.9 2637.03   445.2 2633.75   458.6 2629.47   463.5 2629.62     474 2628.86
   512.32628.967   575.7 2629.01     605 2631.89   671.9 2632.84   713.7 2634.58
   726.2 2636.47   743.3  2635.3   759.3 2636.59   776.4 2640.05   797.8 2641.26
   818.2 2645.15   842.7 2647.08     860 2650.88   881.5 2651.52   937.6 2670.79
#Mann= 8 ,-1,0
       0      .1       0  191.27     .07       0  330.59     .03       0
  390.59     .07       0   463.5    .045       0   512.3     .08       0
  600.59     .06       0  660.59     .08       0
#XS Ineff= 2 , 0
          339.74 2646.56
Permanent Ineff=
       F       F
Bank Sta=463.5,512.3
XS Rating Curve= 0 ,0
Exp/Cntr(USF)=0,0
Exp/Cntr=0.3,0.1