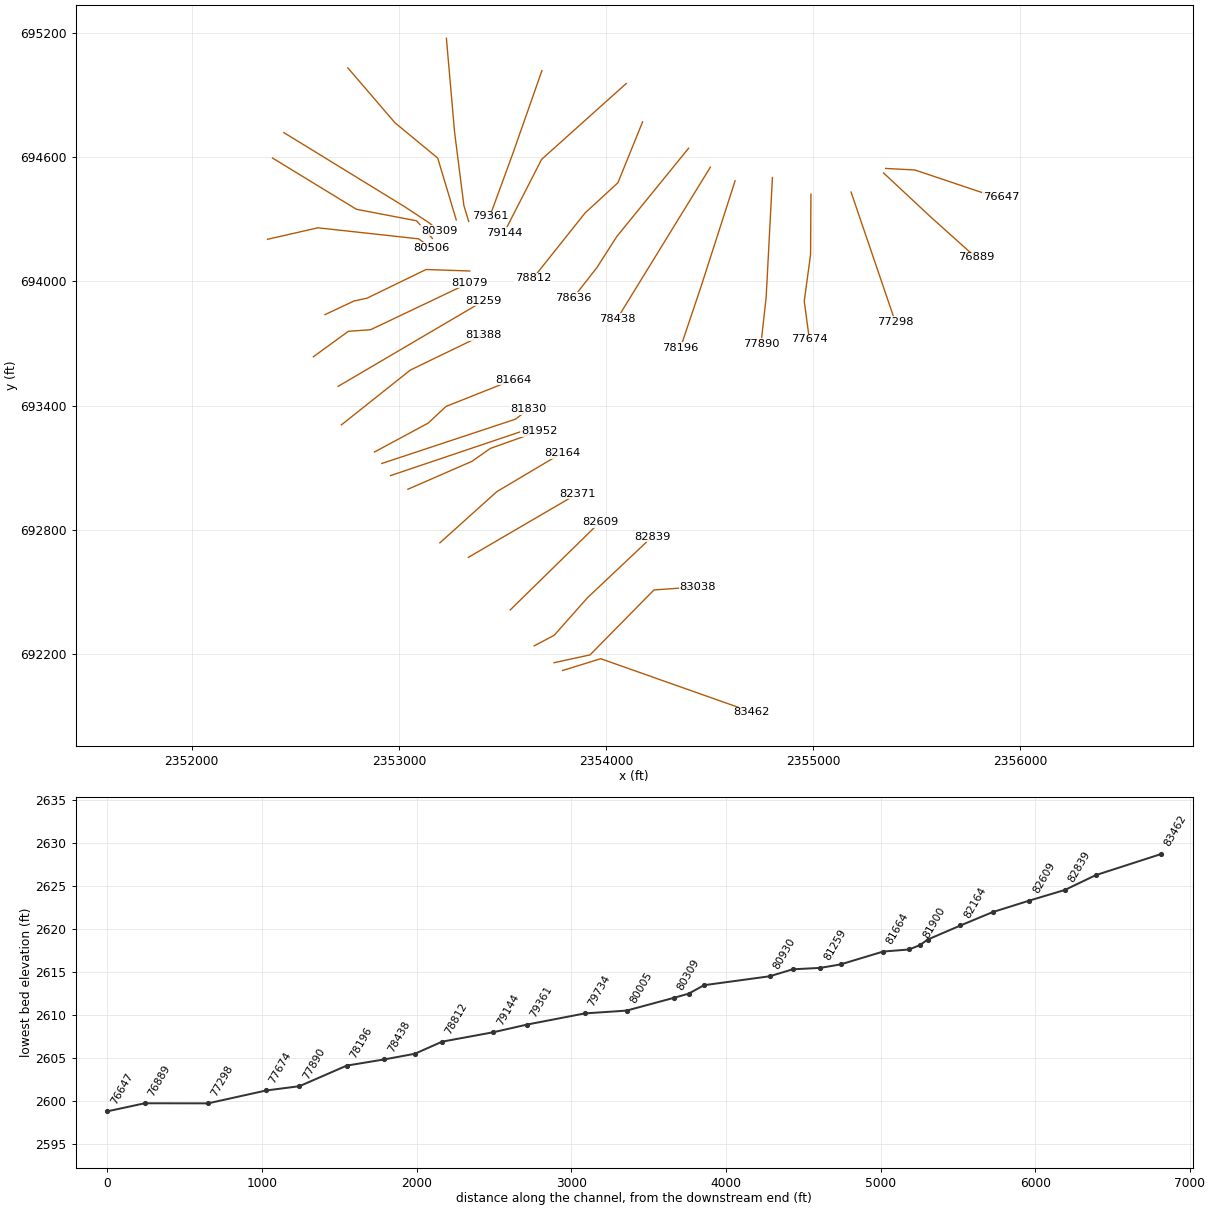
HEC-RAS study GLADYFK.prj: GLADYFK

--- GLADYFK.g01 (geometry) --- (continued)

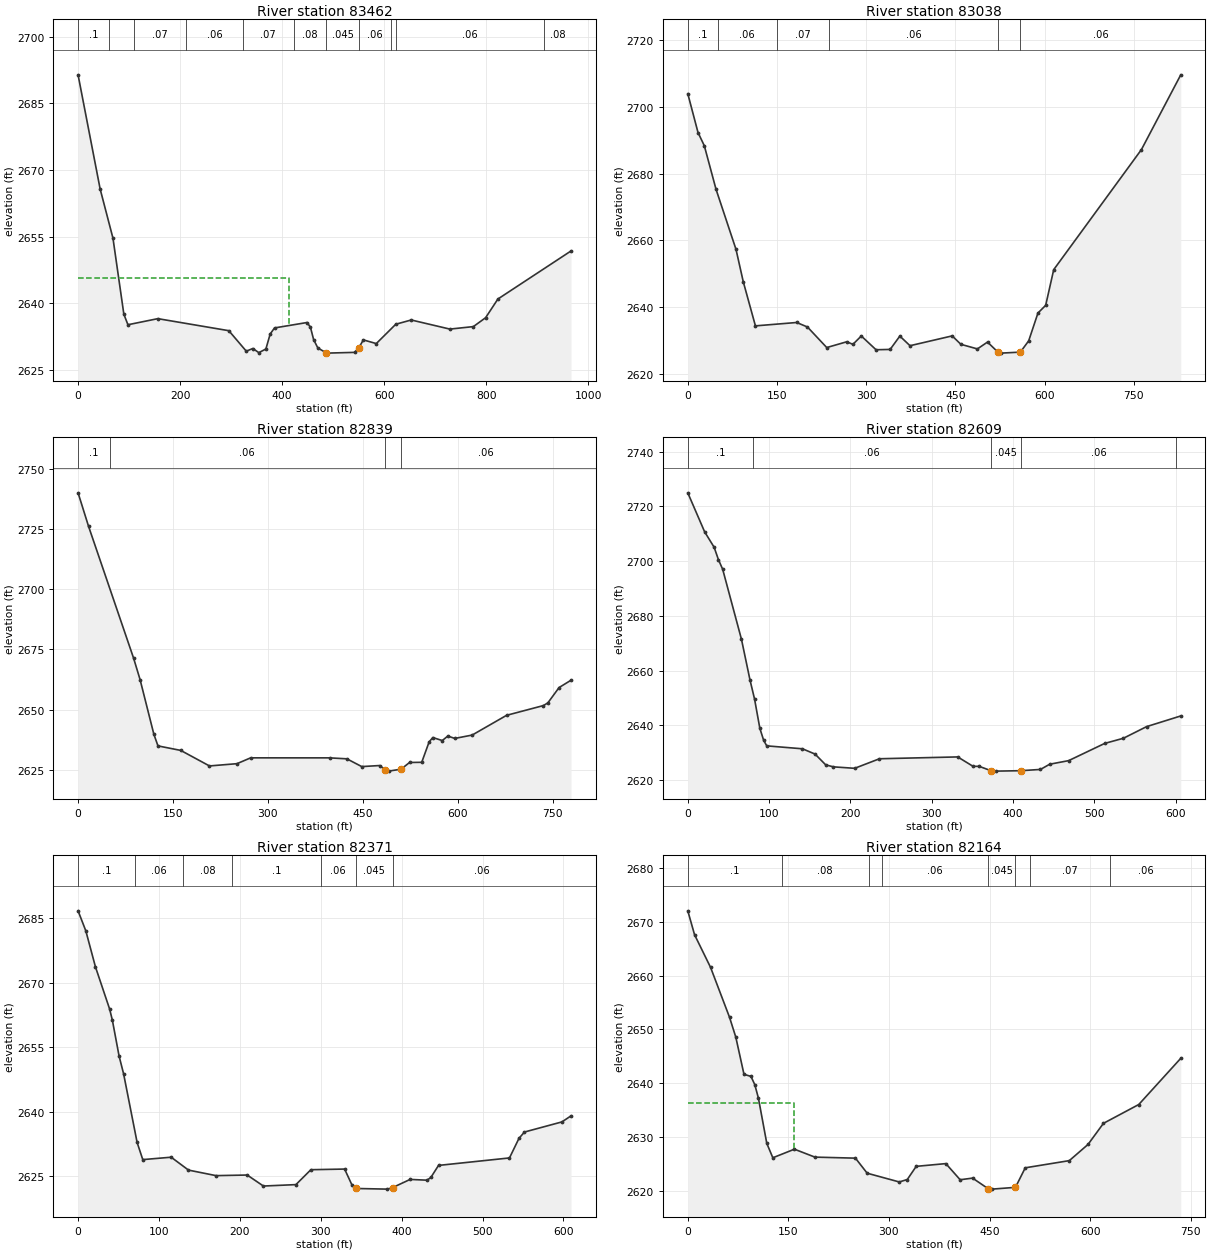
Type RM Length L Ch R = 1 ,83462   ,393.8,424.2,451.9
XS GIS Cut Line= 3
2353790.85535449692122.2641422822353974.48762447692179.115465705
2354703.94014854691921.450627272
#Sta/Elev= 30
       0 2691.39    43.3 2665.67    68.4 2654.61    89.7 2637.52    97.7 2635.14
   156.3 2636.51   295.4  2633.8   329.6 2629.19   342.4 2629.79   354.2 2628.86
     368 2629.68   376.4 2633.05   384.9 2634.42   448.6 2635.64   455.3 2634.59
   461.5  2631.8   469.8 2629.91   486.3 2628.81   486.7 2628.75   541.9 2628.92
   550.4 2629.99   558.9 2631.73   584.3  2630.9   622.5 2635.25   652.8 2636.21
   728.5 2634.16   774.5 2634.72   798.5 2636.72   822.6 2640.93   965.9 2651.75
#Mann= 11 ,-1,0
       0      .1       0      60     .06       0     110     .07       0
  212.23     .06       0  322.23     .07       0  422.23     .08       0
   486.3    .045       0   550.4     .06       0  612.23     .08       0
  622.23     .06       0  912.23     .08       0
#XS Ineff= 2 , 0
          413.23 2645.73
Permanent Ineff=
       F       F
Bank Sta=486.3,550.4
XS Rating Curve= 0 ,0
Exp/Cntr(USF)=0,0
Exp/Cntr=0.3,0.1

Type RM Length L Ch R = 1 ,83038   ,198.9,198.9,200
XS GIS Cut Line= 4
2353749.04185176  692159.83829662353922.96241795692197.517325176
 2354231.4578708692510.9596409372354441.98669198692526.063393591
#Sta/Elev= 30
       0 2703.95    17.2 2692.32    27.8 2688.36    47.5 2675.32    81.1 2657.32
    93.2  2647.7   113.7 2634.44   183.1 2635.45   201.2  2634.1   233.6 2627.95
   267.3 2629.68   277.6 2628.91   291.7 2631.41   316.5 2627.29   340.2 2627.39
   356.5 2631.38   373.6  2628.5   444.5 2631.44   459.1 2628.92   486.9 2627.54
   503.9 2629.59   520.8 2626.69   526.5 2626.28   559.1 2626.58   573.1 2629.95
   588.7 2638.28   601.7  2640.6   615.2 2651.27   762.7 2687.23   828.8  2709.6
#Mann= 6 ,-1,0
       0      .1       0      50     .06       0     150     .07       0
  237.96     .06       0   520.8    .045       0   559.1     .06       0
Bank Sta=520.8,559.1
XS Rating Curve= 0 ,0
Exp/Cntr=0.3,0.1

Type RM Length L Ch R = 1 ,82839   ,231.8,229.7,229.2
XS GIS Cut Line= 4
2353653.49398547692241.3365267742353749.70227021 692292.04094764
2353909.66702078692472.5356963382354221.89672075 692767.13952615
#Sta/Elev= 30
       0 2739.95    16.6 2726.04    87.7 2671.45      98 2662.52   119.8 2639.86
   126.3 2635.02   162.3 2633.15   207.7 2626.71   251.2 2627.65   272.8 2630.07
   397.5 2630.06   424.9 2629.66   448.4 2626.44   476.7 2626.88   484.9 2625.22
   490.8 2624.56   510.6 2625.37   523.9 2628.14   543.2 2628.22   554.9 2636.69
   560.7 2638.48   575.7 2637.24   584.4  2639.1   595.5 2638.12   622.9 2639.51
   677.3  2647.7   735.6 2651.75   742.6 2652.87   760.3 2659.22   779.2 2662.26
#Mann= 4 ,-1,0
       0      .1       0      50     .06       0   484.9    .045       0
   510.6     .06       0
Bank Sta=484.9,510.6
XS Rating Curve= 0 ,0
Exp/Cntr(USF)=0,0
Exp/Cntr=0.3,0.1

Type RM Length L Ch R = 1 ,82609   ,242.8,238.5,231.8
XS GIS Cut Line= 2
2353537.52010725692414.5349452592353970.72837798692838.607243941
#Sta/Elev= 30
       0 2724.99    20.7 2710.75    32.4  2705.1    37.7 2700.56    42.9 2697.07
      66 2671.49    76.5 2656.61    82.1 2649.65    88.6 2638.97    93.3 2634.57
    97.1 2632.55     141 2631.48   156.5 2629.55   169.6 2625.61   179.1 2624.88
   205.2 2624.35   235.7 2627.84   331.9 2628.51   350.8 2625.07   358.3 2625.07
   373.2 2623.44   378.7 2623.32   409.8 2623.48   433.7 2623.94     445 2625.84
   468.3 2627.15   512.7 2633.45   535.6 2635.32   564.2 2639.58   606.2 2643.48
#Mann= 5 ,-1,0
       0      .1       0      80     .06       0   373.2    .045       0
   409.8     .06       0     600     .05       0
Bank Sta=373.2,409.8
XS Rating Curve= 0 ,0
Exp/Cntr=0.3,0.1

Type RM Length L Ch R = 1 ,82371   ,205.8,207,205.9
XS GIS Cut Line= 2
2353335.58470054692668.3634358772353861.84282388692975.557172946
#Sta/Elev= 30
       0 2686.75     9.6 2682.08    21.5  2673.7      39 2663.89    42.4  2661.3
    50.7 2652.95    56.3  2648.8      73 2632.83      80 2628.84   115.1  2629.4
   136.5  2626.4   170.6 2625.11   209.1 2625.25   229.1 2622.69   269.3 2623.02
   287.8 2626.49   329.5 2626.64   338.8 2622.84   343.4 2622.12   382.5 2621.97
   388.8 2622.33   410.5 2624.23   431.4 2624.05   436.1 2624.69   445.6 2627.49
   533.3 2629.23     545 2633.78   551.8 2635.26   598.2 2637.62   609.4 2639.03
#Mann= 7 ,-1,0
       0      .1       0      70     .06       0     130     .08       0
     190      .1       0     300     .06       0   343.4    .045       0
   388.8     .06       0
Bank Sta=343.4,388.8
XS Rating Curve= 0 ,0
Exp/Cntr(USF)=0,0
Exp/Cntr=0.3,0.1

Type RM Length L Ch R = 1 ,82164   ,206.9,211.4,208.5
XS GIS Cut Line= 3
     2353197.864       692738.442353472.79070485692985.415370972
2353787.07024276693172.041704847
#Sta/Elev= 30
       0 2671.99    10.1 2667.56      34  2661.5    62.3 2652.24    71.6 2648.58
    83.8 2641.69    94.2 2641.31    99.9 2639.78   105.3 2637.29   117.8  2628.9
   126.8 2626.23     159 2627.82   189.6 2626.35     250 2626.16   267.5 2623.37
   315.3 2621.75   327.3  2622.2   340.6 2624.64   384.8 2625.15   406.1 2622.16
   424.7 2622.46   447.9  2620.5   453.6 2620.42   488.6 2620.75   503.2 2624.37
   568.9  2625.7   596.8  2628.7   619.8 2632.61   672.5  2636.1   735.1 2644.66
#Mann= 8 ,-1,0
       0      .1       0     140     .08       0     270     .07       0
     290     .06       0   447.9    .045       0   488.6     .06       0
  509.57     .07       0  629.57     .06       0
#XS Ineff= 2 , 0
          158.28 2636.43
Permanent Ineff=
       F       F
Bank Sta=447.9,488.6
XS Rating Curve= 0 ,0
Exp/Cntr=0.3,0.1

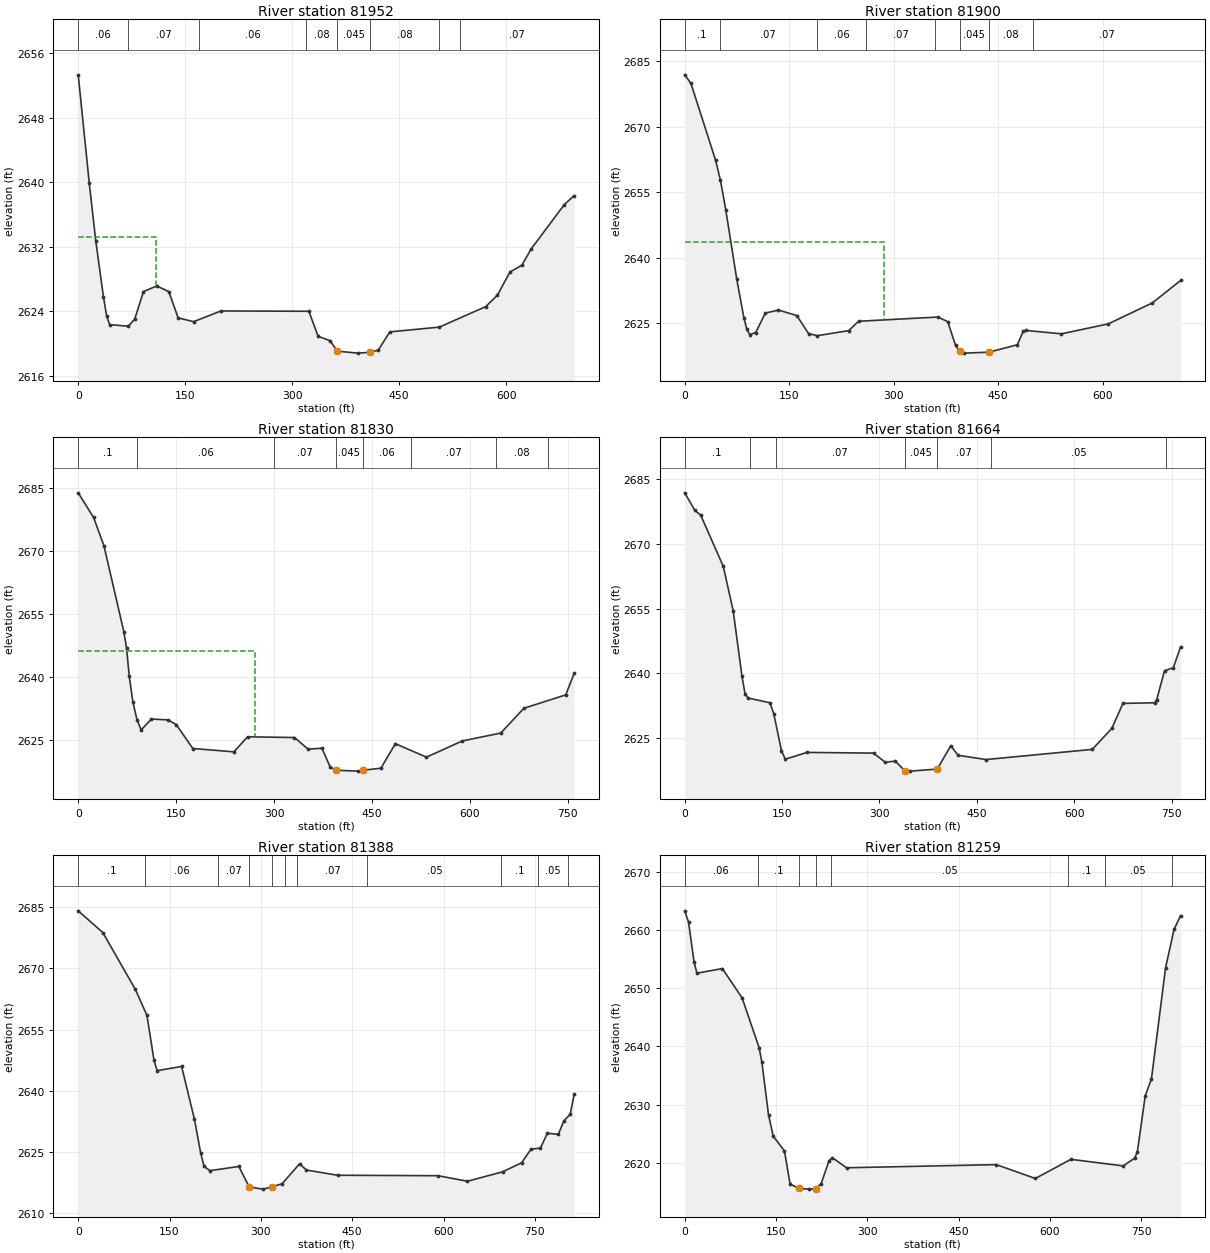
Type RM Length L Ch R = 1 ,81952   ,58.5,52,48.3
XS GIS Cut Line= 4
2353043.70123472692997.2654480372353352.15958209  693131.5683447
2353441.59261912693194.1714706232353676.95991054693277.935541919
#Sta/Elev= 30
       0 2653.35    15.5 2639.89    24.6 2632.74    35.4 2625.75    39.8 2623.43
    44.1 2622.32    70.3 2622.12    79.3 2623.03    91.5 2626.42     110 2627.12
     127 2626.43   140.1 2623.16   161.9 2622.69   200.2 2624.02   323.4 2623.98
   336.4 2620.87   353.2 2620.32   363.4 2619.02   392.2 2618.78   409.7 2618.88
   420.9 2619.17   436.9 2621.42   506.3 2622.01   571.5 2624.56   587.8 2625.98
   605.4 2628.86   622.2 2629.71   635.1 2631.72   681.7 2637.24   695.4 2638.35
#Mann= 8 ,-1,0
       0     .06       0      70     .07       0     170     .06       0
     320     .08       0   363.4    .045       0   409.7     .08       0
  505.59     .06       0  535.59     .07       0
#XS Ineff= 2 , 0
          108.42 2633.24
Permanent Ineff=
       F       F
Bank Sta=363.4,409.7
XS Rating Curve= 0 ,0
Exp/Cntr(USF)=0,0
Exp/Cntr=0.3,0.1

Type RM Length L Ch R = 1 ,81900   ,70.1,70.4,70
XS GIS Cut Line= 2
2352959.64791956693063.0030163092353634.37049895693290.560410535
#Sta/Elev= 30
       0  2681.9       9 2679.93    44.4 2662.31    51.2 2657.84      59 2650.97
    74.7 2635.14      85 2626.23    89.2 2623.59    93.4 2622.38   101.9 2622.81
   115.8  2627.3   134.7 2627.99     161 2626.73   177.9  2622.6   190.5 2622.12
   235.7 2623.28   249.6 2625.42   363.6 2626.39   377.8 2625.32   388.9 2619.87
   394.8 2618.55   401.6 2618.12   436.9 2618.34   477.6 2620.03     486 2623.08
   490.2 2623.32   540.9 2622.54   608.2 2624.82   671.4 2629.62   712.1 2634.77
#Mann= 8 ,-1,0
       0      .1       0      50     .07       0     190     .06       0
     260     .07       0     360     .08       0   394.8    .045       0
   436.9     .08       0     500     .07       0
#XS Ineff= 2 , 0
          285.81 2643.67
Permanent Ineff=
       F       F
Bank Sta=394.8,436.9
XS Rating Curve= 0 ,0
Exp/Cntr(USF)=0,0
Exp/Cntr=0.3,0.1

Type RM Length L Ch R = 1 ,81830   ,156.3,166,173
XS GIS Cut Line= 3
2352917.91250228693121.6313405862353562.82406932693335.276929051
2353626.42089566693383.968249212
#Sta/Elev= 30
       0 2683.95    23.5 2678.09    39.4 2671.33    69.8 2650.88      74 2646.97
    78.2 2640.22    83.7  2634.1    90.1 2629.81    96.4 2627.45   112.2 2630.03
   137.5 2629.83   150.2  2628.7   175.5 2623.01   238.4 2622.22   259.4  2625.8
   331.1 2625.63   352.1 2622.86   373.2 2623.08   385.8 2618.63   394.3 2617.84
     428 2617.62   436.4 2617.83   463.6 2618.32   485.7 2624.16   533.3 2620.95
   588.1 2624.81   647.1 2626.69   682.5  2632.6   746.6 2635.79   759.5 2640.91
#Mann= 8 ,-1,0
       0      .1       0      90     .06       0     300     .07       0
   394.3    .045       0   436.4     .06       0     510     .07       0
     640     .08       0  719.38     .07       0
#XS Ineff= 2 , 0
          270.89 2646.18
Permanent Ineff=
       F       F
Bank Sta=394.3,436.4
XS Rating Curve= 0 ,0
Exp/Cntr(USF)=0,0
Exp/Cntr=0.3,0.1

Type RM Length L Ch R = 1 ,81664   ,271.5,276,272.9
XS GIS Cut Line= 4
2352882.38043079693177.0038441522353141.11988877693316.237658261
2353227.56469136693396.766138876 2353554.6663778693526.868217119
#Sta/Elev= 30
       0 2681.76    15.7 2677.69    24.7  2676.6    59.5 2664.73    74.7 2654.49
    88.3  2639.3      93 2635.28    97.4  2634.3   131.4 2633.19   137.3 2630.62
   149.1 2622.12     155 2620.13   188.3 2621.71   290.9 2621.55   308.9 2619.43
   324.5  2619.7   339.1 2617.46   347.2 2617.38   389.1 2617.85   409.9 2623.26
   421.2 2621.04   464.3 2620.06   627.9 2622.41     658 2627.26   675.2 2633.05
   723.8 2633.19     727 2633.82   739.2 2640.61   752.7 2641.29     764 2646.13
#Mann= 7 ,-1,0
       0      .1       0     100     .06       0     140     .07       0
   339.1    .045       0   389.1     .07       0  471.97     .05       0
  741.97     .07       0
Bank Sta=339.1,389.1
XS Rating Curve= 0 ,0
Exp/Cntr=0.3,0.1

Type RM Length L Ch R = 1 ,81388   ,130.5,129.5,126.2
XS GIS Cut Line= 3
2352722.74313995693308.0230466592353055.35258838 693572.40491593
2353405.96430485693742.028490608
#Sta/Elev= 30
       0  2684.1    40.4 2678.78    93.8 2664.84   112.9 2658.46   124.5 2647.43
   129.6 2644.92   169.8 2645.95   190.9 2632.98   201.1 2624.74   206.8 2621.43
   216.4 2620.41   263.8 2621.44   280.8  2616.4   303.3 2615.88   317.8 2616.41
   334.9 2617.22   363.4 2622.07   374.8 2620.56   425.8 2619.28   590.8 2619.17
   639.1 2617.81   696.9 2620.12     728 2622.33   743.5 2625.64   759.1 2625.96
   770.5  2629.6   788.4 2629.29   797.4 2632.57   807.9 2634.24   814.4 2639.09
#Mann= 11 ,-1,0
       0      .1       0     110     .06       0     230     .07       0
   280.8    .045       0   317.8     .07       0     340      .1       0
     360     .07       0  474.88     .05       0  694.88      .1       0
  754.88     .05       0  804.88      .1       0
Bank Sta=280.8,317.8
XS Rating Curve= 0 ,0
Exp/Cntr(USF)=0,0
Exp/Cntr=0.3,0.1

Type RM Length L Ch R = 1 ,81259   ,185.4,179.6,170.4
XS GIS Cut Line= 2
2352706.82092857693493.8794374662353409.48737465693906.586195067
#Sta/Elev= 30
       0 2663.29     6.3 2661.37    15.5 2654.46    20.1 2652.58    61.9 2653.37
    94.3 2648.34   122.2 2639.81   126.8 2637.32   137.8 2628.22   145.4 2624.59
   163.9 2622.05   173.2 2616.37   187.5 2615.59     205 2615.48     215 2615.53
   224.2 2616.42   237.2 2620.35   242.8 2620.87     266 2619.15     512 2619.69
   576.2 2617.31   634.6  2620.6   720.6 2619.47   739.2 2620.79   743.8 2621.87
   756.8 2631.52     767 2634.43   790.2 2653.51   804.1  2660.1   814.9 2662.48
#Mann= 8 ,-1,0
       0     .06       0     120      .1       0   187.5    .045       0
     215      .1       0     240     .05       0     630      .1       0
     690     .05       0     800      .1       0
Bank Sta=187.5,215
XS Rating Curve= 0 ,0
Exp/Cntr=0.3,0.1

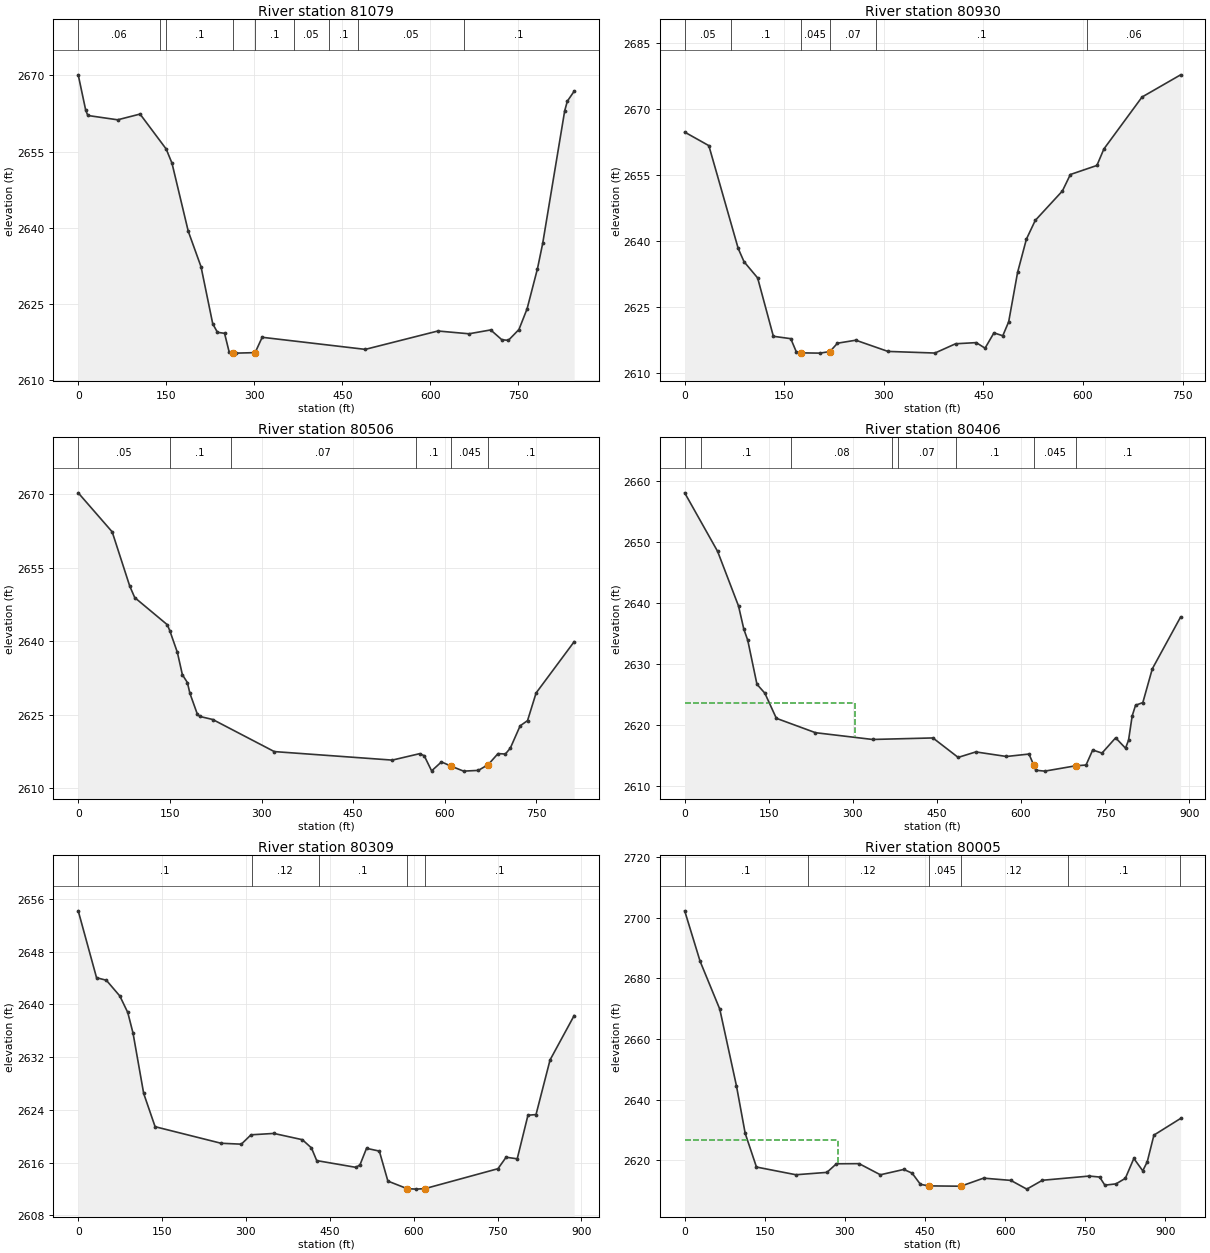
Type RM Length L Ch R = 1 ,81079   ,147,148.6,153.4
XS GIS Cut Line= 4
2352586.91916092693636.5346824272352756.12366065693759.592500411
2352863.79925139693767.2836140352353340.64829608693994.171465943
#Sta/Elev= 30
       0 2670.13    12.8 2663.15    16.4 2662.12    67.2 2661.27   105.4  2662.4
   149.9 2655.52   159.8 2652.73   187.5 2639.33   209.3 2632.33   229.3 2621.07
   237.3 2619.41   249.4 2619.21   257.4 2615.46   263.2 2615.36   269.4 2615.31
   301.5 2615.41   313.5 2618.43   489.2 2616.05     613 2619.67     666 2619.12
     703 2619.88   721.9 2617.95   733.1 2617.83   751.1 2619.96     765 2624.04
   782.7 2631.95   791.6 2636.93   829.1 2663.05   833.6 2664.94   845.2  2666.9
#Mann= 9 ,-1,0
       0     .06       0     140     .05       0     150      .1       0
   263.2    .045       0   301.5      .1       0  367.17     .05       0
  427.17      .1       0  477.17     .05       0  657.17      .1       0
Bank Sta=263.2,301.5
XS Rating Curve= 0 ,0
Exp/Cntr(USF)=0,0
Exp/Cntr=0.3,0.1

Type RM Length L Ch R = 1 ,80930   ,404.9,424.4,401.9
XS GIS Cut Line= 5
 2352643.2045703693840.0240044142352784.07441826693906.100417977
2352845.90466608693919.3497567962353131.53628659694057.952097552
2353342.23679479694050.681975891
#Sta/Elev= 30
       0 2664.79    36.4 2661.71    80.6 2638.33    89.4  2635.3   109.9 2631.61
   133.6 2618.33   159.8 2617.79     168 2614.85   175.1 2614.56   203.8  2614.5
   218.8 2614.86   230.2 2616.76   257.8 2617.44   306.2 2614.89     377 2614.52
   408.1 2616.63   439.2 2616.89   452.5 2615.63   465.9 2619.11   479.2 2618.45
   488.1 2621.64   501.5 2632.87   514.8 2640.44   528.1 2644.69     569 2651.39
     581 2655.14     621  2657.2   631.5 2660.95     689 2672.77   747.1 2677.82
#Mann= 6 ,-1,0
       0     .05       0      70      .1       0   175.1    .045       0
   218.8     .07       0  288.83      .1       0  606.31     .06       0
Bank Sta=175.1,218.8
XS Rating Curve= 0 ,0
Exp/Cntr(USF)=0,0
Exp/Cntr=0.3,0.1

Type RM Length L Ch R = 1 ,80506   ,104.8,100.1,94.8
XS GIS Cut Line= 5
2352365.94126099 694203.732946552352608.99699752694259.152493538
 2352900.9731678 694227.255937122353095.20622674694205.891704261
2353154.91882851694163.462824285
#Sta/Elev= 30
       0 2670.28    55.6 2662.31    84.3 2651.25    92.5 2648.89   145.9 2643.34
     150 2642.09   162.3  2637.7   170.5 2633.14   178.7 2631.54   182.8 2629.35
   195.1 2625.05   199.2 2624.62   220.2    2624   320.9 2617.45     514 2615.71
   558.7 2617.02   566.3 2616.61   578.4 2613.51   594.5 2615.34   610.6 2614.46
   630.7 2613.46   654.9 2613.61     671 2614.79   687.1 2617.04   699.1 2616.95
   707.2 2618.15   723.3 2622.71   735.4 2623.77   749.4 2629.41   811.7 2639.88
#Mann= 6 ,-1,0
       0     .05       0     150      .1       0  249.29     .07       0
  553.01      .1       0   610.6    .045       0     671      .1       0
Bank Sta=610.6,671
XS Rating Curve= 0 ,0
Exp/Cntr=0.3,0.1

Type RM Length L Ch R = 1 ,80406   ,91.7,96.7,97.1
XS GIS Cut Line= 4
2352390.13369151694595.8186034322352795.23494281694348.493628952
2353085.20215427694293.0587208792353161.95818083694207.774246921
#Sta/Elev= 30
       0 2658.09    58.7  2648.5    96.1 2639.52   105.5 2635.74   112.5 2633.92
   128.9 2626.71     143 2625.25   163.5 2621.13   233.3 2618.77   335.1 2617.66
   442.8 2617.91   487.8 2614.72   519.3 2615.62     574 2614.87   614.1 2615.27
   622.7 2613.45   626.3 2612.61   642.4 2612.47   697.1 2613.34   715.9 2613.47
   727.8 2615.93   744.4 2615.43   768.7 2617.93   786.3 2616.23   791.7 2617.53
   798.2 2621.52   804.2 2623.26   817.2 2623.71   834.1 2629.24   884.6 2637.74
#Mann= 8 ,-1,0
       0     .05       0      30      .1       0     190     .08       0
     370     .12       0     380     .07       0  484.63      .1       0
   622.7    .045       0   697.1      .1       0
#XS Ineff= 2 , 0
          302.92 2623.57
Permanent Ineff=
       F       F
Bank Sta=622.7,697.1
XS Rating Curve= 0 ,0
Exp/Cntr(USF)=0,0
Exp/Cntr=0.3,0.1

Type RM Length L Ch R = 1 ,80309   ,310,304,298.8
XS GIS Cut Line= 4
 2352444.6358497694718.7530384842353030.36838073694359.435585592
2353146.75585232694282.6972586182353193.65092367694244.700299414
#Sta/Elev= 30
       0  2654.2    32.8 2644.05    50.3 2643.67    74.5 2641.27    88.6 2638.78
      98 2635.66   117.1 2626.49   137.5 2621.45   255.4 2618.94   291.7  2618.8
     309 2620.22   349.8 2620.43   400.8 2619.48   417.1 2618.23   426.5 2616.31
   496.9 2615.28     504 2615.69   515.6 2618.17   538.5 2617.75   553.8  2613.2
   588.3 2612.05   604.8 2611.98   620.3 2612.06   750.7 2615.08   765.2 2616.82
   785.1 2616.58   804.3 2623.19   818.7 2623.29   843.8 2631.58   886.9 2638.31
#Mann= 5 ,-1,0
       0      .1       0     310     .12       0     430      .1       0
   588.3    .045       0   620.3      .1       0
Bank Sta=588.3,620.3
XS Rating Curve= 0 ,0
Exp/Cntr=0.3,0.1

Type RM Length L Ch R = 1 ,80005   ,292.1,270.6,248.3
XS GIS Cut Line= 4
2352753.52209143695031.1275785422352981.97766389694765.374762861
2353187.54352302694595.8186034322353277.09222068694297.322944577
#Sta/Elev= 30
       0 2702.23    28.9 2685.59    65.7 2669.83    96.9 2644.58   113.3 2628.89
   134.4 2617.78   208.3 2615.24   266.3 2616.02   284.1 2618.85   326.6  2618.9
   366.4 2615.23   410.3 2616.99   425.9 2615.76   441.4 2612.08     457 2611.57
     517 2611.46   559.6 2614.12   610.7 2613.38   640.6  2610.5   669.8 2613.42
   757.7 2614.81     777 2614.48   786.7 2611.81   807.6 2612.23   825.1 2614.06
     841 2620.61   857.7 2616.54   866.1  2619.5   878.6  2628.3   928.6  2633.8
#Mann= 6 ,-1,0
       0      .1       0     230     .12       0     457    .045       0
     517     .12       0  716.92      .1       0  926.92     .06       0
#XS Ineff= 2 , 0
          286.82 2626.82
Permanent Ineff=
       F       F
Bank Sta=457,517
XS Rating Curve= 0 ,0
Exp/Cntr(USF)=0,0
Exp/Cntr=0.3,0.1

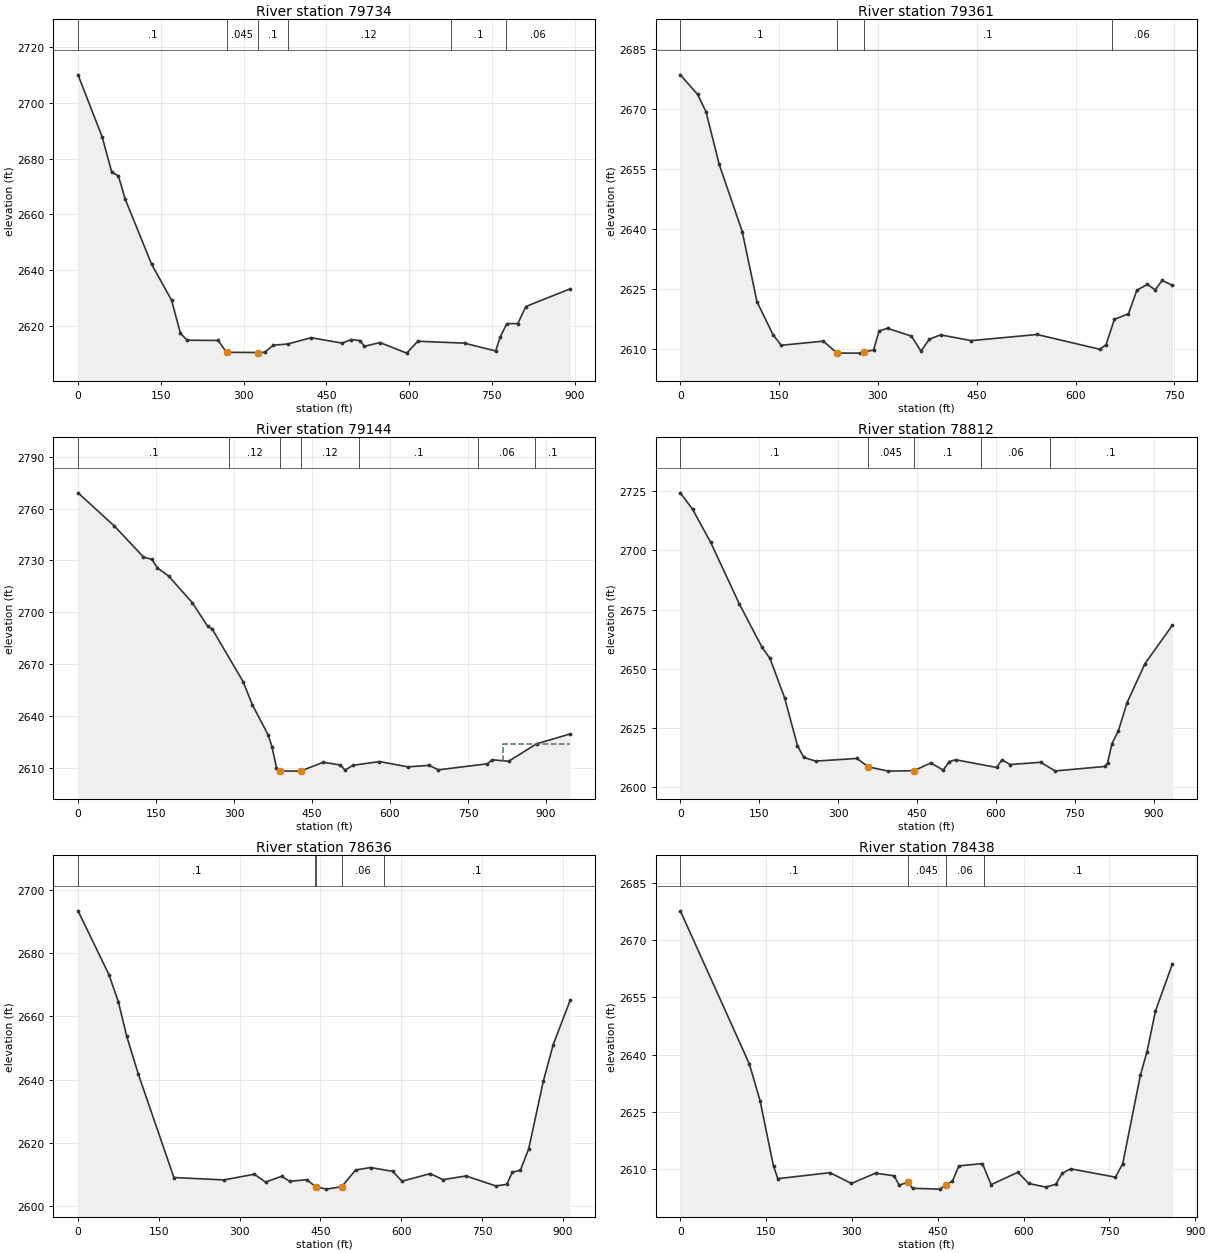
Type RM Length L Ch R = 1 ,79734   ,383.9,373.5,359.6
XS GIS Cut Line= 4
2353229.45638132695174.0679698162353269.08809479694719.943665287
2353313.79567806  694367.4399802 2353337.0615913694289.985123941
#Sta/Elev= 30
       0 2710.03      44 2687.62    61.1 2675.11    73.2 2673.78    85.2 2665.59
   133.4 2642.07   169.6 2629.14   185.6 2617.32   197.6 2614.81   253.9 2614.71
   269.2 2610.47   326.1 2610.39   338.2 2610.47   354.2 2613.03     380 2613.44
   422.5  2615.7   478.8 2613.76   494.9 2615.02   511.1 2614.69   519.1 2612.62
   547.3 2613.97   595.7 2610.17   615.9 2614.44   700.6 2613.75     757 2610.94
   765.2  2615.9   777.2 2620.75   797.2 2620.78   811.7 2626.89   892.1 2633.25
#Mann= 6 ,-1,0
       0      .1       0   269.2    .045       0   326.1      .1       0
     380     .12       0  675.85      .1       0  775.85     .06       0
Bank Sta=269.2,326.1
XS Rating Curve= 0 ,0
Exp/Cntr=0.3,0.1

Type RM Length L Ch R = 1 ,79361   ,226.6,216.9,206.8
XS GIS Cut Line= 3
2353690.72191937695017.9767495262353550.00253734694617.139721921
 2353439.1327212694314.379839369
#Sta/Elev= 30
       0 2678.59    26.3 2673.67      39 2669.34    59.1 2656.13    94.1 2639.28
   116.4 2621.76   140.7 2613.51   153.2 2610.84   217.1 2611.87     238 2608.89
   272.2 2608.87   278.7 2609.16   293.4 2609.65   301.8 2614.42   314.6  2615.1
   350.9 2613.12   365.4 2609.36   378.1 2612.36   395.1 2613.45   441.8    2612
   541.6 2613.54   636.8 2609.84   646.3 2610.96   659.1 2617.34   680.4 2618.72
   693.1 2624.62   709.3  2626.1   720.9  2624.7   731.5 2627.07   747.2 2625.86
#Mann= 4 ,-1,0
       0      .1       0     238    .045       0   278.7      .1       0
  654.82     .06       0
Bank Sta=238,278.7
XS Rating Curve= 0 ,0
Exp/Cntr(USF)=0,0
Exp/Cntr=0.3,0.1

Type RM Length L Ch R = 1 ,79144   ,330.7,331.9,335.3
XS GIS Cut Line= 3
     2354097.865      694955.8752353689.10266588694589.465713272
2353507.98433117694235.634287911
#Sta/Elev= 30
       0 2769.15      70 2749.89   125.8 2732.01   141.9  2730.6   152.7 2725.71
   174.2 2720.97   219.8 2705.52   249.4 2691.82     258  2690.3   317.5 2659.77
   335.3 2646.36   365.7 2628.94   372.9 2622.15   381.6 2610.05     389 2608.12
   426.6 2607.98     428    2608   471.5  2613.1   504.5 2611.54   513.4 2608.54
   528.7 2611.34   579.6 2613.53   634.6 2610.45   675.1 2611.34   693.1 2608.72
   787.4 2612.25   796.5 2614.58   827.9 2613.68   881.8 2623.79   946.4 2629.52
#Mann= 7 ,-1,0
       0      .1       0     290     .12       0     389    .045       0
     428     .12       0     540      .1       0  768.95     .06       0
  878.95      .1       0
#XS Ineff= 2 , 0
                          816.85         2623.52
Permanent Ineff=
       F       F
Bank Sta=389,428
XS Rating Curve= 0 ,0
Exp/Cntr=0.3,0.1

Type RM Length L Ch R = 1 ,78812   ,176.7,176.3,179.8
XS GIS Cut Line= 4
2354176.84342094694770.651775046 2354057.4451574 694476.42033989
2353899.66888057 694331.436734162353648.07968239694015.884180514
#Sta/Elev= 30
       0 2724.26    23.2 2717.37    57.7 2703.36   112.2 2677.41   155.2 2659.15
   170.5 2654.39   198.2 2637.82   222.7 2617.63   234.7 2612.68   257.1 2611.11
   335.6 2612.23   357.3 2608.69   395.3 2606.88   444.2 2607.07     476 2610.33
   499.7 2607.33   511.5 2610.92   523.3 2611.68   601.2 2608.42   611.4 2611.67
   626.8 2609.67     685 2610.62   712.4 2606.96   806.9 2608.85     812 2610.27
   820.5 2618.51   832.6 2623.89     849 2635.68   883.2 2652.23   935.4 2668.45
#Mann= 5 ,-1,0
       0      .1       0   357.3    .045       0   444.2      .1       0
  571.81     .06       0  701.81      .1       0
Bank Sta=357.3,444.2
XS Rating Curve= 0 ,0
Exp/Cntr(USF)=0,0
Exp/Cntr=0.3,0.1

Type RM Length L Ch R = 1 ,78636   ,196.1,197.6,201.6
XS GIS Cut Line= 4
     2354398.857      694643.2582354052.66809034694217.666706048
2353956.89648677694068.462782835     2353841.505      693920.417
#Sta/Elev= 30
       0 2693.36    57.4 2673.21    74.9 2664.64    90.3 2653.82     112 2641.75
     178 2609.14   270.8 2608.38   327.5 2610.19   348.1 2607.69   378.2 2609.54
   392.9 2607.93   424.2 2608.46   441.3 2606.26   461.2 2605.47   489.6 2606.23
   515.2 2611.51   543.1 2612.29   584.1 2611.08   601.4 2607.97   653.8 2610.36
   677.5 2608.46   720.3 2609.63   775.7 2606.47     796 2606.99   806.1 2610.79
   821.4 2611.49   836.6 2618.19   863.7 2639.52   882.2 2651.14   913.6 2665.11
#Mann= 5 ,-1,0
       0      .1       0     440     .06       0   441.3    .045       0
   489.6     .06       0  568.61      .1       0
Bank Sta=441.3,489.6
XS Rating Curve= 0 ,0
Exp/Cntr=0.3,0.1

Type RM Length L Ch R = 1 ,78438   ,237.5,242.6,246.1
XS GIS Cut Line= 2
2354503.96588224694551.9206443142354053.24720244693819.188041961
#Sta/Elev= 30
       0 2677.67   120.6 2637.61   139.4 2627.97   162.9 2610.83   170.5 2607.55
   261.5 2609.12   299.1  2606.3   341.3    2609   373.7  2608.3   382.7 2605.84
   397.3 2606.63     406 2605.03   454.1 2604.81   464.2 2605.93   475.8 2606.93
   486.9  2610.9   528.1  2611.5   543.3 2605.99   590.2 2609.22     609 2606.29
   638.6 2605.36   656.1 2606.04   667.7 2608.97   682.2 2610.13   760.7 2607.94
   773.4 2611.49   804.3 2634.67   815.7 2640.73   830.5 2651.41   860.3 2663.82
#Mann= 4 ,-1,0
       0      .1       0   397.3    .045       0   464.2     .06       0
     530      .1       0
Bank Sta=397.3,464.2
XS Rating Curve= 0 ,0
Exp/Cntr(USF)=0,0
Exp/Cntr=0.3,0.1

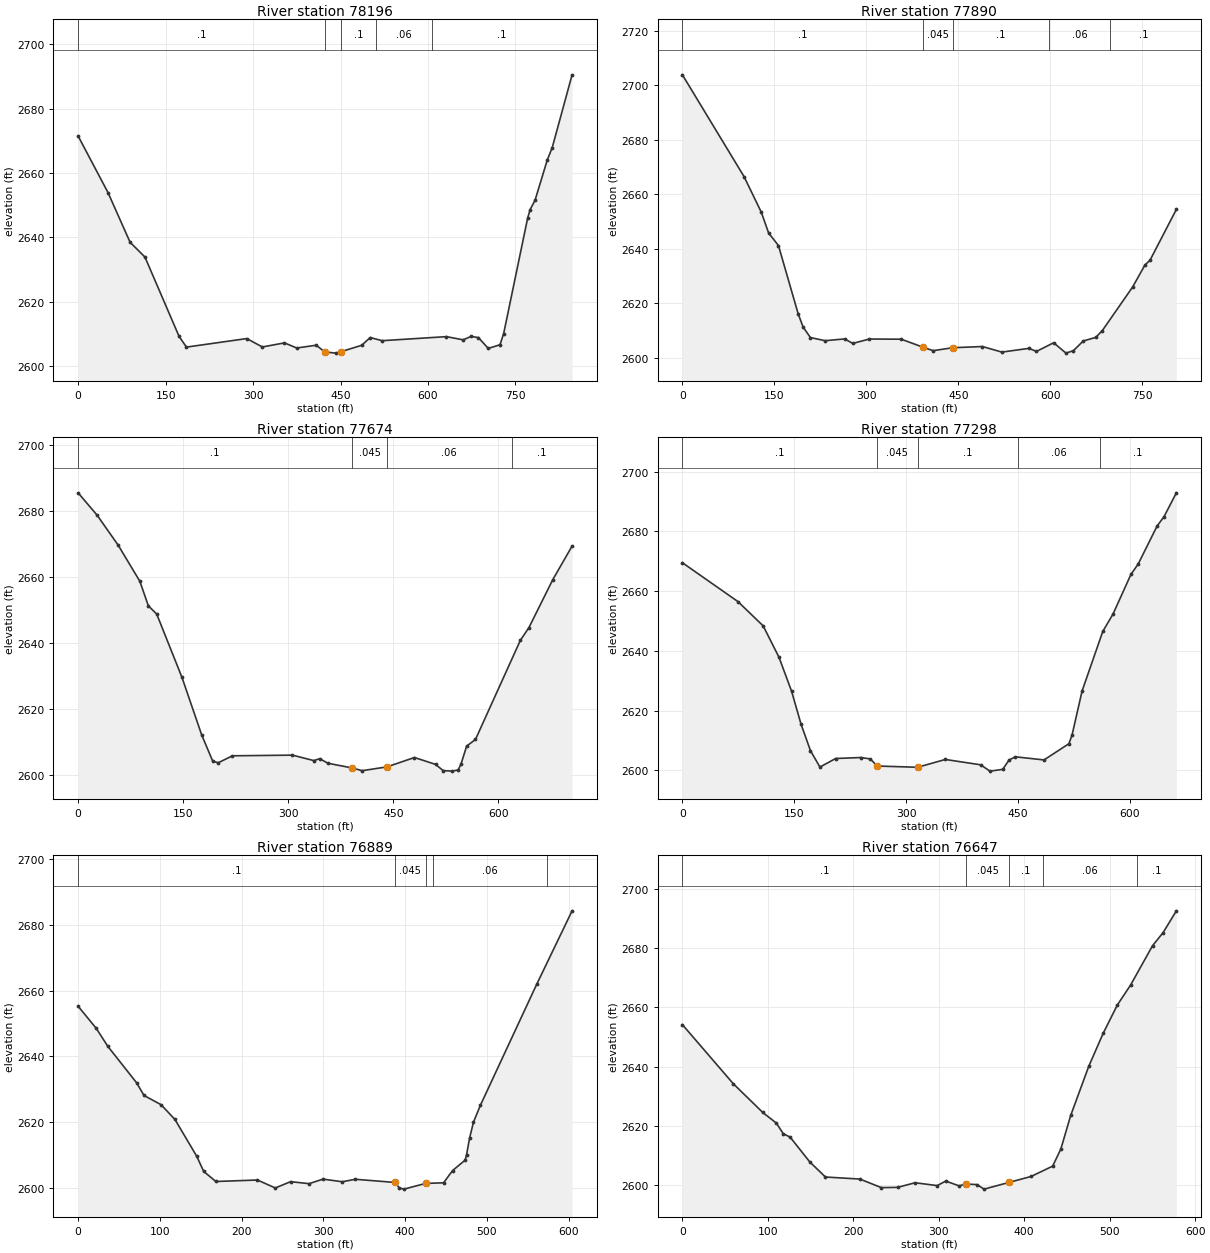
Type RM Length L Ch R = 1 ,78196   ,297.6,306.1,301.2
XS GIS Cut Line= 3
2354623.29066613694486.0183895212354458.63737097 693974.51553791
2354359.74442723693680.990751801
#Sta/Elev= 30
       0 2671.49    51.3 2653.91    89.1 2638.51   114.6 2633.92   173.2 2609.26
   185.8 2605.96   289.2 2608.61     316    2606   353.9 2607.27   374.9 2605.68
   408.5 2606.55   422.8 2604.46   442.1 2604.09   451.4 2604.58   486.3 2606.52
   500.9 2608.93   521.3 2607.95   631.6 2609.21   660.3 2608.22   673.8 2609.27
   686.5 2608.92   703.4 2605.54   723.5  2606.7   729.8 2610.18   770.8 2645.92
   775.1 2648.64   783.5  2651.5   804.7 2664.12   813.1 2667.92   847.1 2690.48
#Mann= 5 ,-1,0
       0      .1       0   422.8    .045       0   451.4      .1       0
     510     .06       0  607.35      .1       0
Bank Sta=422.8,451.4
XS Rating Curve= 0 ,0
Exp/Cntr=0.3,0.1

Type RM Length L Ch R = 1 ,77890   ,209,215.3,205.4
XS GIS Cut Line= 3
2354803.60567495694501.5610152872354773.38989753693924.943262919
2354748.21008302693698.324932295
#Sta/Elev= 30
       0 2703.75   100.5 2666.42   128.6 2653.38   140.6 2645.73   156.6 2641.14
   188.6 2616.21   196.7 2611.29   208.7  2607.4   232.7 2606.25   264.7  2606.9
   277.7 2605.25   304.8 2606.86   356.9  2606.8   392.9  2603.8   408.9 2602.59
   440.6 2603.67   489.1 2604.11   520.9 2602.07   565.2 2603.44   577.2 2602.31
   605.3 2605.49   625.4 2601.69   637.5  2602.6   653.6 2606.15   673.8 2607.45
   684.4 2609.87   734.1 2625.96   754.3 2634.07   762.3 2635.71   805.4 2654.42
#Mann= 5 ,-1,0
       0      .1       0   392.9    .045       0   440.6      .1       0
  597.41     .06       0  697.41      .1       0
Bank Sta=392.9,440.6
XS Rating Curve= 0 ,0
Exp/Cntr(USF)=0,0
Exp/Cntr=0.3,0.1

Type RM Length L Ch R = 1 ,77674   ,358.6,376,380.9
XS GIS Cut Line= 4
2354989.46375887694421.3807419452354987.73687016694129.854054021
2354957.20254349693904.7994113082354982.02697983693720.029942729
#Sta/Elev= 30
       0 2685.62    27.1 2678.84    57.2 2669.73    88.2 2658.76   100.2 2651.36
   112.2 2648.84   148.2 2629.65   176.4 2612.17   192.2 2604.18   200.2 2603.74
   220.2 2605.84     306 2606.04   336.6 2604.38   344.7 2604.97   356.8 2603.57
   390.9 2602.16   405.5 2601.32     441 2602.49   480.1 2605.32   510.2 2603.24
     521 2601.36   534.4 2601.19   542.5 2601.57   546.5  2603.3   554.6 2608.78
   567.2  2610.8   631.3 2640.88   643.4 2644.69   677.5 2659.26   705.1 2669.47
#Mann= 4 ,-1,0
       0      .1       0   390.9    .045       0     441     .06       0
  618.65      .1       0
Bank Sta=390.9,441
XS Rating Curve= 0 ,0
Exp/Cntr=0.3,0.1

Type RM Length L Ch R = 1 ,77298   ,392.6,409,410.1
XS GIS Cut Line= 2
2355183.22364363694431.7056934632355396.98065461693804.796011128
#Sta/Elev= 30
       0 2669.52    74.5  2656.5   108.3 2648.36   129.5 2637.85   146.4 2626.46
     159 2615.49   171.7 2606.56   184.4 2601.05   205.5 2603.92   239.3 2604.25
     252 2603.78   261.2  2601.4   315.4 2600.98   352.6  2603.6   399.9 2601.81
   412.4 2599.69   429.5 2600.28     438 2603.41   446.4 2604.49   484.9 2603.44
   518.3 2608.88   522.5 2611.78   535.9  2626.5   563.7 2646.51   577.4 2652.31
   601.5 2665.63   611.2  2669.1   636.6 2681.86   645.7 2684.91   662.4 2692.95
#Mann= 5 ,-1,0
       0      .1       0   261.2    .045       0   315.4      .1       0
     450     .06       0     560      .1       0
Bank Sta=261.2,315.4
XS Rating Curve= 0 ,0
Exp/Cntr(USF)=0,0
Exp/Cntr=0.3,0.1

Type RM Length L Ch R = 1 ,76889   ,230.7,242.1,244.9
XS GIS Cut Line= 3
 2355339.9357241694524.2228483492355569.07203617694310.194424981
2355785.61844099694116.309853225
#Sta/Elev= 30
       0 2655.27    22.2 2648.54    36.3 2643.09    71.5 2632.02    80.6 2628.15
   101.4 2625.36   118.4 2620.88   145.1 2609.68   153.6 2605.08   168.5 2602.02
   219.3 2602.47   241.2 2600.05   259.9 2601.97   282.5 2601.36   299.5 2602.74
   323.1 2601.94   339.2 2602.69   387.5 2601.73     393 2600.06   398.6  2599.7
   425.1 2601.44     447 2601.62   458.1 2605.35   473.4 2608.52   475.1  2610.1
   478.8 2615.17   483.6 2620.06   492.1  2625.2   560.9 2661.92   604.2 2684.25
#Mann= 5 ,-1,0
       0      .1       0   387.5    .045       0   425.1      .1       0
  433.55     .06       0  573.55      .1       0
Bank Sta=387.5,425.1
XS Rating Curve= 0 ,0
Exp/Cntr(USF)=0,0
Exp/Cntr=0.3,0.1

Type RM Length L Ch R = 1 ,76647   ,237.3,235.9,238.2
XS GIS Cut Line= 4
2355350.29425226694545.7910067982355491.65234128694538.249997197
 2355832.8818238694423.5704317572355907.28623579694405.563238152
#Sta/Elev= 30
       0 2654.17    59.4 2634.31      94  2624.6     110 2620.99     118 2617.43
   126.1 2616.27   149.1 2607.91   167.4 2602.84   207.7 2602.15   232.8 2599.27
   251.8 2599.35   272.3 2600.91   298.2 2599.95   308.2 2601.47   323.6 2599.88
   332.3 2600.47   344.7 2600.29   353.1 2598.76   382.2 2601.02     408 2603.02
   433.3 2606.51   442.9 2612.29   454.4 2623.57   475.5 2640.11   492.4 2651.24
     509  2660.8   524.5 2667.51   550.2 2680.77   562.6  2685.2   578.1 2692.52
#Mann= 5 ,-1,0
       0      .1       0   332.3    .045       0   382.2      .1       0
  421.56     .06       0  531.54      .1       0
Bank Sta=332.3,382.2
XS Rating Curve= 0 ,0
Exp/Cntr=0.3,0.1