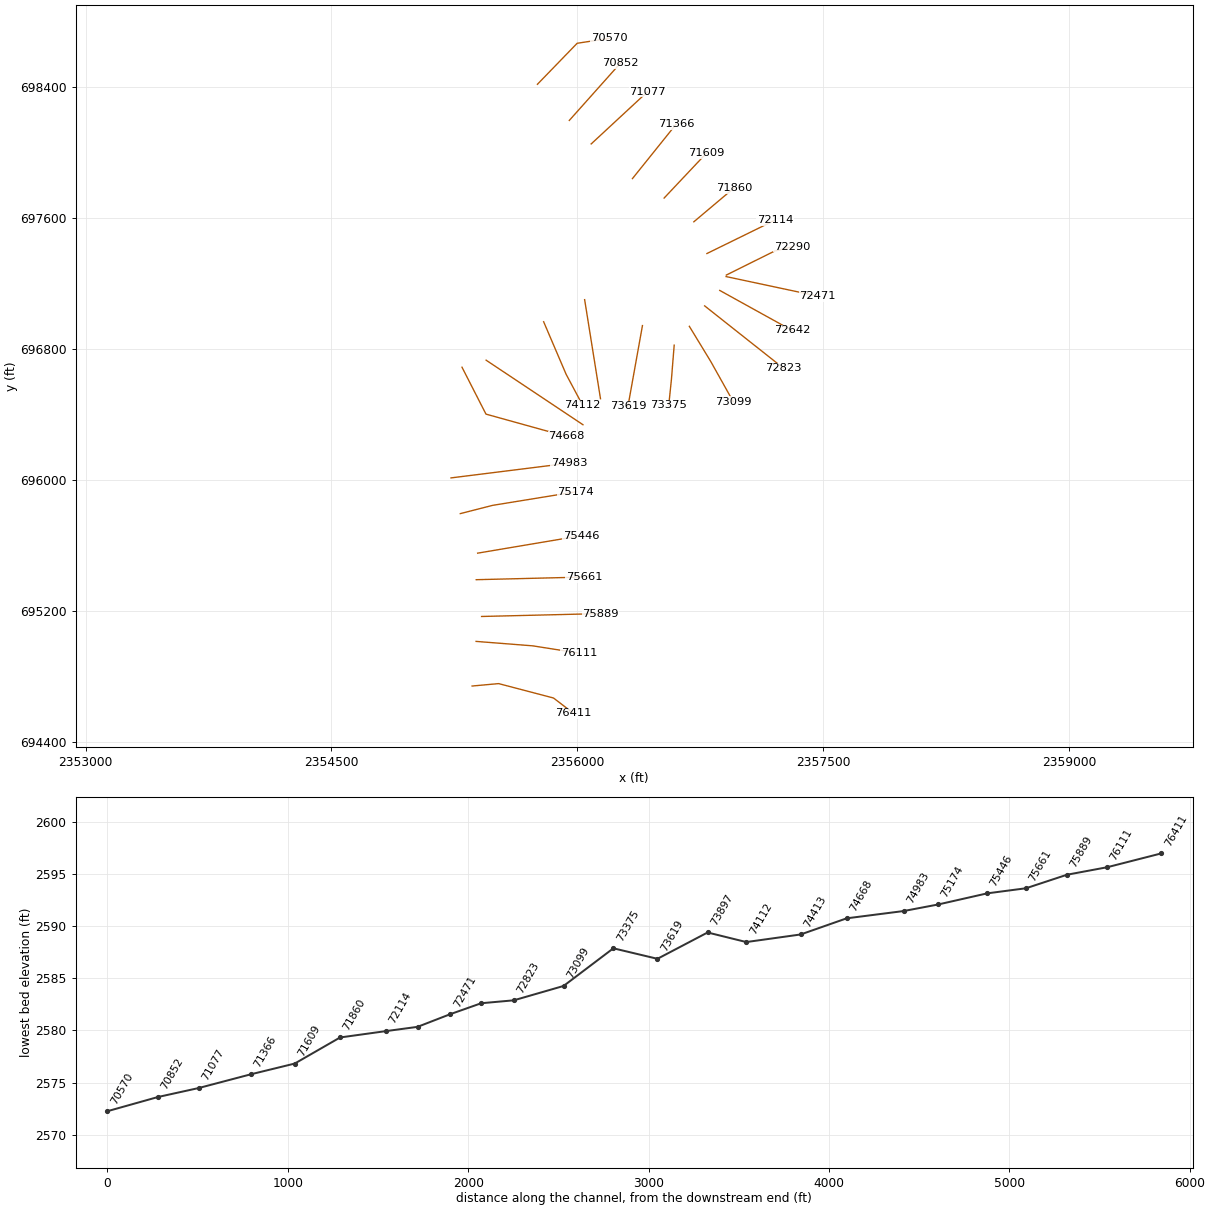
HEC-RAS study GLADYFK.prj: GLADYFK

--- GLADYFK.g01 (geometry) --- (continued)

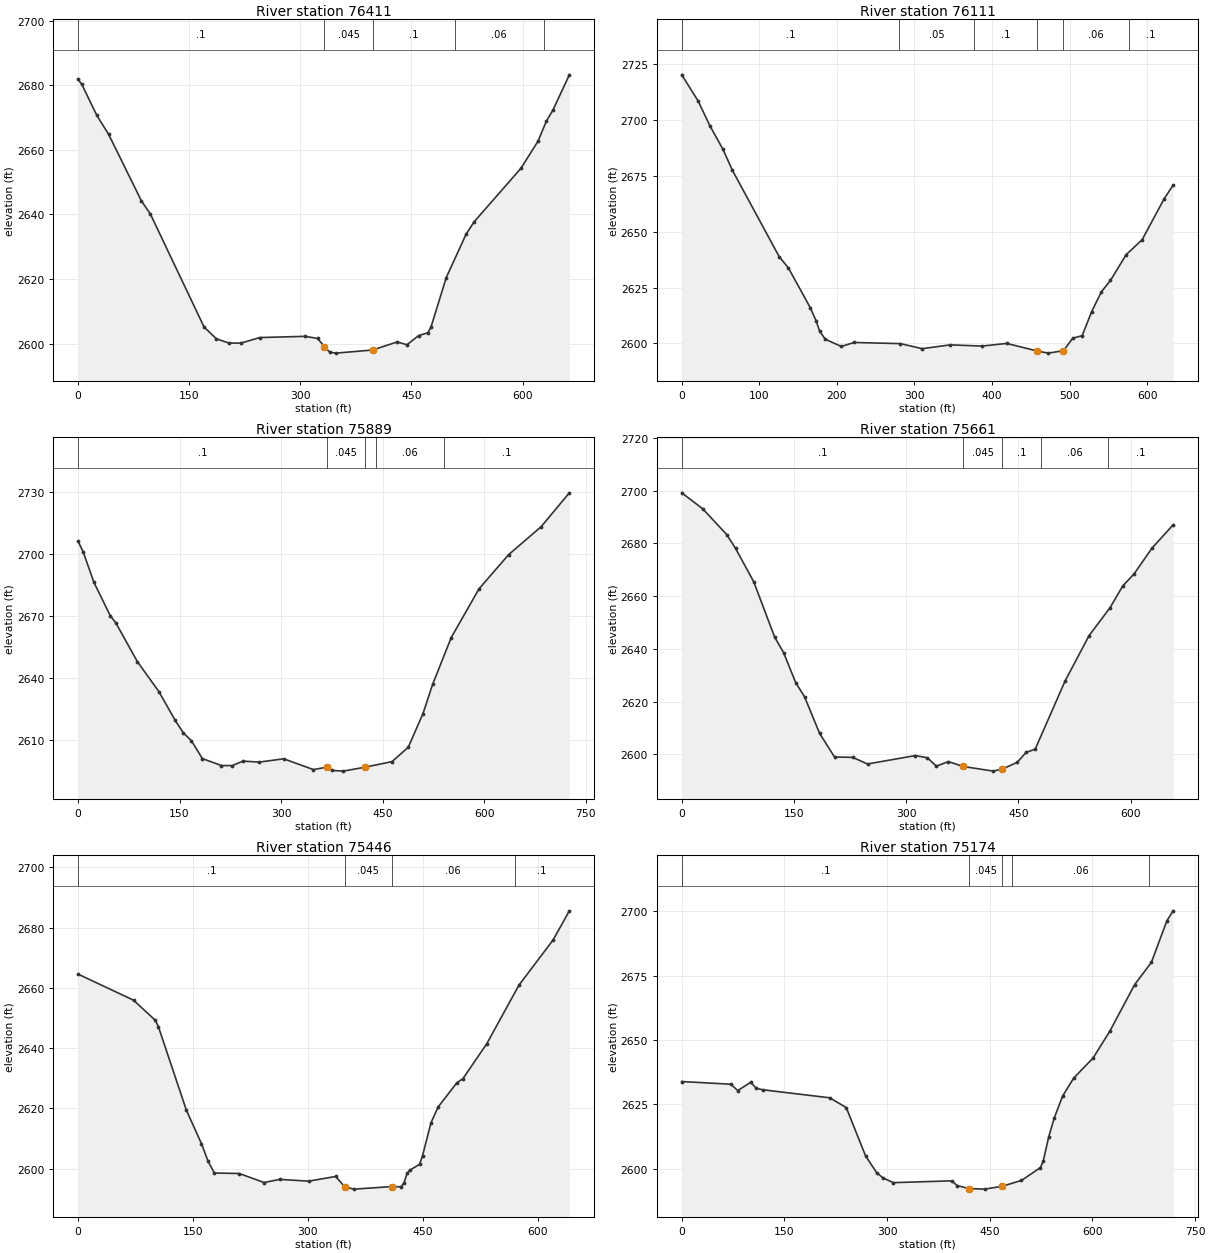
Type RM Length L Ch R = 1 ,76411   ,306.5,300.2,302.2
XS GIS Cut Line= 4
2355358.95099246694742.6844717012355520.66019224694757.500040668
2355855.35844407694669.6183767792355978.12325628694575.750731505
#Sta/Elev= 30
       0 2681.91     5.2 2680.32    25.3 2670.77    41.4 2664.82    85.6 2644.21
    97.6 2640.18   170.2 2605.09   186.7 2601.48   203.2 2600.16   219.8 2600.12
   245.4 2601.85   306.4 2602.22   323.2 2601.58   332.6 2599.05   339.7 2597.31
     348 2597.02   397.6 2597.99   430.7 2600.49   443.9 2599.62   459.6 2602.45
   472.1 2603.33   476.2 2605.02   496.9 2620.43   523.6 2633.84   534.6 2637.75
   597.8 2654.35   620.6 2662.67     632 2668.93   640.9 2672.38     663 2683.29
#Mann= 5 ,-1,0
       0      .1       0   332.6    .045       0   397.6      .1       0
  508.43     .06       0  628.43      .1       0
Bank Sta=332.6,397.6
XS Rating Curve= 0 ,0
Exp/Cntr(USF)=0,0
Exp/Cntr=0.3,0.1

Type RM Length L Ch R = 1 ,76111   ,219.5,222.5,219.8
XS GIS Cut Line= 3
2355383.09242891695015.1227618482355728.68314218694987.996381516
2356012.07737915694943.359716229
#Sta/Elev= 30
       0 2720.14    21.1 2708.44    36.3 2697.33    53.2 2686.77    65.3 2677.44
   125.6 2638.83   137.5 2633.78   165.6 2616.06   173.6 2609.84   177.6  2605.6
   185.1 2601.87   205.7 2598.69   222.3 2600.45   281.9 2599.94     310 2597.68
   346.1 2599.38   387.2 2598.85     419 2600.03     458 2596.65   472.4 2595.69
   492.1 2596.77   504.1 2602.36   516.2 2603.49   528.4 2614.19   541.1 2623.16
   552.7 2628.18   572.9 2639.69   593.6 2646.44   621.8 2664.64   633.5 2670.82
#Mann= 6 ,-1,0
       0      .1       0     280     .05       0  376.65      .1       0
     458    .045       0   492.1     .06       0  576.65      .1       0
Bank Sta=458,492.1
XS Rating Curve= 0 ,0
Exp/Cntr=0.3,0.1

Type RM Length L Ch R = 1 ,75889   ,227,227.2,227.5
XS GIS Cut Line= 2
2355416.58486721695167.2425539692356141.91235492 695184.79079964
#Sta/Elev= 30
       0 2706.29     7.6 2701.12    23.6 2686.26    47.6 2670.21    55.6 2666.85
    87.6 2648.01   119.6 2633.38   143.6 2619.49   155.6 2613.46   167.6 2609.66
   183.6 2601.05   211.7 2597.68   227.7 2597.63   243.6 2599.81   267.7 2599.34
   303.7 2600.93   347.7 2595.71   367.7 2596.91   375.7 2595.31   391.7 2594.97
   423.4 2596.85   463.7 2599.57   487.7 2606.54   509.4 2622.83   523.7 2636.99
   551.1 2659.62   592.1 2683.16   635.8  2699.7   683.8 2713.22   725.5 2729.63
#Mann= 5 ,-1,0
       0      .1       0   367.7    .045       0   423.4      .1       0
     440     .06       0     540      .1       0
Bank Sta=367.7,423.4
XS Rating Curve= 0 ,0
Exp/Cntr(USF)=0,0
Exp/Cntr=0.3,0.1

Type RM Length L Ch R = 1 ,75661   ,212.1,215.1,220.2
XS GIS Cut Line= 2
2355383.99102656695391.7613973442356040.47713891695407.883596016
#Sta/Elev= 30
       0 2699.14    28.2 2693.04    60.2 2683.27    71.9 2678.07    96.2 2665.43
   124.2 2644.42   136.2 2638.52   152.2 2627.24   164.2  2621.8   184.2 2607.98
   204.2 2599.01   228.3  2598.9   248.3 2596.38   312.3 2599.57   328.3 2598.72
   340.3 2595.56   356.3 2597.28   376.1 2595.44   416.3 2593.67   428.3 2594.45
   448.3 2596.99   460.3  2600.8   472.3 2601.97   512.3 2627.83   544.3    2645
   572.4 2655.62   589.4 2663.86   604.4 2668.37   628.4 2678.16   656.7 2687.01
#Mann= 5 ,-1,0
       0      .1       0   376.1    .045       0   428.3      .1       0
     480     .06       0     570      .1       0
Bank Sta=376.1,428.3
XS Rating Curve= 0 ,0
Exp/Cntr=0.3,0.1

Type RM Length L Ch R = 1 ,75446   ,271.6,272,271.3
XS GIS Cut Line= 2
 2355392.6051895695553.7484557822356025.07484837695660.439332704
#Sta/Elev= 30
       0  2664.6    72.6 2655.92     101 2649.24     105 2647.11   141.5  2619.4
   161.2 2608.28   169.9 2602.36   178.1 2598.53   210.5 2598.37     243 2595.37
   263.2 2596.42   301.1 2595.83   336.3 2597.38   348.4 2593.91   360.6 2593.18
   409.3 2594.02   421.4 2593.95   425.5 2595.15   429.5 2598.39     433 2599.47
   445.8 2601.39   449.8 2604.31   460.8 2615.22   470.1 2620.45   494.5 2628.49
   502.6 2629.91   533.7  2641.5   575.6 2660.92   620.2 2675.94   641.4 2685.61
#Mann= 4 ,-1,0
       0      .1       0   348.4    .045       0   409.3     .06       0
     570      .1       0
Bank Sta=348.4,409.3
XS Rating Curve= 0 ,0
Exp/Cntr(USF)=0,0
Exp/Cntr=0.3,0.1

Type RM Length L Ch R = 1 ,75174   ,191.2,191.3,189.3
XS GIS Cut Line= 3
2355286.71040398695795.0921920312355483.52231766 695845.42417875
2355991.57672738695928.060805816
#Sta/Elev= 30
       0 2633.86    71.7 2632.82    81.8 2630.37   100.6 2633.54   108.9 2631.27
     118 2630.68     216 2627.56   240.3 2623.78   268.6    2605   284.9 2598.44
   294.1 2596.46   309.2 2594.62   394.3 2595.33   402.4  2593.5   419.6 2592.32
   442.9 2592.11   468.4 2593.24   496.3 2595.48     524 2600.46     528 2602.87
   536.1 2612.35   544.2 2619.73   556.4 2628.21   572.6  2635.2   600.9 2642.97
   625.3 2653.34   661.7 2671.49   686.1 2680.09   708.9 2696.32   717.9 2700.11
#Mann= 5 ,-1,0
       0      .1       0   419.6    .045       0   468.4      .1       0
  483.15     .06       0  683.15      .1       0
Bank Sta=419.6,468.4
XS Rating Curve= 0 ,0
Exp/Cntr=0.3,0.1

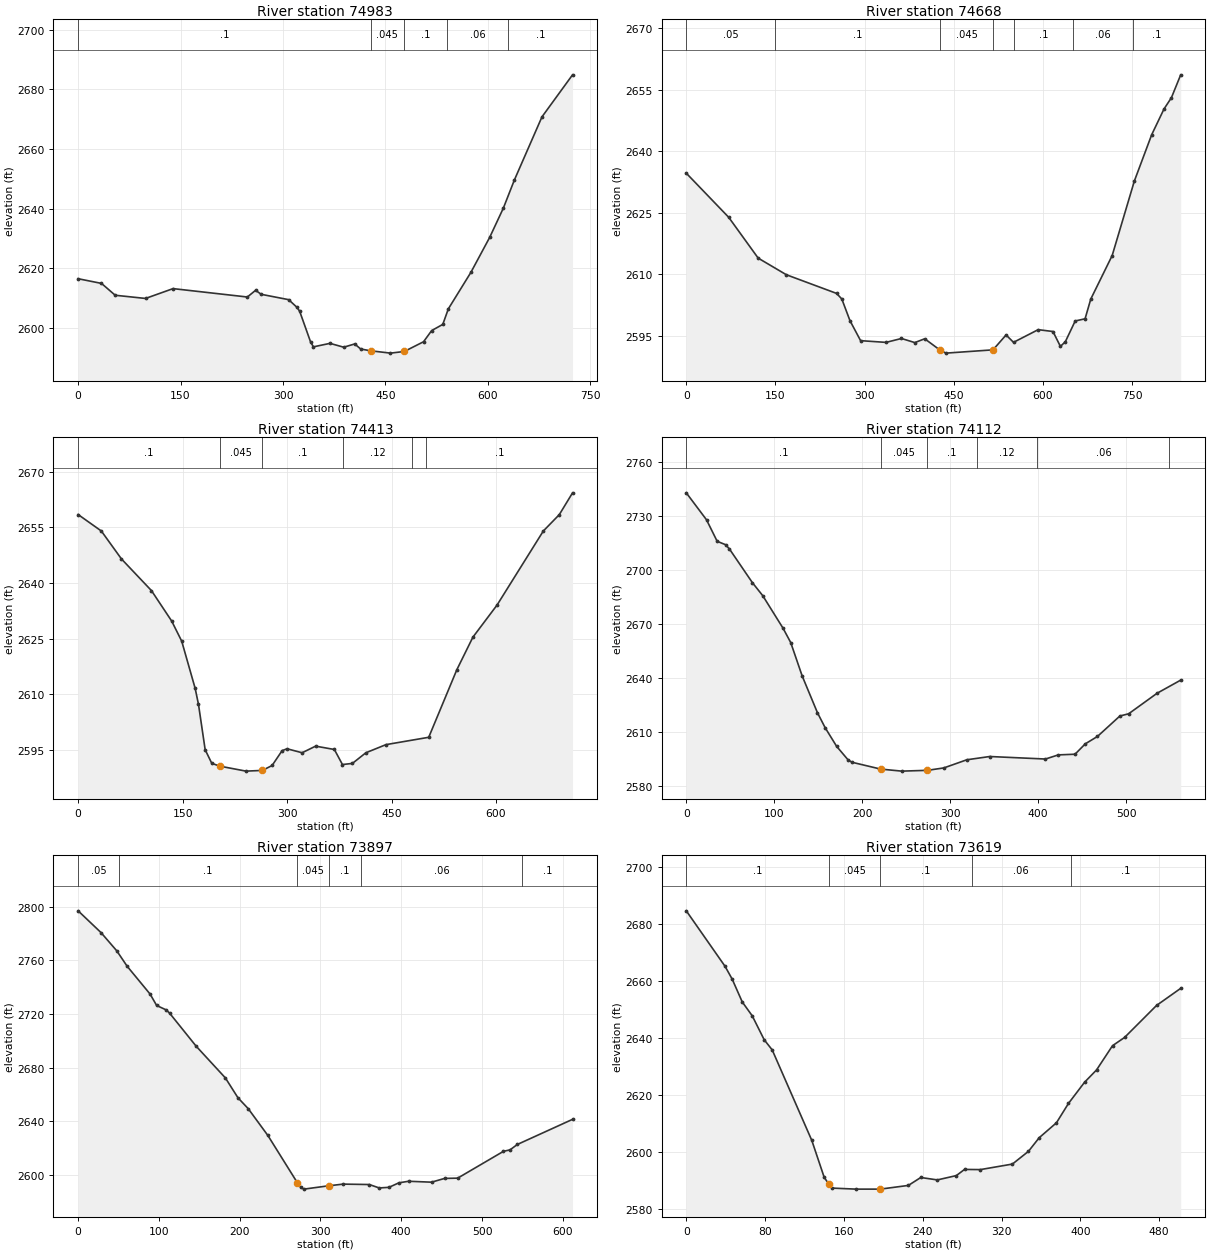
Type RM Length L Ch R = 1 ,74983   ,332.6,315.5,291
XS GIS Cut Line= 2
2355230.26619332696013.1332747592355948.70260194696102.937825837
#Sta/Elev= 30
       0 2616.46    34.2 2614.89    54.3 2610.91    98.7 2609.84     139 2613.14
   247.8 2610.32   259.9 2612.58     268 2611.23   308.3 2609.43   320.4 2606.86
   324.4 2605.54   340.5 2595.16   344.6 2593.59   368.8 2594.76   388.9 2593.47
     405 2594.56   413.8 2592.86   428.2 2592.27   457.4 2591.48   477.6 2592.03
   505.8  2595.3   517.7 2599.05     534 2601.13   542.1 2606.34   575.1 2618.58
   602.6 2630.32   622.7 2640.18   638.8  2649.6   679.2  2670.8     724 2684.92
#Mann= 5 ,-1,0
       0      .1       0   428.2    .045       0   477.6      .1       0
     540     .06       0     630      .1       0
Bank Sta=428.2,477.6
XS Rating Curve= 0 ,0
Exp/Cntr(USF)=0,0
Exp/Cntr=0.3,0.1

Type RM Length L Ch R = 1 ,74668   ,256.9,254.7,239.2
XS GIS Cut Line= 3
2355297.10378035696688.7160987762355443.37189876696402.474057346
2355935.18996955696265.966258055
#Sta/Elev= 30
       0 2634.65    71.4 2623.89     121 2613.94   168.4 2609.89   252.9 2605.34
   261.7 2603.98   275.4  2598.7   293.3 2593.82   336.1  2593.4   362.1 2594.35
   384.5 2593.35   401.2 2594.28   427.1  2591.5   436.9 2590.78   516.1 2591.58
   538.1 2595.21   550.6 2593.41   592.1  2596.5     617 2596.05   629.5 2592.42
   637.8 2593.56   654.4 2598.62     671 2599.15   680.6 2603.96   716.6 2614.57
     754 2632.77   783.1 2644.03   803.8  2650.3   816.3 2653.06   831.9 2658.63
#Mann= 7 ,-1,0
       0     .05       0     150      .1       0   427.1    .045       0
   516.1     .08       0  551.45      .1       0  651.45     .06       0
  751.45      .1       0
Bank Sta=427.1,516.1
XS Rating Curve= 0 ,0
Exp/Cntr=0.3,0.1

Type RM Length L Ch R = 1 ,74413   ,308.1,301.3,273.5
XS GIS Cut Line= 2
2355444.41550743696731.5696833852356035.05313183696337.811267119
#Sta/Elev= 30
       0 2658.46    33.3 2654.02    62.2 2646.48   105.3 2637.93   134.3 2629.73
   148.7  2624.3     168 2611.58   172.8 2607.25   182.4    2595   191.9 2591.33
   203.5 2590.57     241 2589.23   264.5 2589.42   278.5 2590.75   292.9 2594.76
     300 2595.26   321.6 2594.19     341 2595.97   367.9 2595.07   379.5 2591.01
   393.8 2591.31   413.1 2594.18     442 2596.38   503.4 2598.36   543.8 2616.61
   566.8 2625.37   601.5 2634.04   667.9 2654.01   690.9 2658.44   709.9 2664.32
#Mann= 6 ,-1,0
       0      .1       0   203.5    .045       0   264.5      .1       0
     380     .12       0     480     .06       0     500      .1       0
Bank Sta=203.5,264.5
XS Rating Curve= 0 ,0
Exp/Cntr(USF)=0,0
Exp/Cntr=0.3,0.1

Type RM Length L Ch R = 1 ,74112   ,219.4,214.5,209.6
XS GIS Cut Line= 3
2355795.28531063696966.3097122942355932.48973857 696645.45322886
2356032.69171717 696457.61723766
#Sta/Elev= 30
       0 2743.09      23 2728.11    35.1 2716.16    44.7 2714.27    49.1 2711.87
    75.2 2693.15    86.9 2685.96     110 2667.86   118.7 2659.92   131.7 2641.38
   149.1 2620.91   157.8 2612.64   170.9 2602.25   183.9 2594.74   188.3 2593.43
   220.9 2589.63   244.9  2588.5   274.1 2588.94   292.7 2590.28   318.8  2594.8
   344.9 2596.62   408.2 2595.22   422.8 2597.52   441.8 2597.89   453.5 2603.67
   467.3 2607.76   492.8 2619.13   502.7 2620.34   535.1 2631.77   561.9 2639.05
#Mann= 6 ,-1,0
       0      .1       0   220.9    .045       0   274.1      .1       0
     330     .12       0  398.96     .06       0  548.96      .1       0
Bank Sta=220.9,274.1
XS Rating Curve= 0 ,0
Exp/Cntr=0.3,0.1

Type RM Length L Ch R = 1 ,73897   ,287.4,278,274.4
XS GIS Cut Line= 2
2356045.41519541697101.1499512832356142.12778888696496.696242103
#Sta/Elev= 30
       0 2797.04    28.3 2780.82    47.8 2767.22    60.7 2755.68    89.1 2734.92
    97.2 2726.43   109.3 2723.04   113.4 2720.58   146.1 2696.06   182.3 2672.38
   197.9 2657.54   210.6 2649.44   234.9 2629.44   271.5  2594.1   275.4 2590.83
   279.5 2589.42   310.1  2591.9   328.1 2593.16   360.5 2592.85   372.7 2590.31
   384.8 2590.75     397  2594.1   409.1 2595.29   437.5 2594.61   453.7 2597.41
   469.9 2597.62   526.6 2617.63   534.7 2618.71   543.7 2622.72   612.1 2641.48
#Mann= 6 ,-1,0
       0     .05       0      50      .1       0   271.5    .045       0
   310.1      .1       0     350     .06       0     550      .1       0
Bank Sta=271.5,310.1
XS Rating Curve= 0 ,0
Exp/Cntr(USF)=0,0
Exp/Cntr=0.3,0.1

Type RM Length L Ch R = 1 ,73619   ,255.7,244.2,243.3
XS GIS Cut Line= 2
2356398.21181932696943.0024579522356309.56583044696449.062503123
#Sta/Elev= 30
       0 2684.51    39.4 2665.02    46.6 2660.54    56.8 2652.55    66.9  2647.7
    79.1 2639.27    87.2 2635.73   127.4 2603.97     140    2591   144.6 2588.69
   148.2 2587.25   172.2 2586.89   196.9 2586.89   225.4 2588.19     238 2590.97
   254.8 2590.12   274.1 2591.64   282.4  2593.8   298.5 2593.74     331 2595.68
   347.3 2600.15   358.2 2604.93   375.7 2610.16   387.9 2616.95   404.2 2624.37
   416.4  2628.7   432.6  2637.2   444.8 2640.08   477.3 2651.32   501.8 2657.32
#Mann= 5 ,-1,0
       0      .1       0   144.6    .045       0   196.9      .1       0
     290     .06       0     390      .1       0
Bank Sta=144.6,196.9
XS Rating Curve= 0 ,0
Exp/Cntr=0.3,0.1

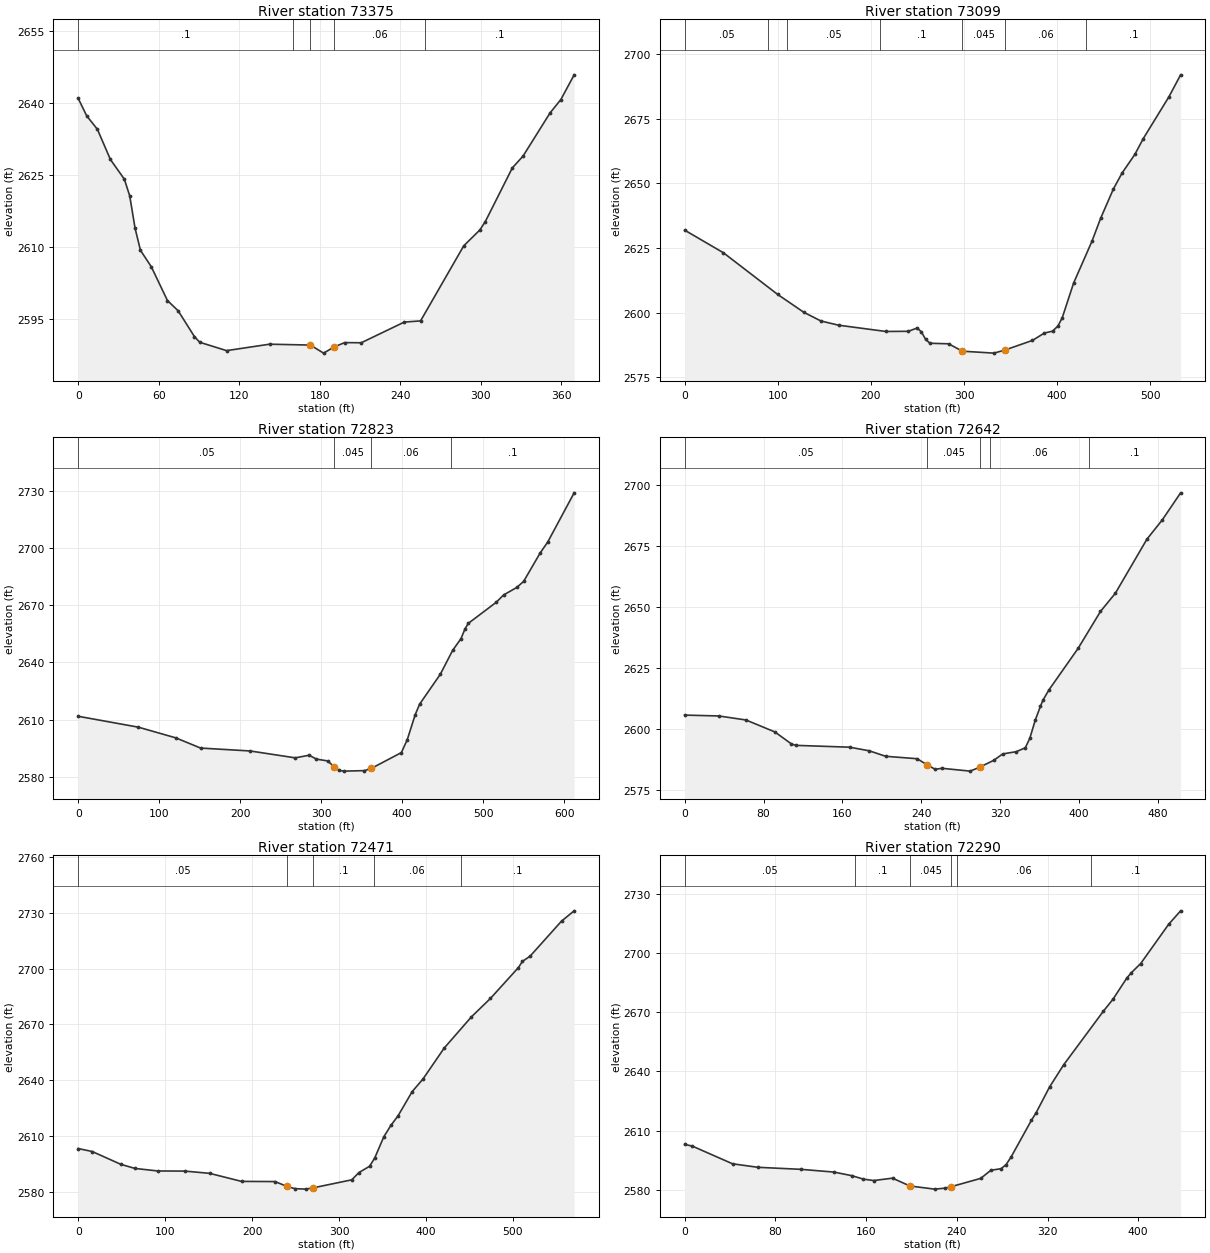
Type RM Length L Ch R = 1 ,73375   ,266.1,276.1,288.3
XS GIS Cut Line= 3
2356591.78582519696823.465154956 2356575.0709525696615.496063446
 2356558.4486187696455.328035373
#Sta/Elev= 30
       0 2640.95     6.3 2637.33    14.3 2634.52      24 2628.23    34.4 2624.12
    38.4 2620.65    42.4 2613.89    46.4 2609.32    54.5 2605.88    66.5 2598.86
    74.5 2596.72    86.6 2591.36    90.6 2590.16   110.6 2588.42   142.6 2589.76
   173.1 2589.58   182.9  2587.9   190.9  2589.2   198.6 2590.09     211 2590.06
   243.1 2594.37   255.2 2594.61   287.4 2610.25   299.4 2613.55   303.5 2615.31
   323.6 2626.47   331.6 2628.94   351.8 2637.95   359.8 2640.72   369.7 2645.86
#Mann= 5 ,-1,0
       0      .1       0     160     .06       0   173.1    .045       0
   190.9     .06       0  258.64      .1       0
Bank Sta=173.1,190.9
XS Rating Curve= 0 ,0
Exp/Cntr(USF)=0,0
Exp/Cntr=0.3,0.1

Type RM Length L Ch R = 1 ,73099   ,268.7,275.8,286.1
XS GIS Cut Line= 3
2356684.24135093696938.3466886812356814.74830507696724.065209171
2356952.27222638696478.208900859
#Sta/Elev= 30
       0 2631.88    41.6 2623.13    99.8 2607.02   127.8 2600.12   146.3 2596.72
   165.3 2595.09   216.2 2592.66   240.2 2592.73   249.6    2594   254.1 2592.57
   258.8 2589.58   263.4  2588.1   283.5 2587.89   298.2 2585.03   332.1 2584.28
   343.9 2585.47   373.4 2589.19   386.3 2592.05   395.1 2592.79   400.9 2594.79
   405.5    2598   417.7 2611.42   437.5 2627.68   446.7 2636.47   460.4 2647.82
   469.6 2653.93   483.4 2661.17   492.5 2667.33     520 2683.48   532.6 2692.01
#Mann= 7 ,-1,0
       0     .05       0      90      .1       0     110     .05       0
     210      .1       0   298.2    .045       0   343.9     .06       0
   430.9      .1       0
Bank Sta=298.2,343.9
XS Rating Curve= 0 ,0
Exp/Cntr=0.3,0.1

Type RM Length L Ch R = 1 ,72823   ,181.7,180.7,187.7
XS GIS Cut Line= 2
2356777.66768882697063.1557181352357257.77663497 696683.21338665
#Sta/Elev= 30
       0 2611.69    74.4 2605.96   120.5 2600.36   151.1 2595.01   212.3 2593.48
     268 2589.87   285.1 2591.25     294 2589.22   307.9 2588.26   316.4 2585.09
   322.1 2583.31   327.8  2582.9   353.4 2583.16     362 2584.35     399 2592.64
   406.2 2599.36   416.1 2612.56   421.5 2618.05     447 2633.71   462.3  2646.3
   472.5 2652.39   477.6 2657.62   481.6 2660.47   515.8 2671.43   525.3 2675.41
   541.4  2679.3   549.9 2682.49   570.4 2697.46   579.6 2703.11   612.3 2728.99
#Mann= 4 ,-1,0
       0     .05       0   316.4    .045       0     362     .06       0
     460      .1       0
Bank Sta=316.4,362
XS Rating Curve= 0 ,0
Exp/Cntr(USF)=0,0
Exp/Cntr=0.3,0.1

Type RM Length L Ch R = 1 ,72642   ,164.6,171.2,178.7
XS GIS Cut Line= 2
2356869.78071626697157.4568656252357310.07428216696913.821995869
#Sta/Elev= 30
       0 2605.62    34.7 2605.26    62.2 2603.61    91.5 2598.71   107.9  2593.9
   112.5  2593.2   167.3 2592.45   187.4 2590.95   203.9 2588.71   235.9 2587.71
   246.2 2585.14   254.2 2583.37     261 2583.78   289.7 2582.62   299.2 2584.22
   313.6 2587.06   322.7 2589.68   336.5 2590.61   345.6  2592.2   350.2 2596.11
   355.8 2603.66     361 2609.28   363.6 2611.82   369.8 2616.09   399.3 2633.08
   421.9 2648.17     437 2655.65     469 2677.83   484.6 2685.75   503.2 2696.86
#Mann= 5 ,-1,0
       0     .05       0   246.2    .045       0   299.2     .05       0
     310     .06       0     410      .1       0
Bank Sta=246.2,299.2
XS Rating Curve= 0 ,0
Exp/Cntr=0.3,0.1

Type RM Length L Ch R = 1 ,72471   ,168.5,181.5,189.6
XS GIS Cut Line= 2
2356908.38281755697242.0835805322357466.36978372 697123.12891668
#Sta/Elev= 30
       0 2603.36    16.1 2601.77    48.9 2594.91    65.2 2592.69    91.6 2591.32
   122.5 2591.26   151.1 2590.05   187.9 2585.72   226.5 2585.63   239.9 2583.05
   249.3 2581.84   261.5 2581.57   270.3 2582.26   314.7 2586.57   322.9 2590.46
   335.2 2593.86   341.1 2598.31   351.5 2609.65   359.7  2615.8   367.9 2620.92
   384.2 2633.97   396.5 2640.64     421 2657.32   452.3 2674.08   474.2 2683.98
   506.3 2700.51     511 2703.85   519.8 2706.67     556 2725.52   570.5 2731.03
#Mann= 5 ,-1,0
       0     .05       0   239.9    .045       0   270.3      .1       0
     340     .06       0     440      .1       0
Bank Sta=239.9,270.3
XS Rating Curve= 0 ,0
Exp/Cntr(USF)=0,0
Exp/Cntr=0.3,0.1

Type RM Length L Ch R = 1 ,72290   ,173.1,175.4,175.7
XS GIS Cut Line= 3
 2356910.3580256697251.5833475842357204.18558695697397.646282198
2357310.39098518697423.464169061
#Sta/Elev= 30
       0 2602.95     6.5  2602.2    42.2 2593.18    64.6  2591.4   102.4 2590.38
   131.6 2588.99   147.4 2587.16   157.7  2585.4   166.7  2584.7   183.3  2585.9
   198.6 2581.95   220.4 2580.35   229.8 2580.84   235.3 2581.64   261.1 2585.79
     270 2589.89     279  2590.7   283.4 2592.71   287.9 2596.65   305.8 2615.21
   309.9 2618.97   321.8 2632.07   334.2 2643.27   369.3 2670.47   377.7 2676.48
   389.9  2687.2     394 2689.99   402.2 2694.59   426.9  2714.5   437.4 2721.28
#Mann= 6 ,-1,0
       0     .05       0     150      .1       0   198.6    .045       0
   235.3      .1       0     240     .06       0  358.13      .1       0
Bank Sta=198.6,235.3
XS Rating Curve= 0 ,0
Exp/Cntr(USF)=0,0
Exp/Cntr=0.3,0.1

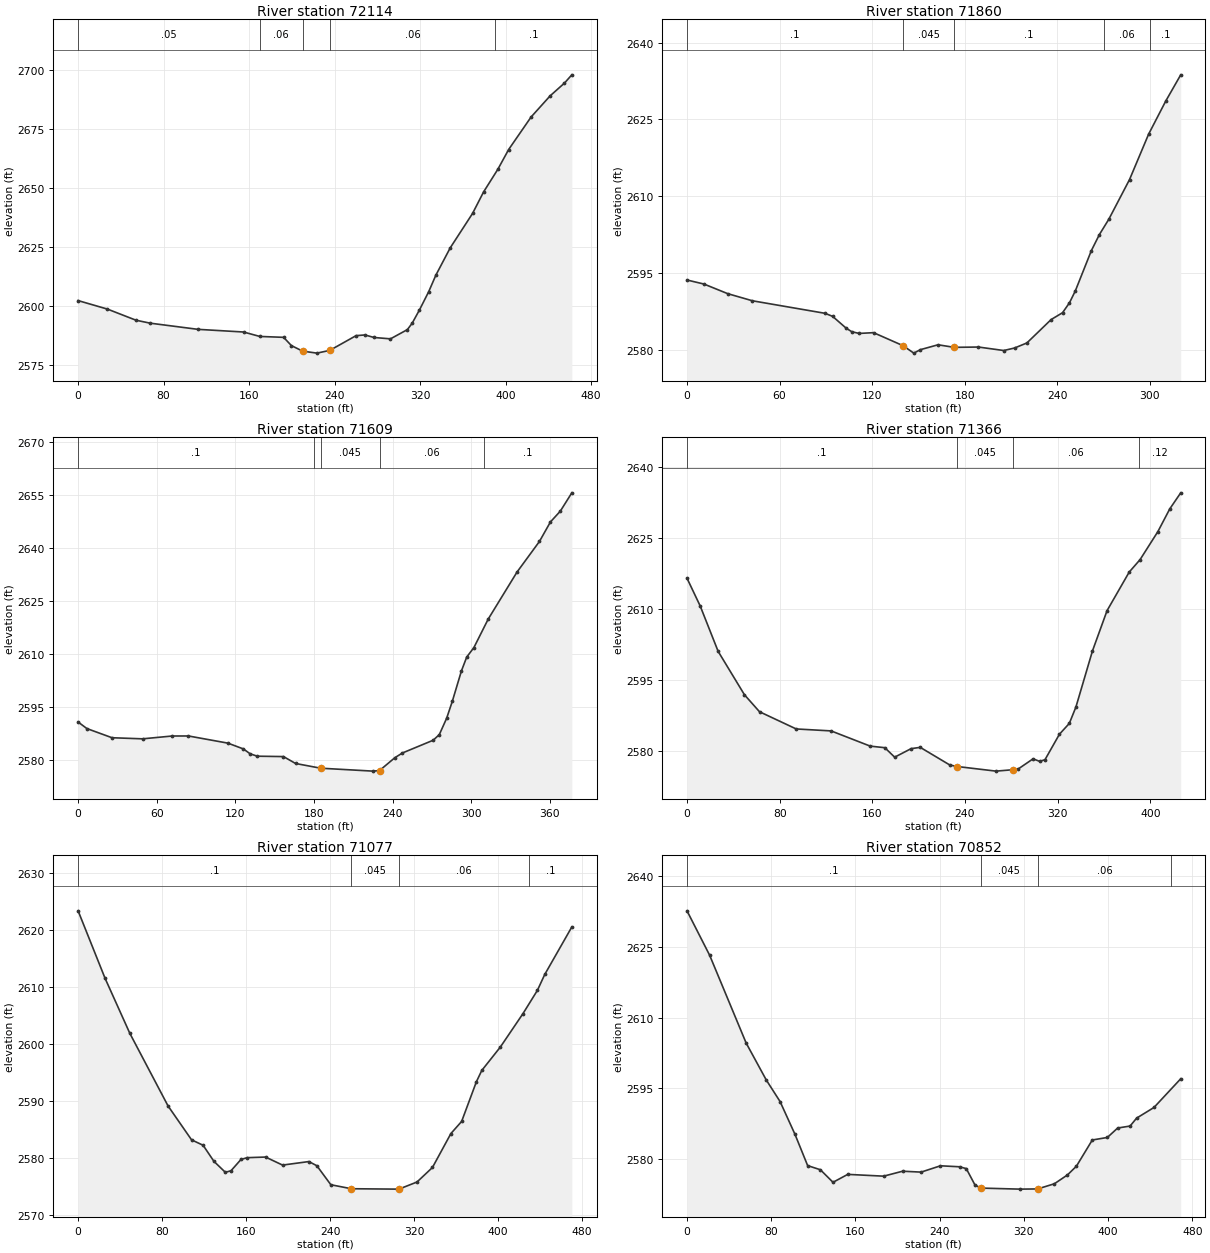
Type RM Length L Ch R = 1 ,72114   ,250.4,253.9,256.7
XS GIS Cut Line= 2
2356791.52572219697382.6985760942357206.35986773697586.083437188
#Sta/Elev= 30
       0  2602.2    27.5 2598.59    54.2 2593.88    67.5 2592.63   112.1 2590.02
   154.8 2588.89     170 2587.01   192.3 2586.63   199.6 2583.13   210.1 2580.78
   223.5 2579.94   235.5  2581.1   260.1 2587.34   268.4 2587.64   276.9 2586.57
   292.3 2585.99   308.1  2589.9   312.6 2592.61   319.4 2598.22   328.1    2606
   334.8    2613   348.2 2624.54   369.1 2639.12   379.4 2648.22   392.8 2657.86
   402.9 2666.22   423.9    2680   441.7 2688.95   455.1 2694.36     462 2697.86
#Mann= 5 ,-1,0
       0     .05       0     170     .06       0   210.1    .045       0
   235.5     .06       0     390      .1       0
Bank Sta=210.1,235.5
XS Rating Curve= 0 ,0
Exp/Cntr=0.3,0.1

Type RM Length L Ch R = 1 ,71860   ,249.3,251.7,254.6
XS GIS Cut Line= 2
2356711.73074274697576.3655779292356956.47853981697782.588258798
#Sta/Elev= 30
       0 2593.62      11 2592.83    26.4 2590.95    42.4 2589.56    89.5 2587.11
    94.4 2586.51   103.1 2584.22   106.8 2583.51   111.6 2583.18   120.9 2583.33
     140 2580.79     147 2579.33   151.3 2580.01   162.7 2580.96   173.2 2580.46
   188.9 2580.52   205.3 2579.84   212.3 2580.33   220.3 2581.32     236 2585.89
   243.4 2587.23   247.9 2589.17   251.7  2591.5   262.1 2599.38   267.3 2602.51
   273.4  2605.5   286.8 2613.24   299.2 2622.13   310.3  2628.6     320 2633.72
#Mann= 5 ,-1,0
       0      .1       0     140    .045       0   173.2      .1       0
     270     .06       0     300      .1       0
Bank Sta=140,173.2
XS Rating Curve= 0 ,0
Exp/Cntr(USF)=0,0
Exp/Cntr=0.3,0.1

Type RM Length L Ch R = 1 ,71609   ,240.7,242.9,244.5
XS GIS Cut Line= 2
2356530.43607824697721.4013095292356788.78097515697995.609489585
#Sta/Elev= 30
       0 2590.74     6.7 2588.88    25.9 2586.28    49.2 2585.97    71.8 2586.77
    84.2 2586.78   114.3 2584.75   126.1 2583.11   131.2 2581.74   136.7 2581.05
   156.7 2580.94   165.9 2578.99     185 2577.65     225 2576.82     230 2576.99
   241.7 2580.63   247.5 2581.97   270.9 2585.57   275.6 2587.17   281.2 2591.81
   285.5 2596.58   292.5 2605.25   296.5 2609.13     302 2611.84   312.9  2619.9
   334.9 2633.23     352  2641.9   360.4 2647.43   367.9 2650.47   376.7 2655.67
#Mann= 5 ,-1,0
       0      .1       0     180     .06       0     185    .045       0
     230     .06       0     310      .1       0
Bank Sta=185,230
XS Rating Curve= 0 ,0
Exp/Cntr(USF)=0,0
Exp/Cntr=0.3,0.1

Type RM Length L Ch R = 1 ,71366   ,292.9,289,286
XS GIS Cut Line= 2
  2356337.104672697840.1759279862356604.01070585698172.549479568
#Sta/Elev= 30
       0 2616.46    11.4  2610.6    26.9 2601.03    49.6 2591.89    62.6 2588.31
    94.3 2584.68   124.4 2584.27   158.2 2581.06   170.8 2580.73   179.3 2578.73
   193.5 2580.53   201.4  2580.8     227 2577.07   233.4 2576.76   266.8 2575.79
   281.7 2576.09     286 2576.25   298.8 2578.38   304.5 2577.85   309.1  2578.2
   321.6 2583.58   330.1 2585.85   335.8  2589.3   350.1 2601.14   362.7 2609.63
   381.8 2617.75   391.2 2620.38   406.6  2626.3   416.8 2631.06   426.3 2634.46
#Mann= 4 ,-1,0
       0      .1       0   233.4    .045       0   281.7     .06       0
     390     .12       0
Bank Sta=233.4,281.7
XS Rating Curve= 0 ,0
Exp/Cntr(USF)=0,0
Exp/Cntr=0.3,0.1

Type RM Length L Ch R = 1 ,71077   ,223.1,225.2,229.1
XS GIS Cut Line= 2
2356085.30652687698051.6863699022356430.26998571698371.470014228
#Sta/Elev= 30
       0 2623.32    25.7 2611.47    49.3 2601.81    85.7 2589.07   108.1 2583.12
   119.1 2582.17   129.4 2579.35   140.3 2577.42   145.7  2577.7   155.2 2579.68
   161.1 2579.99   178.6  2580.1   194.8 2578.69   219.9 2579.31   227.5 2578.57
   240.8 2575.24   260.3 2574.54   303.9 2574.47   305.9 2574.49   322.9 2575.72
   337.6 2578.27   355.2 2584.23   365.4 2586.35   379.5 2593.33   384.6  2595.3
   402.3 2599.41   423.9 2605.29   437.6 2609.36   444.6 2612.15   470.4 2620.49
#Mann= 4 ,-1,0
       0      .1       0   260.3    .045       0   305.9     .06       0
     430      .1       0
Bank Sta=260.3,305.9
XS Rating Curve= 0 ,0
Exp/Cntr(USF)=0,0
Exp/Cntr=0.3,0.1

Type RM Length L Ch R = 1 ,70852   ,282.2,281.4,279.9
XS GIS Cut Line= 2
2355951.85350994698195.2113126312356264.08320991698545.210734373
#Sta/Elev= 30
       0 2632.64    21.5 2623.22    56.2 2604.59    75.3 2596.76    88.4 2592.19
   102.6 2585.22   114.6  2578.6   126.7 2577.72   138.7 2575.06   152.7 2576.74
   186.8 2576.36   204.8 2577.41   222.4 2577.22   240.8 2578.56   258.9 2578.35
   265.3 2577.96   273.6 2574.47   279.3 2573.83   316.1 2573.61   333.1 2573.65
     349 2574.75   361.4 2576.62   369.9 2578.47     385 2584.03   399.3 2584.57
   409.1 2586.57   420.9 2586.99   427.1 2588.67   443.6 2590.93     469 2597.02
#Mann= 4 ,-1,0
       0      .1       0   279.3    .045       0   333.1     .06       0
     460      .1       0
Bank Sta=279.3,333.1
XS Rating Curve= 0 ,0
Exp/Cntr(USF)=0,0
Exp/Cntr=0.3,0.1

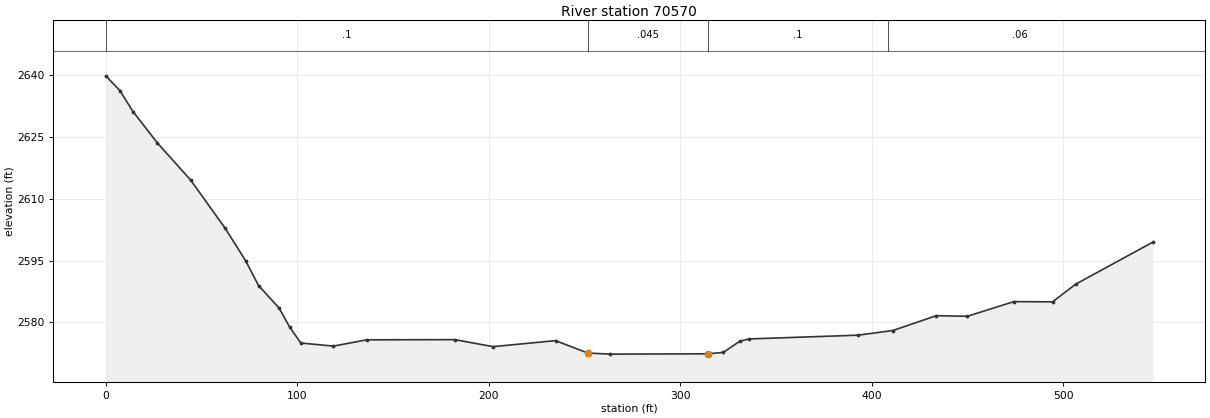
Type RM Length L Ch R = 1 ,70570   ,286,278.2,274.1
XS GIS Cut Line= 3
2355757.37061976698415.8640752892355999.69515752 698666.07384404
2356196.09771073698696.289621456
#Sta/Elev= 30
       0 2639.91     7.4 2636.31    14.2 2631.23      27 2623.56    44.3 2614.58
    62.3 2602.89      73 2594.99    79.8 2588.91    90.6  2583.4      96 2578.85
   101.9 2574.94   118.9 2574.19   136.3 2575.72   182.3 2575.76   202.3 2574.06
   234.9 2575.52   251.8  2572.5   263.5 2572.24   314.5 2572.32   322.6 2572.67
   331.1 2575.36   335.9 2575.93     393 2576.85   411.1 2577.98   433.8 2581.59
     450 2581.44   474.3 2585.01   494.5 2584.95   506.6 2589.25     547  2599.5
#Mann= 4 ,-1,0
       0      .1       0   251.8    .045       0   314.5      .1       0
  408.32     .06       0
Bank Sta=251.8,314.5
XS Rating Curve= 0 ,0
Exp/Cntr(USF)=0,0
Exp/Cntr=0.3,0.1