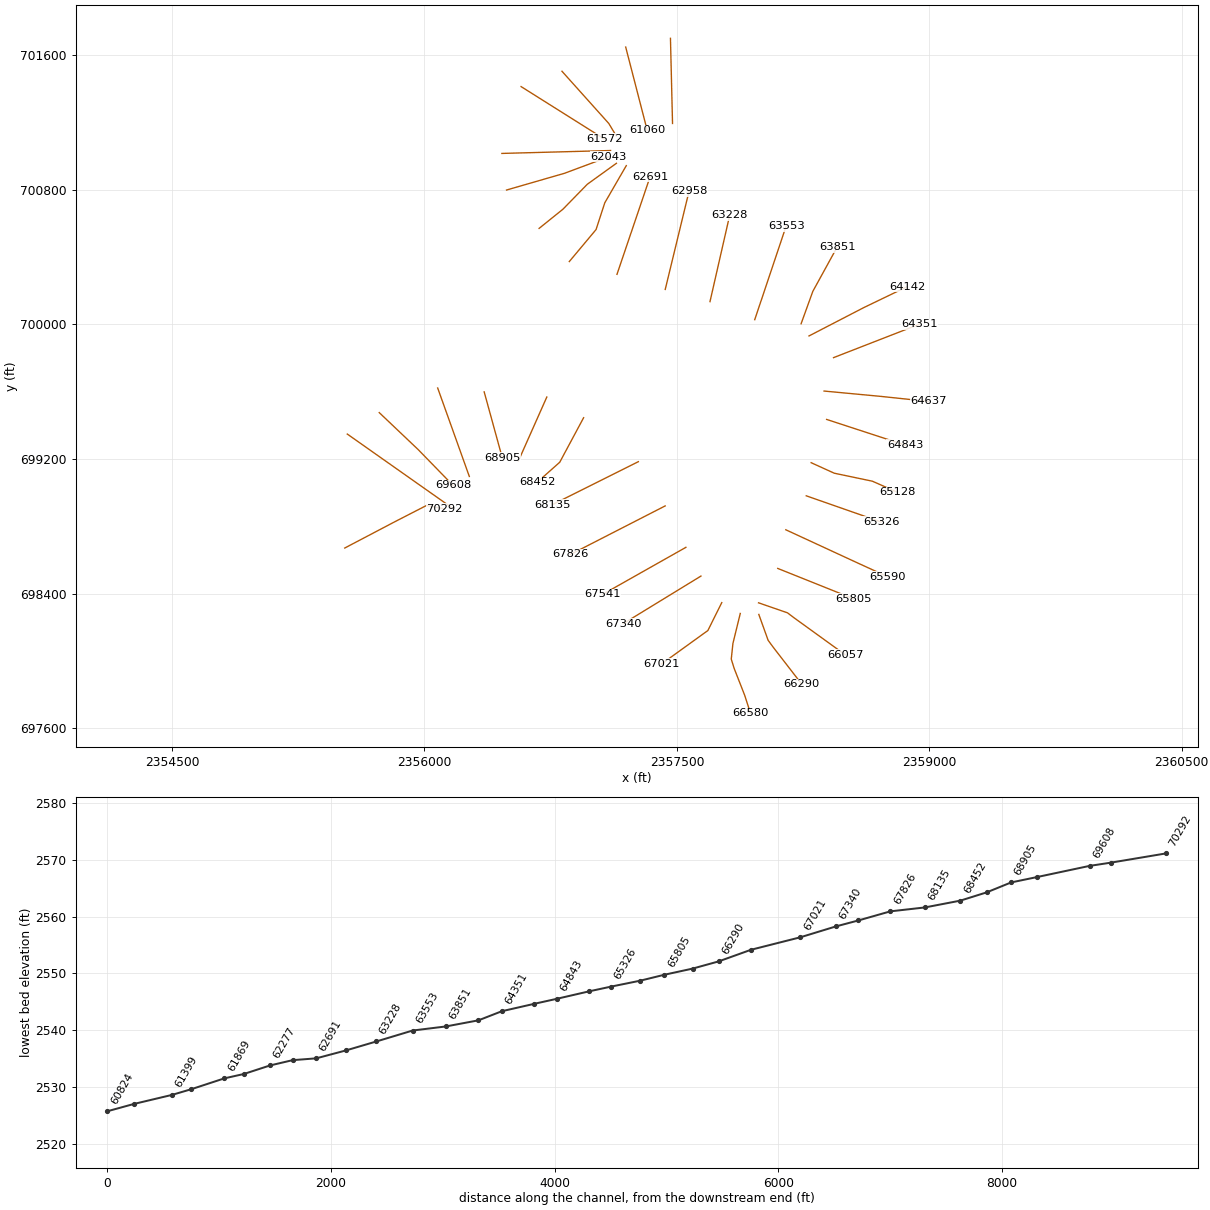
HEC-RAS study GLADYFK.prj: GLADYFK

--- GLADYFK.g01 (geometry) --- (continued)

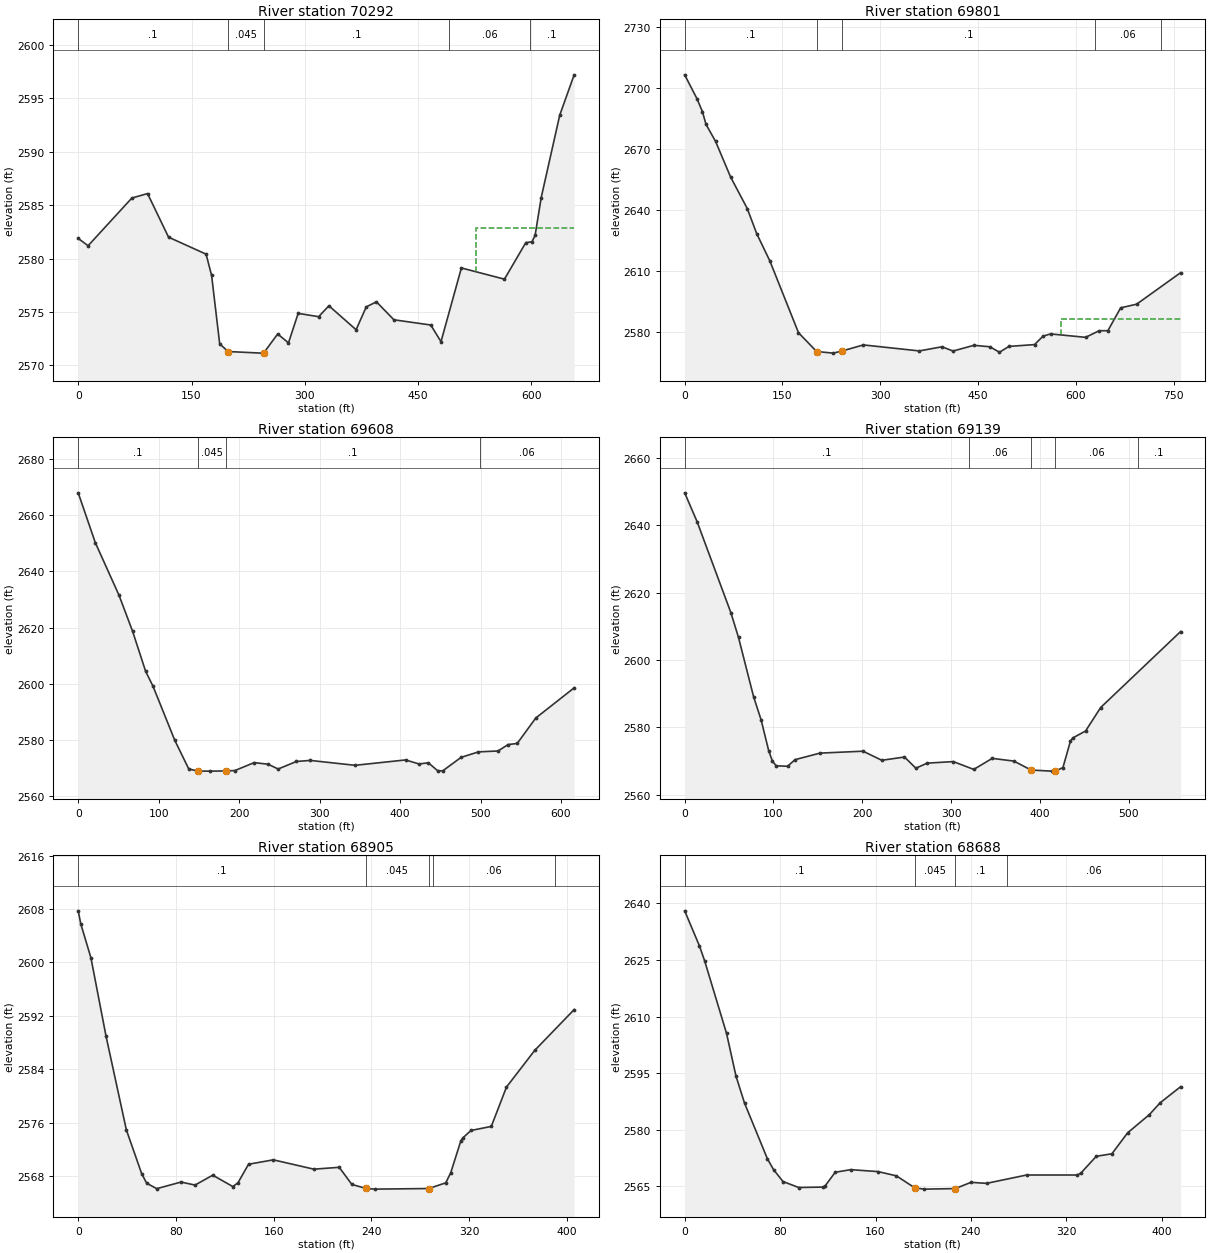
Type RM Length L Ch R = 1 ,70292   ,511.8,491.1,464.8
XS GIS Cut Line= 4
2355526.31464466698671.1098069432355828.47241882 698829.74263838
2356012.78279589698924.3286112812356118.93821788 698903.74994012
#Sta/Elev= 30
       0 2581.88    13.1  2581.2      71 2585.66    91.8 2586.08   119.6    2582
   169.3 2580.41   176.6 2578.42   187.3 2572.02   198.4  2571.3   242.9 2571.15
   245.8 2571.19   264.1 2572.94   278.4 2572.11   291.2 2574.87   318.3 2574.56
   331.9 2575.58   367.9 2573.34   381.4 2575.48   394.9 2575.95   417.9 2574.27
   466.8 2573.78   480.3 2572.22   507.3 2579.12   564.3 2578.07   592.6 2581.49
   600.8 2581.57   604.9 2582.17     613 2585.71   637.5 2593.41   656.6 2597.19
#Mann= 5 ,-1,0
       0      .1       0   198.4    .045       0   245.8      .1       0
  491.27     .06       0  598.43      .1       0
#XS Ineff= 2 , 0
                          526.29         2582.85
Permanent Ineff=
       F       F
Bank Sta=198.4,245.8
XS Rating Curve= 0 ,0
Exp/Cntr(USF)=0,0
Exp/Cntr=0.3,0.1

Type RM Length L Ch R = 1 ,69801   ,195,193,189.7
XS GIS Cut Line= 2
2355541.42253337699348.4468173652356163.36395186698910.318044824
#Sta/Elev= 30
       0 2706.27    18.7 2694.63    27.3 2688.11    32.7 2681.95    47.4 2673.56
    70.3 2656.16      96 2640.57   110.5 2628.23   130.6 2614.88   174.6 2579.56
   202.4 2570.32   227.9 2569.53   241.8 2570.62   274.2 2573.56   359.9 2570.61
   394.8 2572.65   411.7 2570.55   443.7 2573.37   468.2 2572.65   482.9 2569.97
   497.5 2572.83   536.7 2573.73   549.7 2577.85   561.2 2578.97     615 2577.29
   635.9 2580.54   649.2 2580.55   668.8 2591.78   693.3 2593.57   760.8 2609.06
#Mann= 5 ,-1,0
       0      .1       0   202.4    .045       0   241.8      .1       0
     630     .06       0     730      .1       0
#XS Ineff= 2 , 0
                           576.6         2586.53
Permanent Ineff=
       F       F
Bank Sta=202.4,241.8
XS Rating Curve= 0 ,0
Exp/Cntr(USF)=0,0
Exp/Cntr=0.3,0.1

Type RM Length L Ch R = 1 ,69608   ,470.4,468.3,448.7
XS GIS Cut Line= 3
 2355731.4265376 699475.802682452355962.98902866699255.835767545
2356170.15810441699043.036386382
#Sta/Elev= 30
       0 2667.98    21.2 2650.28    50.7 2631.54    67.5 2618.78    83.8 2604.46
    92.9  2599.2     120 2579.93   137.4 2569.72     149 2568.96   163.7 2568.95
   183.9    2569   194.8 2569.16   218.7 2571.98   236.1  2571.4   248.5  2569.7
   271.2 2572.38   288.4 2572.76     344 2571.02   406.8 2572.93   423.6  2571.5
   435.2 2571.92   446.6 2569.12     453 2569.04   475.9 2573.85   497.5  2575.8
   521.8 2576.12   534.3 2578.41   545.6 2578.79   568.7 2587.85   616.4 2598.58
#Mann= 4 ,-1,0
       0      .1       0     149    .045       0   183.9      .1       0
  499.38     .06       0
Bank Sta=149,183.9
XS Rating Curve= 0 ,0
Exp/Cntr(USF)=0,0
Exp/Cntr=0.3,0.1

Type RM Length L Ch R = 1 ,69139   ,238.4,234.1,231.6
XS GIS Cut Line= 2
2356078.55621811699622.2321100922356266.60848319699096.453328139
#Sta/Elev= 30
       0 2649.66    13.9 2641.14    52.1    2614    60.6  2606.7    77.6 2589.09
    86.1 2582.18    94.6 2573.06    98.8 2569.95   103.1 2568.58   115.8 2568.43
   124.3  2570.4   152.3 2572.34   200.8 2572.91     222 2570.21   247.5 2571.18
   260.3 2567.86     273 2569.36   302.5 2569.82   325.5  2567.5   346.3 2570.78
   370.7 2569.97   390.1 2567.31   413.2 2566.99   417.4    2567   425.9 2568.05
   434.4 2575.96     437 2576.85   451.4 2578.91   468.4 2585.89   558.4 2608.46
#Mann= 5 ,-1,0
       0      .1       0     320     .06       0   390.1    .045       0
   417.4     .06       0     510      .1       0
Bank Sta=390.1,417.4
XS Rating Curve= 0 ,0
Exp/Cntr(USF)=0,0
Exp/Cntr=0.3,0.1

Type RM Length L Ch R = 1 ,68905   ,237.1,217.3,212.4
XS GIS Cut Line= 2
2356354.87791373699599.2053021242356462.33635092699207.749566655
#Sta/Elev= 30
       0 2607.74     2.1 2605.78    10.4  2600.7    22.8 2588.93    39.4 2574.91
    51.9 2568.37      56 2566.92    64.3  2566.1    84.1 2567.09    95.6 2566.64
   110.1 2568.12   126.5 2566.42   130.7 2566.96   139.4 2569.76   159.7 2570.42
   192.9 2569.02   213.6  2569.3     224 2566.73   235.5 2566.14   242.7 2566.03
   286.9 2566.12   300.8 2566.97   304.9 2568.49   313.2 2573.29   315.1 2573.76
   321.5 2574.82   338.1 2575.43   350.5 2581.32   373.7 2586.84   405.9 2592.94
#Mann= 5 ,-1,0
       0      .1       0   235.5    .045       0   286.9      .1       0
     290     .06       0     390      .1       0
Bank Sta=235.5,286.9
XS Rating Curve= 0 ,0
Exp/Cntr(USF)=0,0
Exp/Cntr=0.3,0.1

Type RM Length L Ch R = 1 ,68688   ,236.9,235.6,234.7
XS GIS Cut Line= 2
2356727.14464256699568.5028914992356558.28138413699188.560560014
#Sta/Elev= 30
       0 2638.05    12.4 2628.74    16.8 2624.73    35.1 2605.56      43 2594.26
    50.2 2587.08    69.3 2572.37    74.5 2569.46    82.4 2566.31    95.6 2564.72
   115.6 2564.83   117.4    2565   126.2 2568.76   139.3 2569.45   162.3 2568.93
   177.5 2567.81   192.7 2564.67   200.6 2564.29   226.9 2564.43     240 2566.09
   253.1 2565.82   286.6 2568.03     329 2568.03   332.1 2568.52   345.1 2572.99
   358.2 2573.66   371.3 2579.19   389.6 2584.04   398.7 2587.19   415.8 2591.44
#Mann= 4 ,-1,0
       0      .1       0   192.7    .045       0   226.9      .1       0
     270     .06       0
Bank Sta=192.7,226.9
XS Rating Curve= 0 ,0
Exp/Cntr(USF)=0,0
Exp/Cntr=0.3,0.1

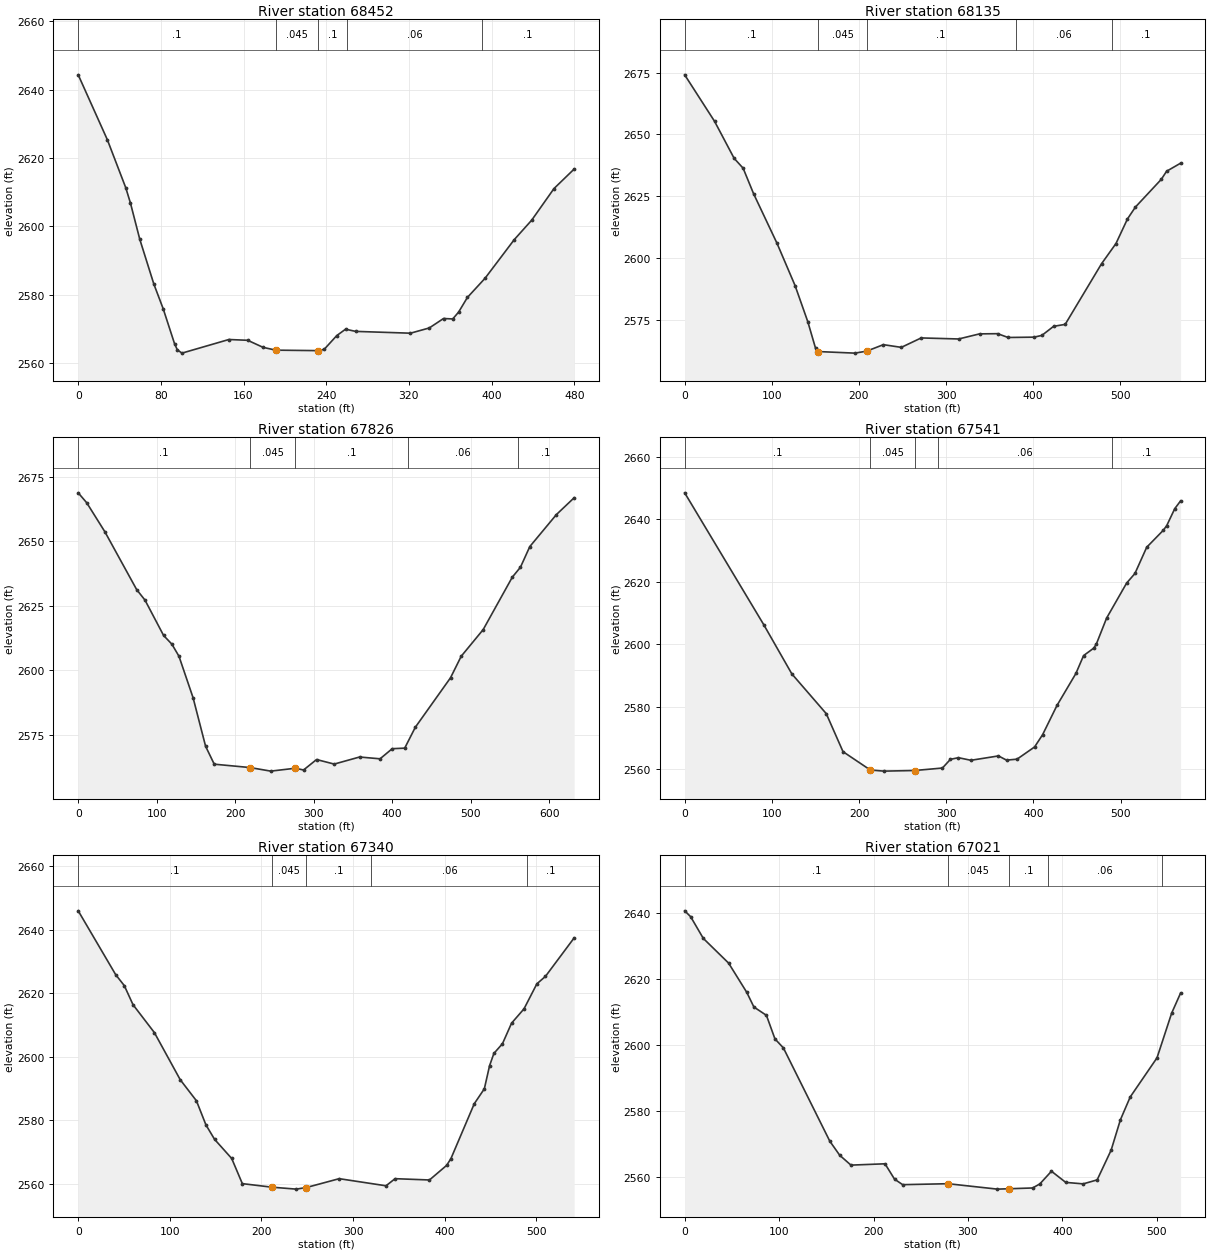
Type RM Length L Ch R = 1 ,68452   ,337.7,317.2,303.3
XS GIS Cut Line= 3
2356945.89931827699445.6932489992356803.90066913699180.884957358
2356669.57762264699061.913116186
#Sta/Elev= 30
       0 2644.35    28.2 2625.33      46 2611.28    50.5 2606.84    59.6 2596.15
    73.2 2583.05    82.3 2575.76    93.2 2565.61    95.9  2563.8   100.4 2562.83
   145.8 2566.82     164 2566.59   178.9 2564.52   191.2  2563.7   232.1 2563.56
     238 2563.93   250.2 2567.97   258.7 2569.84   268.4  2569.2   321.5 2568.67
   339.7  2570.2   353.5 2572.97   362.4 2572.84   368.1 2574.85   376.6 2579.14
   393.6 2584.73   421.9 2596.06   438.8 2601.77   460.4 2611.04   479.9 2616.75
#Mann= 5 ,-1,0
       0      .1       0   191.2    .045       0   232.1      .1       0
     260     .06       0  390.48      .1       0
Bank Sta=191.2,232.1
XS Rating Curve= 0 ,0
Exp/Cntr(USF)=0,0
Exp/Cntr=0.3,0.1

Type RM Length L Ch R = 1 ,68135   ,311.6,309.4,312.6
XS GIS Cut Line= 2
2357270.96768194699184.3975085512356761.77587733698929.801606244
#Sta/Elev= 30
       0  2674.1    34.3 2655.31    56.8 2640.34    67.1 2636.36    79.1 2626.05
     106 2606.01   126.7 2588.95   141.4 2574.26   150.3 2563.51   153.6 2562.26
   195.3 2561.63   208.8 2562.42   228.1 2565.05   248.7 2563.96   271.5 2567.77
   314.5 2567.35   338.5 2569.41   359.3 2569.49   371.2 2567.95   401.1 2568.09
     410 2568.79   423.5 2572.46   436.8 2573.25   478.5 2597.74   495.1 2605.93
   508.3 2615.87   517.4 2620.65   547.1 2631.86   553.2 2635.13   569.3  2638.4
#Mann= 5 ,-1,0
       0      .1       0   153.6    .045       0   208.8      .1       0
     380     .06       0     490      .1       0
Bank Sta=153.6,208.8
XS Rating Curve= 0 ,0
Exp/Cntr(USF)=0,0
Exp/Cntr=0.3,0.1

Type RM Length L Ch R = 1 ,67826   ,284,285.1,286.2
XS GIS Cut Line= 2
2357430.43984053 698921.408334742356868.09064972698633.239346415
#Sta/Elev= 30
       0 2668.74    10.8 2664.91      34 2653.64    74.5 2631.24    85.1 2627.18
   108.8 2613.49   119.4  2610.1   128.4 2605.42   146.4 2589.32   162.3 2570.58
   173.3 2563.63   218.8 2562.33   245.3 2560.94   276.7 2562.06   287.1 2561.38
   303.7 2565.43   326.2 2563.67   358.5 2566.41   384.6 2565.71   400.1 2569.63
     416 2569.84   429.5 2577.92   474.4 2597.11     488 2605.44     516 2615.77
   553.1 2636.07   563.5 2639.93   575.4 2647.92   609.3 2660.32   631.9 2666.83
#Mann= 5 ,-1,0
       0      .1       0   218.8    .045       0   276.7      .1       0
     420     .06       0     560      .1       0
Bank Sta=218.8,276.7
XS Rating Curve= 0 ,0
Exp/Cntr(USF)=0,0
Exp/Cntr=0.3,0.1

Type RM Length L Ch R = 1 ,67541   ,200.1,200.9,201.6
XS GIS Cut Line= 2
2357553.54115593698675.2057039382357058.33813716698395.429987117
#Sta/Elev= 30
       0 2648.45    90.6 2606.27   122.9 2590.48   162.4 2577.74   181.6 2565.57
   212.9  2559.7   228.5 2559.34   263.8 2559.54   295.6 2560.33   304.8 2563.12
     314 2563.64   328.3 2562.81   359.9 2564.21   369.1 2562.86   381.2 2563.17
   401.3 2567.08   410.5    2571     427 2580.37   448.7 2590.61   457.5 2596.33
   469.3 2598.75   472.2 2600.07   483.9 2608.33   506.9 2619.56   516.4 2622.62
   529.9 2631.02     549 2636.48   552.9 2637.97   562.1 2643.39   568.8 2645.88
#Mann= 5 ,-1,0
       0      .1       0   212.9    .045       0   263.8      .1       0
     290     .06       0     490      .1       0
Bank Sta=212.9,263.8
XS Rating Curve= 0 ,0
Exp/Cntr(USF)=0,0
Exp/Cntr=0.3,0.1

Type RM Length L Ch R = 1 ,67340   ,307.6,319,317.4
XS GIS Cut Line= 2
2357643.06938531698504.5425166772357181.43945256698221.969042689
#Sta/Elev= 30
       0 2645.91    40.9 2625.81    50.3 2622.36    59.8 2616.36    83.1 2607.58
   111.3 2592.75     129 2586.11   139.4  2578.5   148.8 2573.97   167.5 2567.94
   179.1 2560.02   211.1 2558.91   237.9 2558.29   248.9 2558.79   284.8 2561.58
   335.9 2559.34   345.8 2561.58   383.3 2561.17     402 2565.76   406.7 2567.88
   432.2 2585.18   443.2 2589.88   448.9 2597.15   453.6 2601.01     463 2604.09
   472.9 2610.54   486.5 2615.06   500.5 2622.92   509.9 2625.28   541.2 2637.39
#Mann= 5 ,-1,0
       0      .1       0   211.1    .045       0   248.9      .1       0
     320     .06       0     490      .1       0
Bank Sta=211.1,248.9
XS Rating Curve= 0 ,0
Exp/Cntr(USF)=0,0
Exp/Cntr=0.3,0.1

Type RM Length L Ch R = 1 ,67021   ,400,441.3,479.3
XS GIS Cut Line= 3
  2357766.746688698346.7912376172357684.17707366698180.936451278
2357408.48711777 697981.93791351
#Sta/Elev= 30
       0 2640.64     6.3 2638.87    19.7  2632.3    46.5 2624.82    65.8 2615.94
    73.3 2611.52    86.6 2608.99    95.6 2601.87   104.6 2599.11   153.7  2570.9
   164.2 2566.63   176.1 2563.64   212.2 2564.04   222.3 2559.38   230.9 2557.72
     279 2558.01   331.2 2556.37   343.1 2556.48   368.5 2556.72   376.2 2557.95
   388.5 2561.79   403.6 2558.41   422.1 2557.96   436.9 2559.17   451.7 2568.17
   461.5 2577.35   471.9 2584.27   500.3 2596.13   515.8 2609.65   525.3 2615.76
#Mann= 5 ,-1,0
       0      .1       0     279    .045       0   343.1      .1       0
  385.27     .06       0  505.27      .1       0
Bank Sta=279,343.1
XS Rating Curve= 0 ,0
Exp/Cntr(USF)=0,0
Exp/Cntr=0.3,0.1

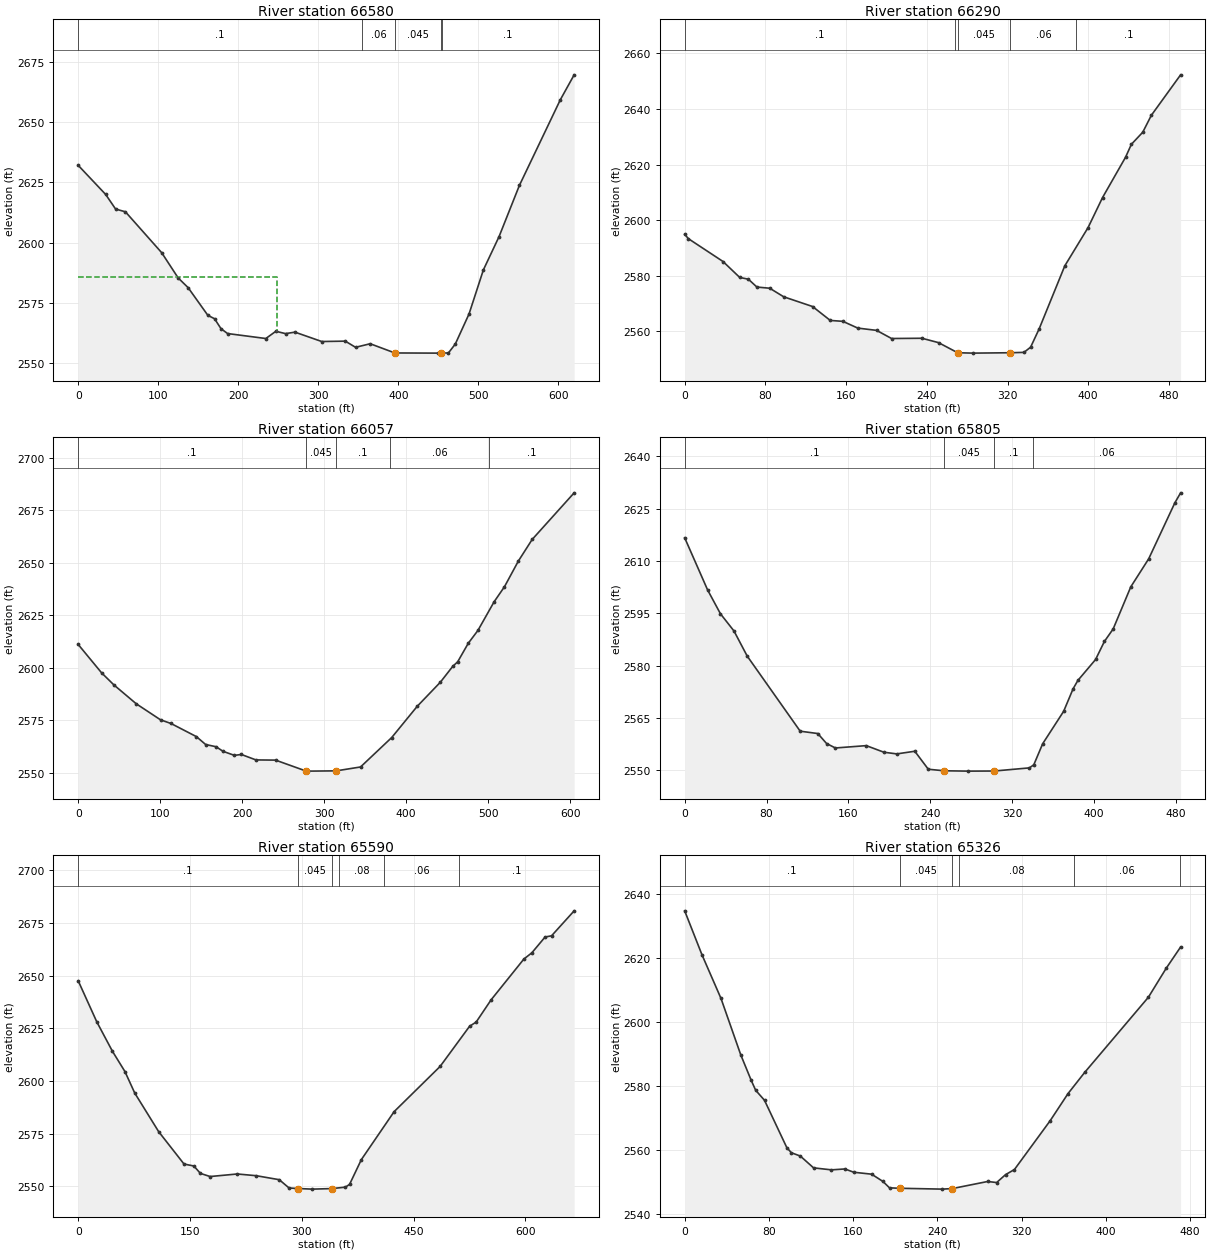
Type RM Length L Ch R = 1 ,66580   ,285.1,289.5,299.5
XS GIS Cut Line= 6
2357876.70765945698282.5087722052357833.01416437698103.937993868
 2357823.1765303698010.9276353552357840.24611279697956.175651552
2357902.77546907697796.5344857562357937.68965532697688.618847806
#Sta/Elev= 30
       0 2632.03    34.3 2619.97    46.7 2613.92      59 2612.77   104.3 2595.81
   124.9 2585.34   137.3 2581.33     162 2569.83   170.3 2568.44   178.4 2564.31
   186.6 2562.29   234.4 2560.23   246.9 2563.23     259 2562.26   270.8 2562.87
   304.3 2558.98   333.7 2559.14   346.5 2556.58   364.8 2558.06   395.6 2554.24
   449.6 2554.17   453.1 2554.19   462.5 2554.24   471.1 2557.93   488.3 2570.43
   506.2 2588.69   525.8  2602.5   551.2 2623.72   602.4 2659.28   619.6 2669.57
#Mann= 5 ,-1,0
       0      .1       0  354.72     .06       0   395.6    .045       0
   453.1     .06       0  454.72      .1       0
#XS Ineff= 2 , 0
           248.9 2585.73
Permanent Ineff=
       F       F
Bank Sta=395.6,453.1
XS Rating Curve= 0 ,0
Exp/Cntr=0.3,0.1

Type RM Length L Ch R = 1 ,66290   ,230.5,233.2,246.2
XS GIS Cut Line= 4
2357986.90854899698276.5089325772358042.28747103698122.718931644
2358074.79608498 698078.549550092358242.04041298697862.355662674
#Sta/Elev= 30
       0  2594.9     3.7 2593.31      38  2585.1    54.6 2579.35    63.1 2578.74
    71.6  2575.9    84.3 2575.48    98.2 2572.39   126.8 2568.89   144.3 2563.89
   156.8 2563.56   171.6 2561.13   190.2 2560.31   205.1 2557.38   235.2 2557.47
   251.6  2555.9   270.6 2552.26   285.9 2552.12   322.9 2552.26   336.3 2552.39
   342.9 2554.26   351.3 2560.79   376.8 2583.54   399.9 2597.33   414.2 2608.11
     437 2622.62   442.8 2627.28   454.1 2631.65   462.6 2637.73   491.6 2652.29
#Mann= 5 ,-1,0
       0      .1       0   268.3     .06       0   270.6    .045       0
   322.9     .06       0   388.3      .1       0
Bank Sta=270.6,322.9
XS Rating Curve= 0 ,0
Exp/Cntr(USF)=0,0
Exp/Cntr=0.3,0.1

Type RM Length L Ch R = 1 ,66057   ,248.6,252.1,258.2
XS GIS Cut Line= 4
2357985.28384708698345.6125298852358157.27855801698286.128432286
2358195.85017512698256.8865538542358499.30018068698037.547683805
#Sta/Elev= 30
       0 2611.17    28.5 2597.67    43.5 2591.92    70.8 2582.92   100.4 2575.28
   113.1 2573.55   144.1 2567.29   155.4 2563.53   168.1 2562.47   176.6 2560.29
   190.4 2558.36     199 2558.78   216.7 2556.19   240.7 2556.09   277.7 2550.91
   280.1 2550.85   314.7 2550.98   344.3 2552.83   382.3 2566.84   413.4 2581.71
   441.6 2593.18   456.7 2600.73   462.8 2602.94   475.7 2611.76   487.4 2617.83
   507.2 2631.51   519.8 2638.66   536.8 2650.93   553.6 2661.19   604.8  2683.4
#Mann= 5 ,-1,0
       0      .1       0   277.7    .045       0   314.7      .1       0
  380.39     .06       0  500.39      .1       0
Bank Sta=277.7,314.7
XS Rating Curve= 0 ,0
Exp/Cntr=0.3,0.1

Type RM Length L Ch R = 1 ,65805   ,215.8,214.6,213.4
XS GIS Cut Line= 2
2358099.41248235 698549.984588072358549.33896707698369.725570946
#Sta/Elev= 30
       0 2616.68    22.4 2601.73      35 2594.87    48.2 2589.95    61.1 2582.76
   112.9 2561.22   130.1 2560.55   138.7 2557.68   147.3 2556.41   177.5 2557.08
   194.7 2555.19   207.3 2554.71   224.9 2555.47   238.1 2550.31   253.5 2549.87
   276.6 2549.77   302.5  2549.8   336.9  2550.7   341.2 2551.59   349.9 2557.63
   370.4 2566.93   379.6 2573.37   384.3 2575.78   401.6 2581.78   410.2 2586.95
   418.8 2590.55     436 2602.61   453.5 2610.65   479.1 2626.72   484.7 2629.57
#Mann= 4 ,-1,0
       0      .1       0   253.5    .045       0   302.5      .1       0
     340     .06       0
Bank Sta=253.5,302.5
XS Rating Curve= 0 ,0
Exp/Cntr(USF)=0,0
Exp/Cntr=0.3,0.1

Type RM Length L Ch R = 1 ,65590   ,262.9,264.3,266.7
XS GIS Cut Line= 3
2358147.26071094698779.6703943872358575.12024322698581.937655317
  2358751.731836698501.097904098
#Sta/Elev= 30
       0 2647.61      25 2628.09    45.9 2614.19    62.7 2604.55    75.9 2594.32
     108    2576     142 2560.64   155.2 2559.71     164  2556.2     177 2554.71
   213.5 2555.92     239  2555.1   269.8 2553.21     283 2549.27   294.9 2549.02
   313.9 2548.73   340.9 2548.99   358.7 2549.68   364.2    2551     380 2562.74
     424 2585.52   485.7 2606.97   525.3 2626.06   534.1 2628.04   554.2 2638.62
   598.1 2657.94   608.9 2660.94   626.6 2668.41   635.3 2668.99   665.6 2680.84
#Mann= 6 ,-1,0
       0      .1       0   294.9    .045       0   340.9      .1       0
     350     .08       0     410     .06       0  511.34      .1       0
Bank Sta=294.9,340.9
XS Rating Curve= 0 ,0
Exp/Cntr=0.3,0.1

Type RM Length L Ch R = 1 ,65326   ,192.2,197.8,198.7
XS GIS Cut Line= 2
2358268.58460041698981.4883726982358713.11712825698826.057418909
#Sta/Elev= 30
       0 2634.76    16.5 2620.94    34.5 2607.33    53.3 2589.65    63.1 2581.77
    67.4 2578.61    75.8 2575.47      97 2560.64   101.3 2559.06   109.8 2558.02
   122.4 2554.32   139.4  2553.7   152.1 2553.98   160.6 2552.95   177.5 2552.35
   188.3 2550.06   194.5 2548.07     204 2547.94   244.8 2547.67   254.2 2547.85
   287.7 2550.06   296.2 2549.73   304.7 2552.21   313.1  2553.8     347 2569.06
     364 2577.57   379.8 2584.19   440.3 2607.72   457.2 2616.78   470.9 2623.44
#Mann= 6 ,-1,0
       0      .1       0     204    .045       0   254.2      .1       0
     260     .08       0     370     .06       0     470      .1       0
Bank Sta=204,254.2
XS Rating Curve= 0 ,0
Exp/Cntr(USF)=0,0
Exp/Cntr=0.3,0.1

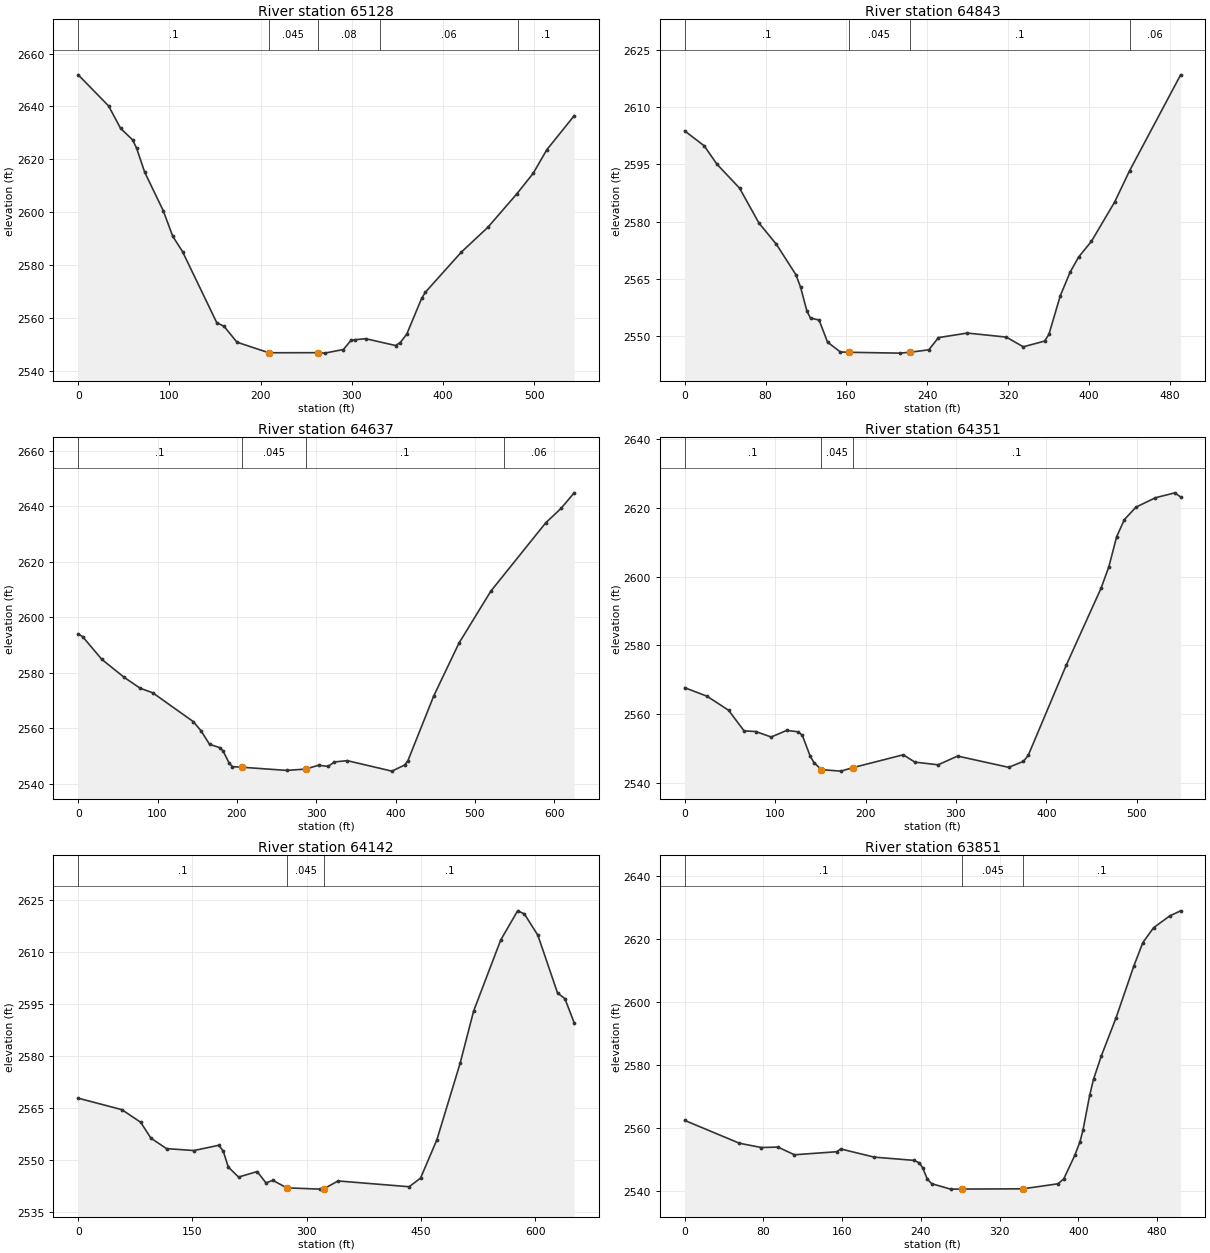
Type RM Length L Ch R = 1 ,65128   ,286.2,285.3,279.6
XS GIS Cut Line= 4
2358297.82505975699178.3006394672358435.06945849699115.818528709
2358661.33504218699068.4190190832358809.57512077699003.081426261
#Sta/Elev= 30
       0 2651.96    33.3 2640.23    46.5 2631.72    59.7 2627.39    64.1 2624.21
    72.9  2615.2    93.2  2600.7   103.7 2590.97   114.4  2585.2   151.9 2558.39
   160.1 2556.91   174.2 2550.95   209.1 2546.97   262.6    2547   270.4 2546.83
   290.9  2548.2   299.1 2551.62   303.1 2551.88   315.4 2552.28   348.1 2549.71
   353.3 2550.84   360.4 2554.02   376.7 2567.52   380.8 2569.83     420  2584.9
   449.5 2594.42   481.2 2607.03   499.1 2614.78     514 2623.65     544  2636.5
#Mann= 5 ,-1,0
       0      .1       0   209.1    .045       0   262.6     .08       0
   330.8     .06       0  481.98      .1       0
Bank Sta=209.1,262.6
XS Rating Curve= 0 ,0
Exp/Cntr=0.3,0.1

Type RM Length L Ch R = 1 ,64843   ,203.1,205.7,219
XS GIS Cut Line= 2
2358389.82074437699435.3467577622358856.11360573699283.024423049
#Sta/Elev= 30
       0 2603.78    19.3 2599.88    31.9 2595.06    54.3 2588.77    73.4 2579.65
    90.8 2574.03     110 2566.09   114.6 2562.85   120.9 2556.54   124.5 2554.68
   132.9 2554.23   141.3 2548.41     154 2545.84   162.4 2545.75   212.8 2545.53
   222.4 2545.74   241.5 2546.41     251  2549.6   279.5 2550.79   318.1 2549.73
   334.9 2547.19   355.9 2548.68   360.2 2550.42   371.5 2560.58   381.2 2566.74
   389.6 2570.71   402.2  2574.8   425.3 2585.16   440.1 2593.38   490.5 2618.48
#Mann= 4 ,-1,0
       0      .1       0   162.4    .045       0   222.4      .1       0
     440     .06       0
Bank Sta=162.4,222.4
XS Rating Curve= 0 ,0
Exp/Cntr(USF)=0,0
Exp/Cntr=0.3,0.1

Type RM Length L Ch R = 1 ,64637   ,280.4,286.5,303.8
XS GIS Cut Line= 3
2358374.61720078699603.9681854862358709.85907257699572.483148389
2358996.63829678699542.199055646
#Sta/Elev= 30
       0 2594.02     5.6 2593.03    29.7 2584.88    57.8 2578.42    77.9  2574.5
      94 2572.81     145 2562.46   154.6 2559.21   165.6 2554.27   178.3  2553.1
   182.4 2551.99   190.4 2547.46   194.4 2546.25     206 2546.04   262.7 2544.89
   286.8 2545.37   286.8 2545.38   302.9 2546.75   314.9 2546.33     323 2547.93
     339  2548.4   395.4 2544.63   411.4 2546.82   415.5 2548.35     448 2571.62
   479.8 2590.64     520 2609.38   589.2 2633.99   608.5 2639.17   625.1  2644.8
#Mann= 4 ,-1,0
       0      .1       0     206    .045       0   286.8      .1       0
  536.72     .06       0
Bank Sta=206,286.8
XS Rating Curve= 0 ,0
Exp/Cntr=0.3,0.1

Type RM Length L Ch R = 1 ,64351   ,206.9,208.2,214.8
XS GIS Cut Line= 2
2358430.95498783699802.4947380252358942.10522246700001.415272684
#Sta/Elev= 30
       0 2567.65    24.6 2565.18    48.5 2561.09    65.7 2555.06    78.6 2554.88
    95.7 2553.28   112.9 2555.21   125.8 2554.78   130.1 2553.77   138.7 2547.79
     143 2545.82   151.3 2543.76   172.8 2543.34   185.9 2544.35   241.7  2548.1
   254.6 2545.97   280.3 2545.18   301.8 2547.73   358.3 2544.45   374.7 2546.19
     380 2547.96   421.9 2574.15   460.6 2596.69   469.2 2602.94   477.7  2611.6
   486.3 2616.63   499.2 2620.27   520.7 2622.99   542.1 2624.42   548.5 2623.21
#Mann= 3 ,-1,0
       0      .1       0   151.3    .045       0   185.9      .1       0
Bank Sta=151.3,185.9
XS Rating Curve= 0 ,0
Exp/Cntr(USF)=0,0
Exp/Cntr=0.3,0.1

Type RM Length L Ch R = 1 ,64142   ,279.3,291.7,311.9
XS GIS Cut Line= 3
2358285.24788708699931.4826475762358611.74442499700100.397814514
 2358867.0024097700223.405531408
#Sta/Elev= 30
       0 2567.97    57.3 2564.66      82 2561.03    95.4 2556.45   115.9 2553.43
   151.9 2552.87   184.5 2554.39   190.4  2552.7     197  2548.1   210.5 2545.22
   234.9 2546.81   246.5 2543.53   255.5 2544.28   273.5 2542.13   273.5 2542.12
   317.1 2541.74   323.1 2541.91   341.1  2544.1   434.4 2542.43   449.4 2544.93
   470.8 2555.98   501.3 2578.03     519 2593.08   554.6  2613.6   576.8 2622.01
   585.7 2621.12   603.4 2614.95   629.2 2598.31   638.9 2596.67     651 2589.74
#Mann= 3 ,-1,0
       0      .1       0   273.5    .045       0   323.1      .1       0
Bank Sta=273.5,323.1
XS Rating Curve= 0 ,0
Exp/Cntr=0.3,0.1

Type RM Length L Ch R = 1 ,63851   ,292.8,297.4,302.1
XS GIS Cut Line= 3
2358238.22248603700004.0706177892358307.91430599700196.540017919
2358451.94113435700458.786910856
#Sta/Elev= 30
       0 2562.47    55.5 2555.23    77.8 2553.86    94.8    2554   111.5 2551.56
   154.3 2552.52   158.6  2553.4   192.6 2550.81   232.8 2549.79   238.5    2549
   241.9 2547.35   246.6  2543.8   251.1 2542.37   270.2 2540.66     282 2540.68
   343.8 2540.76   379.2 2542.35   385.1 2543.88   396.4 2551.39   401.7 2555.74
   404.7  2559.4   411.6 2570.57   415.4  2575.5   423.3 2582.89   438.1 2594.84
   456.4 2611.48   465.5 2618.86   476.4 2623.59   492.9 2627.35   503.9 2628.95
#Mann= 3 ,-1,0
       0      .1       0     282    .045       0   343.8      .1       0
Bank Sta=282,343.8
XS Rating Curve= 0 ,0
Exp/Cntr(USF)=0,0
Exp/Cntr=0.3,0.1

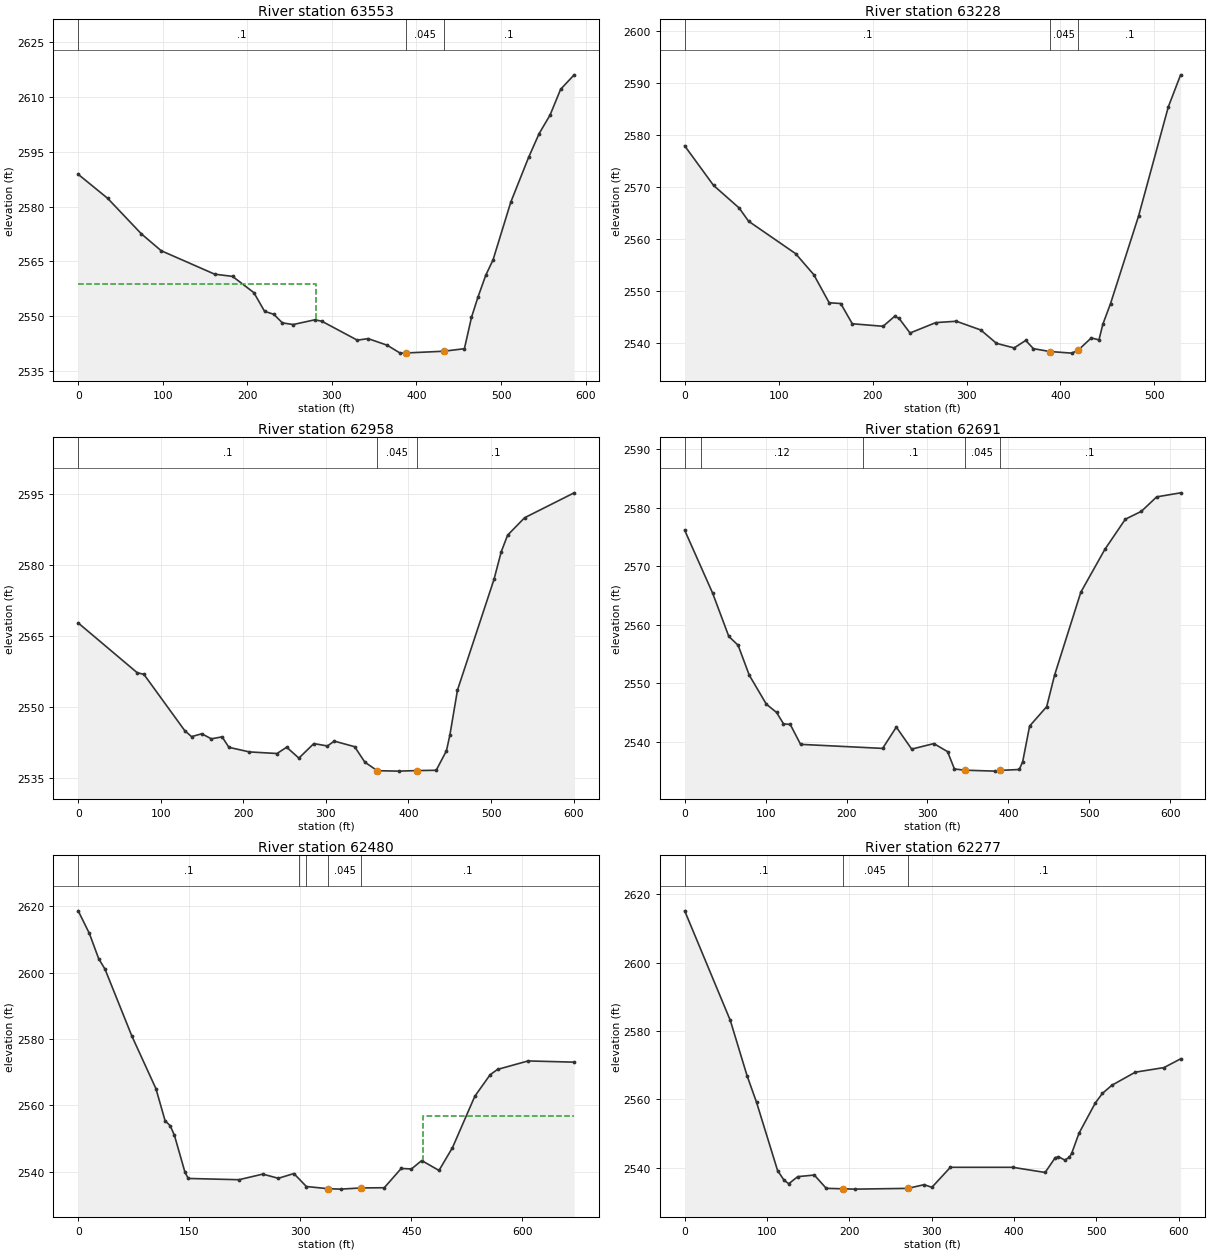
Type RM Length L Ch R = 1 ,63553   ,325.3,325,327.7
XS GIS Cut Line= 2
 2357962.6674027700028.1798596312358149.18454725700584.277272076
#Sta/Elev= 30
       0 2588.84    34.8 2582.28    74.6 2572.58    98.1 2567.95   161.4 2561.53
   182.5 2560.93   207.8 2556.47   220.4 2551.37   231.2 2550.57   241.5 2548.21
   254.2 2547.76   279.5 2549.04   287.9 2548.69   330.1 2543.48   342.8 2543.91
   365.3 2542.11   380.8 2539.94   387.4 2539.98   432.4 2540.46   456.7 2541.15
   465.1 2549.73   472.7 2555.23     482 2561.27   490.5 2565.39   511.6 2581.26
   532.6 2593.46   545.1 2599.99     558 2605.05   570.5  2612.1   586.5 2616.05
#Mann= 3 ,-1,0
       0      .1       0   387.4    .045       0   432.4      .1       0
#XS Ineff= 2 , 0
          280.84 2558.82
Permanent Ineff=
       F       F
Bank Sta=387.4,432.4
XS Rating Curve= 0 ,0
Exp/Cntr(USF)=0,0
Exp/Cntr=0.3,0.1

Type RM Length L Ch R = 1 ,63228   ,271.2,270.4,269.9
XS GIS Cut Line= 2
2357696.70777067700135.2545166862357814.14449131700649.903674787
#Sta/Elev= 30
       0 2577.88    30.7 2570.27      58 2565.92      68 2563.38   118.1 2557.14
   137.4 2553.11   153.8  2547.7   166.1 2547.55   178.4 2543.66   211.2 2543.17
   223.5 2545.09   228.3 2544.67   239.9 2541.88   267.3 2543.88   289.2 2544.14
   315.2 2542.46   331.9 2539.89   350.7 2539.01     363 2540.45   371.2 2538.87
   388.7 2538.32     412 2538.01   418.7 2538.56   432.8 2540.93     441 2540.56
   445.1 2543.56   453.3 2547.54   483.1 2564.35   514.8 2585.37   527.9 2591.53
#Mann= 3 ,-1,0
       0      .1       0   388.7    .045       0   418.7      .1       0
Bank Sta=388.7,418.7
XS Rating Curve= 0 ,0
Exp/Cntr(USF)=0,0
Exp/Cntr=0.3,0.1

Type RM Length L Ch R = 1 ,62958   ,269.1,266.5,265.3
XS GIS Cut Line= 2
2357430.74813863700207.7889617872357572.36300763700791.518543794
#Sta/Elev= 30
       0 2567.73    71.4 2557.23    79.6 2556.87     129    2545   137.3 2543.72
   149.6 2544.33   161.3 2543.26   174.3 2543.68   182.5 2541.47   207.2  2540.5
   240.8 2540.16   252.5 2541.49   267.3 2539.19   285.4 2542.26   301.9 2541.75
   310.1 2542.78   334.8  2541.6   347.2 2538.33   362.3 2536.53   388.3 2536.44
   409.8 2536.55   433.6 2536.62     446 2540.73   450.1 2543.99   459.4 2553.57
   503.6 2576.92   512.4 2582.77   520.1 2586.27   540.6 2589.94   600.7 2595.21
#Mann= 3 ,-1,0
       0      .1       0   362.3    .045       0   409.8      .1       0
Bank Sta=362.3,409.8
XS Rating Curve= 0 ,0
Exp/Cntr(USF)=0,0
Exp/Cntr=0.3,0.1

Type RM Length L Ch R = 1 ,62691   ,209.1,211.6,209.3
XS GIS Cut Line= 2
2357144.06437942700297.5935128652357340.94358755700877.869073677
#Sta/Elev= 30
       0 2576.16    34.5 2565.43    54.5 2558.04      66 2556.53    79.8 2551.42
   100.9 2546.47   113.6 2545.05   122.1 2543.12   130.5    2543   143.2 2539.61
   244.6 2538.92   261.5 2542.56   280.5  2538.8   307.9 2539.74   324.8 2538.37
   333.3 2535.41   345.9  2535.2   383.9 2535.04   389.1 2535.16   413.5 2535.32
   417.7 2536.68   426.2 2542.73   447.3 2546.04   457.1 2551.44   489.5 2565.58
   519.1 2572.87   544.5 2578.04   564.3 2579.38   583.2 2581.85   612.8 2582.54
#Mann= 5 ,-1,0
       0      .1       0      20     .12       0     220      .1       0
   345.9    .045       0   389.1      .1       0
Bank Sta=345.9,389.1
XS Rating Curve= 0 ,0
Exp/Cntr(USF)=0,0
Exp/Cntr=0.3,0.1

Type RM Length L Ch R = 1 ,62480   ,224.5,203.1,185.7
XS GIS Cut Line= 4
 2356860.8346414700373.5819791622357019.71961638700563.553144904
2357071.52993431700722.4381198882357199.32871854700943.495476388
#Sta/Elev= 30
       0 2618.69    15.1 2611.85    27.6 2604.28    36.2 2601.09    72.5  2580.9
     105 2565.04   117.4 2555.35   124.2 2553.87   129.9 2551.03   144.1 2539.93
   148.6 2537.94   217.2 2537.56   249.3 2539.25   270.4 2537.99   291.4 2539.42
   308.3 2535.51   337.7 2534.85   354.5 2534.72   382.6 2535.08   413.5 2535.14
   436.4 2540.95   450.3 2540.81   464.1 2543.34   487.5 2540.36   505.7 2547.24
   535.9 2562.75   556.6 2569.24   566.6 2570.84   607.9  2573.4   670.1 2573.03
#Mann= 5 ,-1,0
       0      .1       0  297.66     .12       0  307.66      .1       0
   337.7    .045       0   382.6      .1       0
#XS Ineff= 2 , 0
                          466.14         2556.81
Permanent Ineff=
       F       F
Bank Sta=337.7,382.6
XS Rating Curve= 0 ,0
Exp/Cntr(USF)=0,0
Exp/Cntr=0.3,0.1

Type RM Length L Ch R = 1 ,62277   ,238.1,233.3,229.8
XS GIS Cut Line= 4
2356681.22553924700570.4611872952356822.84040825 700684.44388674
2356967.90929845700832.9667981382357140.61035822700957.311561169
#Sta/Elev= 30
       0 2615.14    55.4  2583.1    75.7 2566.98    87.3 2559.13   112.8 2539.22
   120.7 2536.37   126.4 2535.37   137.3 2537.43   157.4  2537.9   171.9 2534.01
   191.7 2533.88   206.6 2533.78   270.9    2534   290.7 2535.08   300.2 2534.31
   322.6 2540.16   398.3 2540.16   437.7 2538.65   449.9 2542.96   453.8 2543.27
   461.4 2542.29   467.1 2543.04     470 2544.29   478.8 2550.12   498.6 2558.97
   507.2 2561.76   518.7 2564.14   547.2 2567.97     582 2569.31   602.2 2571.87
#Mann= 3 ,-1,0
       0      .1       0   191.7    .045       0   270.9      .1       0
Bank Sta=191.7,270.9
XS Rating Curve= 0 ,0
Exp/Cntr(USF)=0,0
Exp/Cntr=0.3,0.1

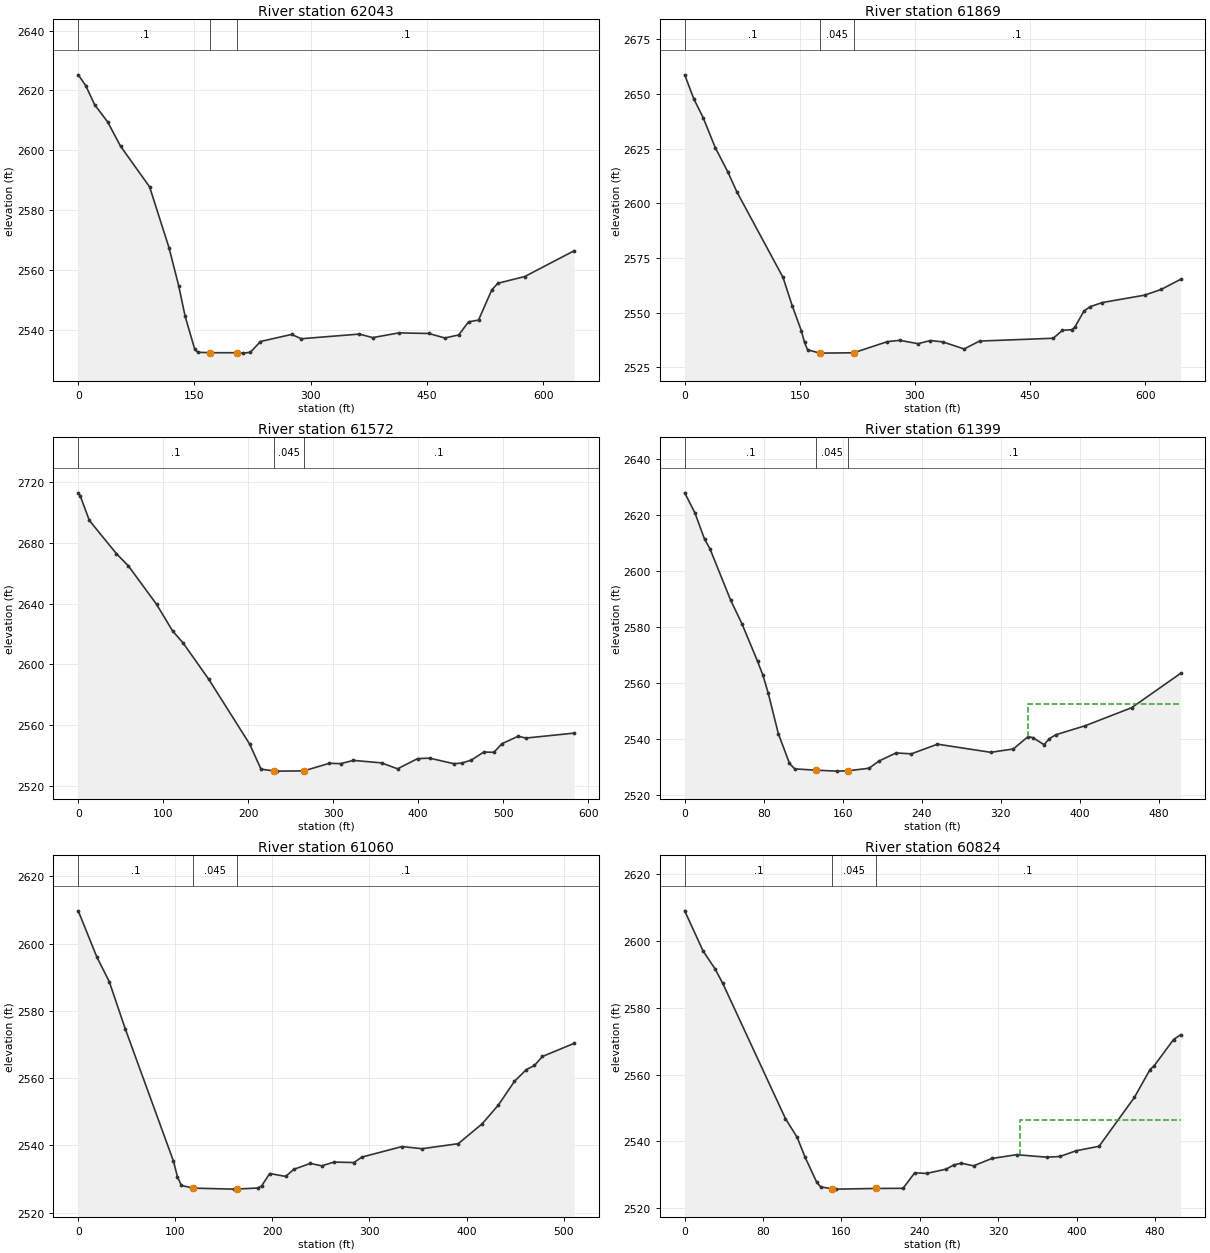
Type RM Length L Ch R = 1 ,62043   ,178.8,174.5,170.2
XS GIS Cut Line= 3
2356487.71057459700798.4981837962356832.65811979  700898.1166559
2357095.82930729700996.248285137
#Sta/Elev= 30
       0 2625.21     9.7 2621.61    21.3 2615.18      38 2609.49    54.6 2601.39
    92.1 2587.79   117.1 2567.53   129.6 2554.83   137.9 2544.63   150.4 2533.53
   154.5 2532.56   170.5 2532.42   204.5 2532.42   212.5 2532.28   222.2 2532.57
   235.1 2536.16   275.3 2538.52   287.8 2537.09   362.8 2538.64   379.9 2537.46
   413.9 2539.05   452.4 2538.84     473 2537.34   490.9 2538.35   503.7 2542.74
   516.5 2543.31   533.6 2553.39   541.4  2555.6   576.2 2557.86   639.9 2566.46
#Mann= 3 ,-1,0
       0      .1       0   170.5    .045       0   204.5      .1       0
Bank Sta=170.5,204.5
XS Rating Curve= 0 ,0
Exp/Cntr(USF)=0,0
Exp/Cntr=0.3,0.1

Type RM Length L Ch R = 1 ,61869   ,307.2,297.2,282.3
XS GIS Cut Line= 2
2356460.16818274 701016.029921492357106.07014627701033.300027466
#Sta/Elev= 30
       0 2658.72      12 2647.68      24 2639.19    39.9 2625.42    56.4 2614.21
      68 2605.22   128.1 2566.12   140.1 2553.17   152.1 2541.63   156.1 2536.42
   160.1 2533.04   176.1 2531.51   220.1 2531.67   264.1 2536.77   280.1 2537.36
   304.1 2535.83   320.1 2537.27     336 2536.66   364.1 2533.42   384.1 2537.02
   480.2 2538.31   492.2 2541.94   504.2 2542.21   508.2 2543.33   520.2 2550.75
   528.2 2552.74   544.2 2554.64   599.1    2558   620.8 2560.62   646.1 2565.24
#Mann= 3 ,-1,0
       0      .1       0   176.1    .045       0   220.1      .1       0
Bank Sta=176.1,220.1
XS Rating Curve= 0 ,0
Exp/Cntr(USF)=0,0
Exp/Cntr=0.3,0.1

Type RM Length L Ch R = 1 ,61572   ,179.2,172.4,169.6
XS GIS Cut Line= 2
2356574.15088219 701413.242358952357068.07591312701102.380451372
#Sta/Elev= 30
       0  2713.1     2.4 2711.07    13.1  2694.9      45 2672.96    59.1 2664.87
    92.2 2639.58   111.1 2622.01   123.3 2614.19   153.6 2590.17   201.7 2547.48
   215.1  2530.9   230.7 2529.68     234 2529.59   265.5 2529.74   295.4 2534.75
     309 2534.53   323.8 2536.67   356.9 2535.03   375.8 2531.12   399.4 2537.84
   413.4 2538.16   441.9  2534.5   451.4  2534.9   462.7 2536.88   477.2 2542.18
   489.2 2542.01   498.7 2547.69   517.6 2552.57     527 2551.41   583.6 2554.66
#Mann= 3 ,-1,0
       0      .1       0   230.7    .045       0   265.5      .1       0
Bank Sta=230.7,265.5
XS Rating Curve= 0 ,0
Exp/Cntr(USF)=0,0
Exp/Cntr=0.3,0.1

Type RM Length L Ch R = 1 ,61399   ,347.1,339.4,330.5
XS GIS Cut Line= 3
2356817.29568534701504.1510215962357095.27549389 701194.12289319
2357139.50624665701120.612982426
#Sta/Elev= 30
       0  2627.8    10.3 2620.72    20.1  2611.3    25.5 2607.93    46.6  2589.5
      58 2581.11    73.8 2567.75    79.2  2562.8    84.6 2556.42    94.8    2542
   106.1 2531.37   111.4 2529.39   132.9 2528.93   154.3 2528.59   165.2  2528.7
   186.7 2529.62   196.8  2532.2     214 2535.07   229.6 2534.76     256  2538.2
   309.9  2535.3   332.7 2536.48   347.8 2540.91   352.6 2540.51   363.9 2538.03
   369.3 2540.17   375.8 2541.56   405.8  2544.8   452.7 2551.22   502.2 2563.45
#Mann= 3 ,-1,0
       0      .1       0   132.9    .045       0   165.2      .1       0
#XS Ineff= 2 , 0
                          347.99         2552.56
Permanent Ineff=
       F       F
Bank Sta=132.9,165.2
XS Rating Curve= 0 ,0
Exp/Cntr(USF)=0,0
Exp/Cntr=0.3,0.1

Type RM Length L Ch R = 1 ,61060   ,241.1,236.3,230.9
XS GIS Cut Line= 2
2357195.87469735701648.1158002312357323.62041701701153.592988872
#Sta/Elev= 30
       0 2609.74    19.1 2596.08      32 2588.66    48.5 2574.62    98.1 2535.32
   102.2 2530.65   106.3 2528.08   118.7 2527.29     160    2527   163.5 2527.03
   184.8 2527.33   188.9 2527.94   197.2 2531.64   213.7 2530.78     222 2532.88
     239 2534.64   250.9 2533.93   263.3 2535.04     284 2534.91   292.2 2536.53
   333.5 2539.65   354.2 2539.02   391.4 2540.51   416.2 2546.46   432.8 2552.02
   449.3 2559.05   461.6 2562.54   469.9 2563.76   478.1 2566.44   510.8 2570.34
#Mann= 3 ,-1,0
       0      .1       0   118.7    .045       0   163.5      .1       0
Bank Sta=118.7,163.5
XS Rating Curve= 0 ,0
Exp/Cntr(USF)=0,0
Exp/Cntr=0.3,0.1

Type RM Length L Ch R = 1 ,60824   ,356.3,352.3,348.6
XS GIS Cut Line= 2
2357461.83432938701699.9261181612357474.16922923701194.001760533
#Sta/Elev= 30
       0 2608.96    18.8 2596.94    30.8 2591.69    38.8  2587.3   102.8 2546.84
   114.8 2541.21   122.8 2535.32   134.8 2527.75   138.8 2526.38   150.8 2525.82
   154.8 2525.72   194.8 2525.92   222.8 2525.96   234.8 2530.61   246.8 2530.41
   266.7 2531.69   274.8 2532.97   282.3 2533.48   294.8 2532.69   313.5 2534.89
   338.8 2536.02   369.5 2535.27   382.9 2535.48   399.5  2537.2   422.9 2538.54
   458.9 2553.13   474.9  2561.5   478.9 2562.54   498.9 2570.47   506.1 2571.88
#Mann= 3 ,-1,0
       0      .1       0   150.8    .045       0   194.8      .1       0
#XS Ineff= 2 , 0
                          342.23         2546.26
Permanent Ineff=
       F       F
Bank Sta=150.8,194.8
XS Rating Curve= 0 ,0
Exp/Cntr(USF)=0,0
Exp/Cntr=0.3,0.1