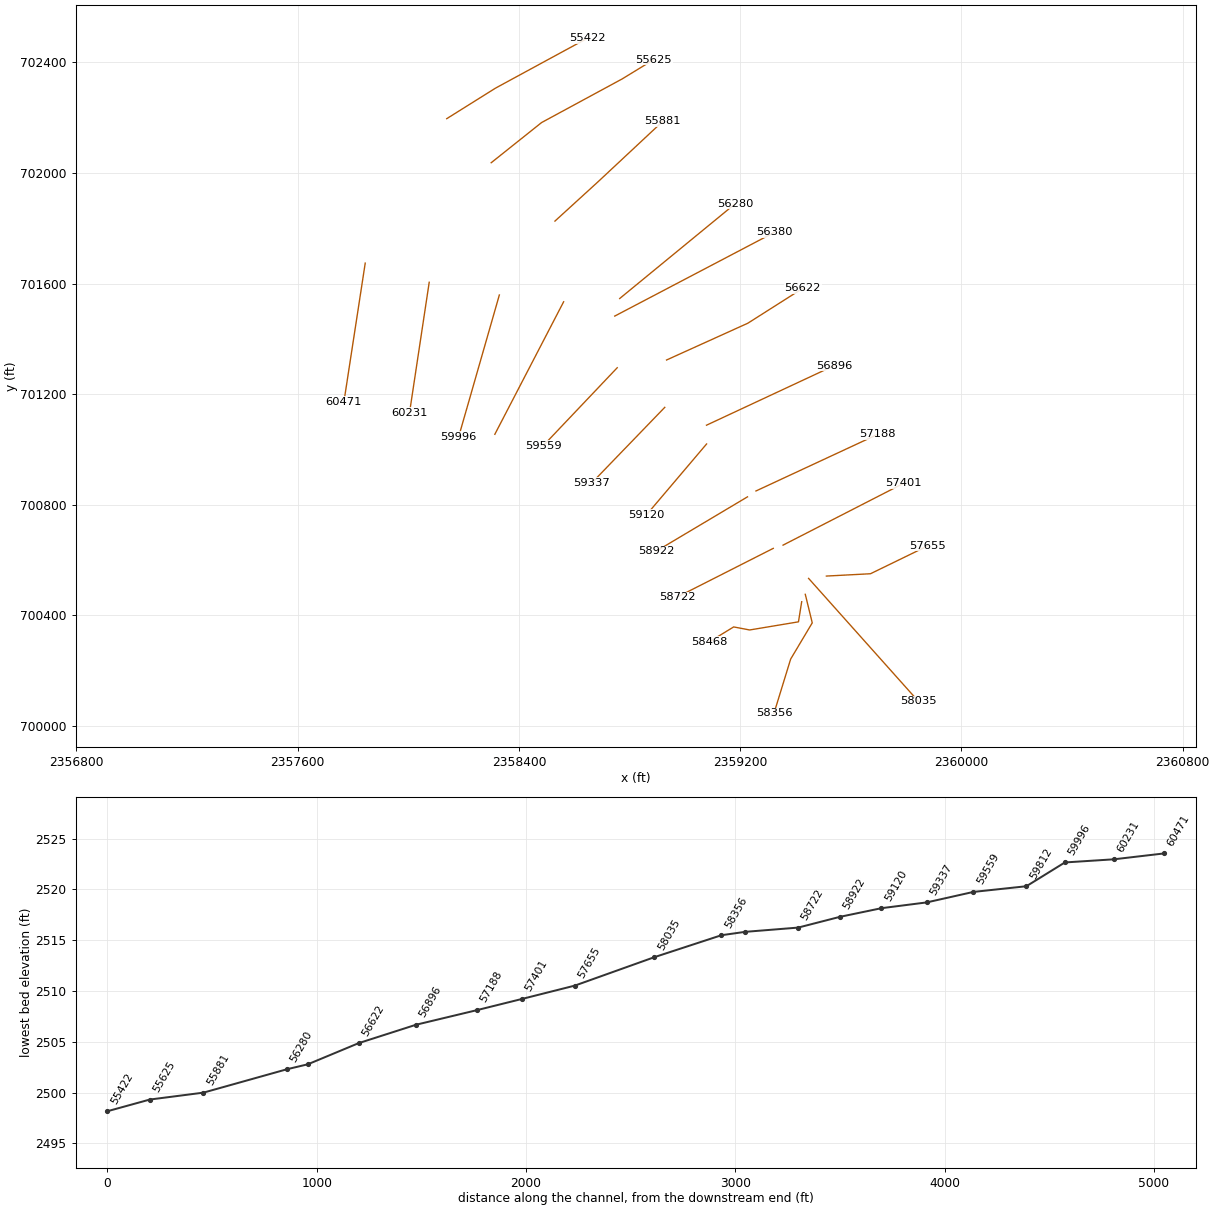
HEC-RAS study GLADYFK.prj: GLADYFK

--- GLADYFK.g01 (geometry) --- (continued)

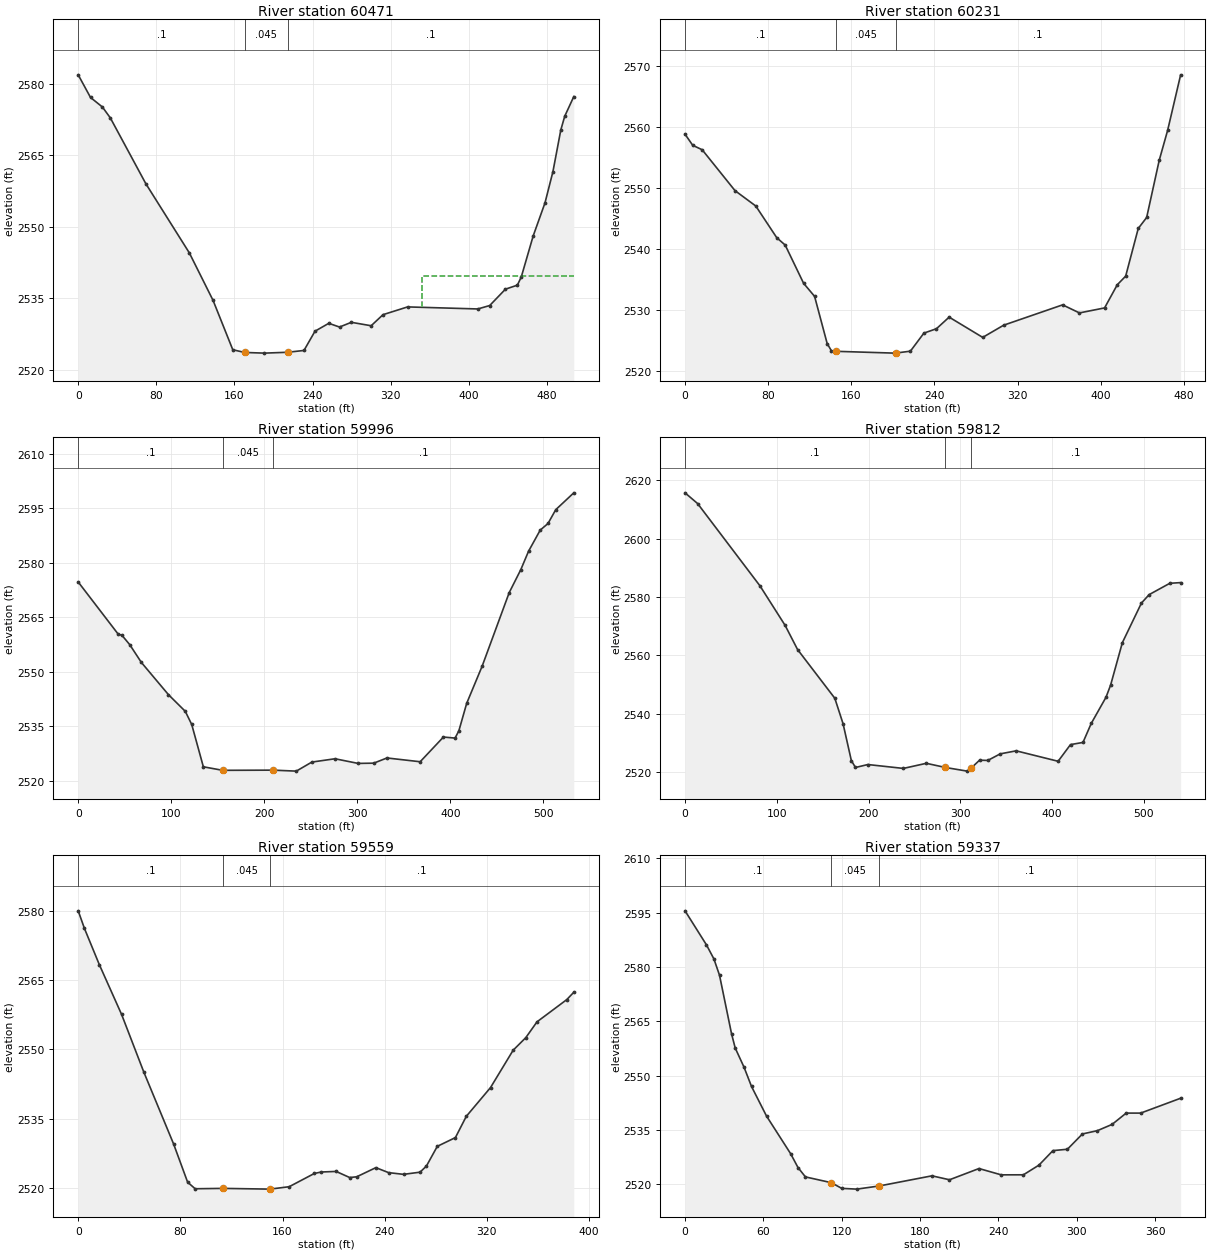
Type RM Length L Ch R = 1 ,60471   ,239.8,240.6,240.7
XS GIS Cut Line= 2
 2357844.2377369  701673.65704932357767.21885161701171.991126036
#Sta/Elev= 30
       0 2581.89    12.6 2577.15    24.8 2575.14    32.9 2572.86    69.3 2559.05
   113.8 2544.56   138.1  2534.6   158.3 2524.25   170.5 2523.68   190.7 2523.54
   214.5 2523.72   231.2  2524.1   242.5 2528.14   256.6 2529.79   267.6 2529.01
   279.7    2530     300 2529.28   312.1  2531.6   337.3 2533.23   409.2  2532.8
   421.4 2533.52   437.5 2536.95   449.7 2537.79   453.7 2539.49   465.9  2548.1
     478 2555.04   486.1 2561.56   494.2 2570.33   498.2  2573.2   507.5 2577.33
#Mann= 3 ,-1,0
       0      .1       0   170.5    .045       0   214.5      .1       0
#XS Ineff= 2 , 0
                          352.06         2539.79
Permanent Ineff=
       F       F
Bank Sta=170.5,214.5
XS Rating Curve= 0 ,0
Exp/Cntr(USF)=0,0
Exp/Cntr=0.3,0.1

Type RM Length L Ch R = 1 ,60231   ,238.2,234.5,231
XS GIS Cut Line= 2
2358075.65715698701604.4840865122358004.46083004701132.818869952
#Sta/Elev= 30
       0 2558.84     7.4 2557.02    16.5 2556.29    48.1 2549.59    68.1 2547.07
    88.3 2541.87    96.4 2540.67   114.1 2534.41   124.7 2532.26   136.8 2524.53
   140.9 2523.34   144.9 2523.26   201.6 2522.96   202.8 2522.97   216.9 2523.28
   229.9 2526.24     242 2526.96   254.2 2528.86   286.5 2525.54   306.7 2527.54
   363.4 2530.87   379.6 2529.55   403.8 2530.37     416 2534.16   424.1 2535.58
   436.2 2543.39   444.3 2545.19   456.4 2554.57   464.5 2559.48     477 2568.57
#Mann= 3 ,-1,0
       0      .1       0   144.9    .045       0   202.8      .1       0
Bank Sta=144.9,202.8
XS Rating Curve= 0 ,0
Exp/Cntr(USF)=0,0
Exp/Cntr=0.3,0.1

Type RM Length L Ch R = 1 ,59996   ,195,183.7,178.1
XS GIS Cut Line= 2
2358329.29817828701558.4586667772358182.44950004701046.527857897
#Sta/Elev= 30
       0 2574.67    42.9 2560.35    47.1 2559.98    55.4 2557.43    67.9 2552.54
      97 2543.68   115.1 2539.09     122 2535.48   134.5 2523.84   155.3 2522.87
   209.4 2522.92   234.4 2522.65   251.1 2525.14     276 2526.05   300.9 2524.77
   317.6 2524.84   331.8 2526.27   367.5 2525.23   392.5 2532.02     405 2531.74
   409.1 2533.75   417.5  2541.3   434.1 2551.51   463.2 2571.75   475.7 2578.09
     484 2583.14   496.5 2588.93   504.9 2590.76   513.2 2594.55   532.6 2599.19
#Mann= 3 ,-1,0
       0      .1       0   155.3    .045       0   209.4      .1       0
Bank Sta=155.3,209.4
XS Rating Curve= 0 ,0
Exp/Cntr(USF)=0,0
Exp/Cntr=0.3,0.1

Type RM Length L Ch R = 1 ,59812   ,260.1,253.3,247.3
XS GIS Cut Line= 2
 2358561.8085855 701533.983887072358312.98165848  701054.6861178
#Sta/Elev= 30
       0 2615.76    13.7 2612.08    81.7 2583.83   109.1 2570.27   122.6 2562.02
   163.2  2545.3   172.2 2536.55   181.2 2523.94   185.7 2521.56   199.2 2522.57
   237.9 2521.24   262.9 2522.99   283.6 2521.57   307.4 2520.31   311.9  2521.4
   320.9 2524.06   329.9 2523.98   343.4 2526.23   360.8 2527.27   406.5 2523.69
     420 2529.41   433.6 2530.15   442.6 2536.67   458.7 2545.66   463.7 2549.81
   476.5 2564.37   497.3 2577.96   505.7 2580.85   528.2 2584.73     540 2584.97
#Mann= 3 ,-1,0
       0      .1       0   283.6    .045       0   311.9      .1       0
Bank Sta=283.6,311.9
XS Rating Curve= 0 ,0
Exp/Cntr(USF)=0,0
Exp/Cntr=0.3,0.1

Type RM Length L Ch R = 1 ,59559   ,223,222.5,222.7
XS GIS Cut Line= 2
2358755.56725819701295.3547849232358488.38424638701013.894818287
#Sta/Elev= 30
       0    2580     4.9 2576.18    16.5 2568.38      34 2557.56    51.4 2545.08
    74.7 2529.53    85.7 2521.25    91.6 2519.83   113.3 2519.91   150.2 2519.75
   165.2 2520.27     185 2523.15   190.5 2523.46     202 2523.58   212.6 2522.26
   218.1 2522.42   233.1  2524.4   243.1 2523.32   254.8 2522.95   267.7 2523.42
   272.7 2524.75   281.2 2529.01   295.4 2530.91   303.9  2535.5   322.9 2541.74
   340.6 2549.82   350.5 2552.54   359.3 2555.97   382.6 2560.78   388.1 2562.37
#Mann= 3 ,-1,0
       0      .1       0   113.3    .045       0   150.2      .1       0
Bank Sta=113.3,150.2
XS Rating Curve= 0 ,0
Exp/Cntr(USF)=0,0
Exp/Cntr=0.3,0.1

Type RM Length L Ch R = 1 ,59337   ,212.1,216.5,217.6
XS GIS Cut Line= 2
2358927.54113341701152.1483618122358663.92389305700879.164011389
#Sta/Elev= 30
       0 2595.48    16.4 2586.09    22.1 2582.22    26.4 2577.72    35.6 2561.59
    38.4 2557.66    45.2 2552.33    50.9 2547.04    62.4 2538.87    80.9 2528.47
    86.5 2524.67    92.2 2522.09     112  2520.5     120 2518.93   131.5 2518.72
   148.7 2519.59   189.1 2522.39   202.5  2521.3   225.1  2524.4   242.1 2522.66
   259.1 2522.67     271 2525.34   281.7 2529.34   292.8 2529.72   304.3 2533.94
   315.7 2534.84     327 2536.57   337.8 2539.69   348.9 2539.69   379.5 2543.79
#Mann= 3 ,-1,0
       0      .1       0     112    .045       0   148.7      .1       0
Bank Sta=112,148.7
XS Rating Curve= 0 ,0
Exp/Cntr(USF)=0,0
Exp/Cntr=0.3,0.1

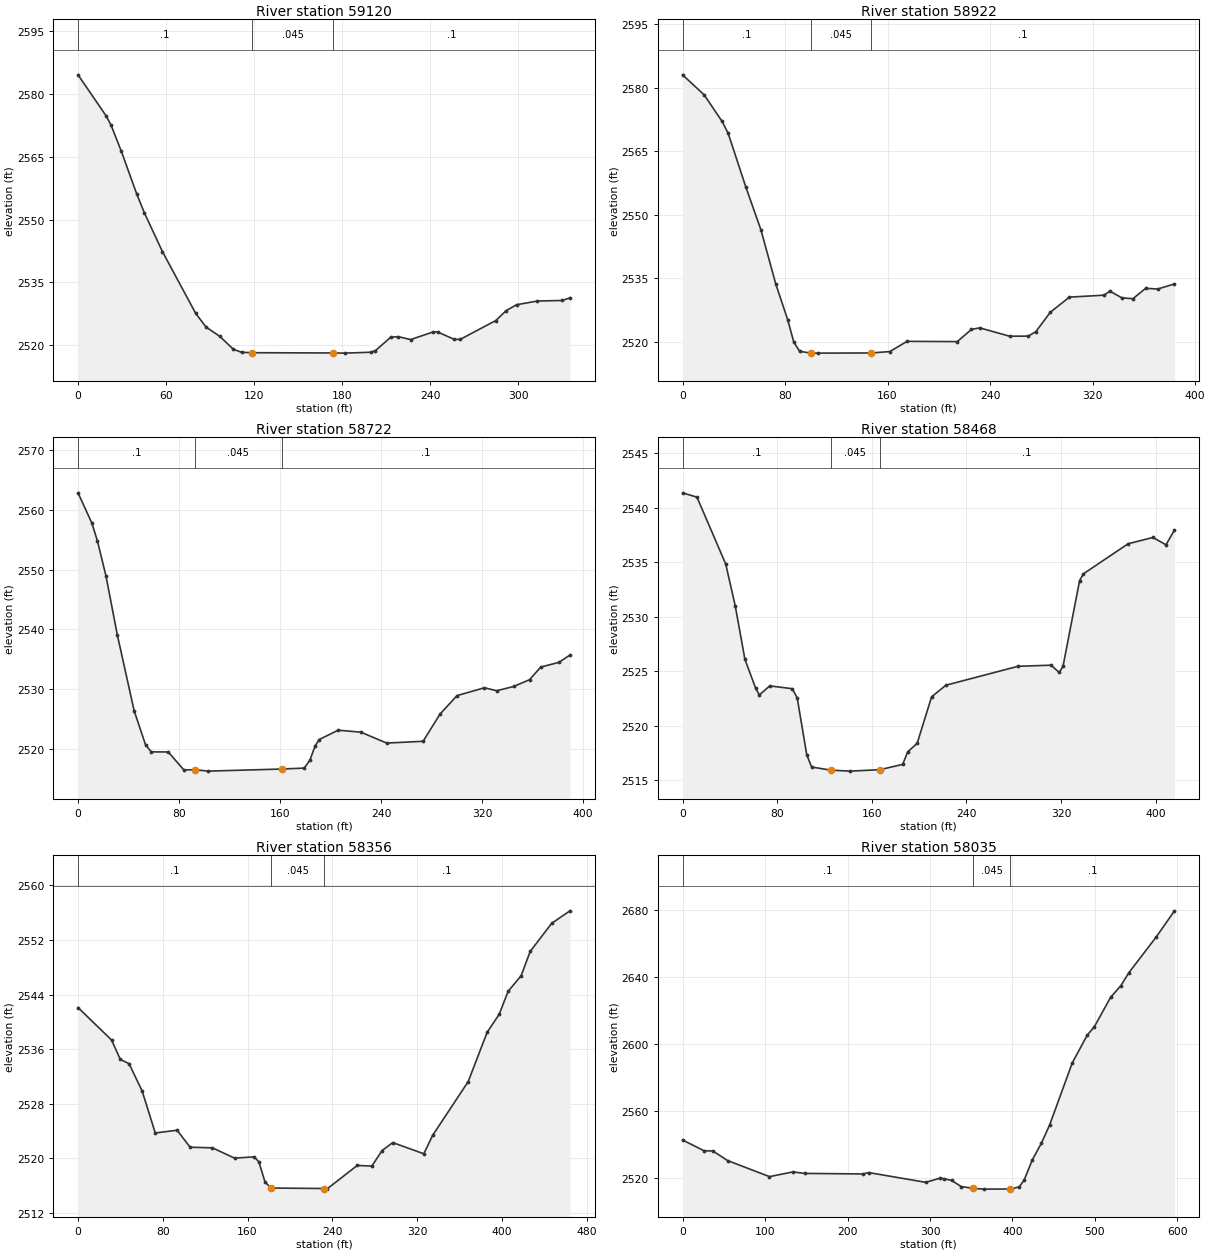
Type RM Length L Ch R = 1 ,59120   ,207.5,198.1,191.3
XS GIS Cut Line= 2
2359078.75305301701019.6706623422358861.97136296700764.082373466
#Sta/Elev= 30
       0 2584.53      19 2574.82    22.5 2572.54    29.5  2566.3      40 2556.11
    45.2 2551.62    57.5 2542.37    80.2 2527.61    87.2 2524.37    96.7 2522.12
   105.8 2519.07   111.4 2518.35   118.7 2518.25   173.9 2518.19   181.6 2518.15
   199.4 2518.36   202.6 2518.75   213.1 2521.97   218.3 2522.07   226.6 2521.38
     242 2523.21   245.2 2523.16   256.2 2521.45   260.3 2521.42   284.6 2525.92
   291.7 2528.29   298.7 2529.69   312.9 2530.58     330 2530.71   335.1 2531.36
#Mann= 3 ,-1,0
       0      .1       0   118.7    .045       0   173.9      .1       0
Bank Sta=118.7,173.9
XS Rating Curve= 0 ,0
Exp/Cntr(USF)=0,0
Exp/Cntr=0.3,0.1

Type RM Length L Ch R = 1 ,58922   ,201.7,200.1,199.4
XS GIS Cut Line= 2
2359226.73589618700828.4856475022358896.88032605700632.083094294
#Sta/Elev= 30
       0 2583.05    16.9 2578.31    30.9 2572.03    35.6 2569.23    49.5 2556.45
    61.2  2546.4    72.8  2533.6    82.1 2525.16    86.8 2519.93    91.4 2517.72
   100.3 2517.31   105.4  2517.3   147.2 2517.34   161.8 2517.67   175.2 2520.08
   214.4 2520.02   225.4 2522.89   231.9 2523.27   255.2  2521.3   269.8 2521.32
   275.7 2522.36     287 2526.95   301.9 2530.53   328.9 2530.99   333.5 2531.94
   342.8 2530.37   351.5 2530.15   361.4 2532.61   370.8 2532.44   383.9 2533.65
#Mann= 3 ,-1,0
       0      .1       0   100.3    .045       0   147.2      .1       0
Bank Sta=100.3,147.2
XS Rating Curve= 0 ,0
Exp/Cntr(USF)=0,0
Exp/Cntr=0.3,0.1

Type RM Length L Ch R = 1 ,58722   ,263.1,253.6,253.1
XS GIS Cut Line= 2
2359319.90120988700642.1550200992358972.41976959700465.896318503
#Sta/Elev= 30
       0 2562.88      11 2557.79    15.4 2554.79    22.1    2549    31.1  2539.1
    44.5 2526.32    53.5 2520.65      58 2519.47    71.5 2519.45    83.8 2516.44
    92.8 2516.48   102.9 2516.24   161.2 2516.59   179.1 2516.75   183.6 2518.04
   187.8 2520.47     191 2521.53     206  2523.1     224 2522.77   244.5 2520.94
   273.3 2521.24   286.7  2525.8   300.2  2528.9   321.9 2530.21   331.6 2529.71
   345.1 2530.43   357.6 2531.56   366.5 2533.68   380.9 2534.47   389.6 2535.69
#Mann= 3 ,-1,0
       0      .1       0    92.8    .045       0   161.2      .1       0
Bank Sta=92.8,161.2
XS Rating Curve= 0 ,0
Exp/Cntr(USF)=0,0
Exp/Cntr=0.3,0.1

Type RM Length L Ch R = 1 ,58468   ,86.7,112.7,124.2
XS GIS Cut Line= 5
2359422.75204826700449.2364511712359411.08346215700376.468841737
2359234.42561123700347.0258665822359176.76645155700358.066982265
2359087.79611504700303.711915549
#Sta/Elev= 30
       0 2541.38    12.2 2540.98    36.5 2534.84    44.6 2530.97    52.7  2526.1
    61.7 2523.46    64.9 2522.81    73.7 2523.65    92.7 2523.39    96.9 2522.56
     105 2517.32   109.1  2516.2   125.3 2515.91   141.4 2515.82   166.7 2515.95
   186.1 2516.44   190.3 2517.59   198.3 2518.37   210.5 2522.64   222.6 2523.71
   283.6 2525.45   311.5 2525.55   318.4 2524.88   321.6 2525.45   335.6 2533.31
   338.8 2533.94   376.6  2536.7   397.6 2537.28   408.6 2536.61   415.8 2537.95
#Mann= 3 ,-1,0
       0      .1       0   125.3    .045       0   166.7      .1       0
Bank Sta=125.3,166.7
XS Rating Curve= 0 ,0
Exp/Cntr(USF)=0,0
Exp/Cntr=0.3,0.1

Type RM Length L Ch R = 1 ,58356   ,280.2,320.4,339.4
XS GIS Cut Line= 4
2359435.72835665700475.9682443082359460.90817116700372.731004802
2359382.85074617 700241.795969332359322.41919133700045.393416122
#Sta/Elev= 30
       0  2542.1    31.7 2537.33    39.9  2534.5    48.2 2533.87    60.5 2529.87
    72.9 2523.72    93.5 2524.12   105.8 2521.63   126.9 2521.54   147.7 2520.03
   166.3 2520.22   170.7 2519.47   176.5 2516.52   182.3 2515.65   231.9 2515.58
   234.8 2515.49   263.5 2518.96   277.3 2518.87   286.9 2521.14     297 2522.31
   326.3 2520.67   334.7 2523.38   368.2 2531.25   386.1 2538.48   397.5 2541.12
   405.8 2544.45   418.2 2546.78   426.7 2550.32     447 2554.44   464.2 2556.27
#Mann= 3 ,-1,0
       0      .1       0   182.3    .045       0   231.9      .1       0
Bank Sta=182.3,231.9
XS Rating Curve= 0 ,0
Exp/Cntr(USF)=0,0
Exp/Cntr=0.3,0.1

Type RM Length L Ch R = 1 ,58035   ,334,380.3,391.7
XS GIS Cut Line= 2
2359447.71587218700533.5802992242359844.99739007 700088.73690948
#Sta/Elev= 30
       0 2542.65    26.1 2536.22    36.7 2536.09    54.7 2530.35   105.4 2520.79
   133.8 2523.61   147.9 2522.71   218.7 2522.39   225.8  2523.2   294.9 2517.39
   311.6 2519.78     317 2519.57   326.4 2518.49   337.7 2514.88   351.9 2513.83
   365.2 2513.33   397.2 2513.41   408.1 2514.62   414.2 2518.77   424.2 2530.94
   434.9 2540.56   445.1 2551.65   472.5 2588.66   490.7 2605.25   499.3 2610.25
     519 2627.79   531.5 2634.76   541.1 2642.46   574.4 2663.86   596.4 2679.38
#Mann= 3 ,-1,0
       0      .1       0   351.9    .045       0   397.2      .1       0
Bank Sta=351.9,397.2
XS Rating Curve= 0 ,0
Exp/Cntr(USF)=0,0
Exp/Cntr=0.3,0.1

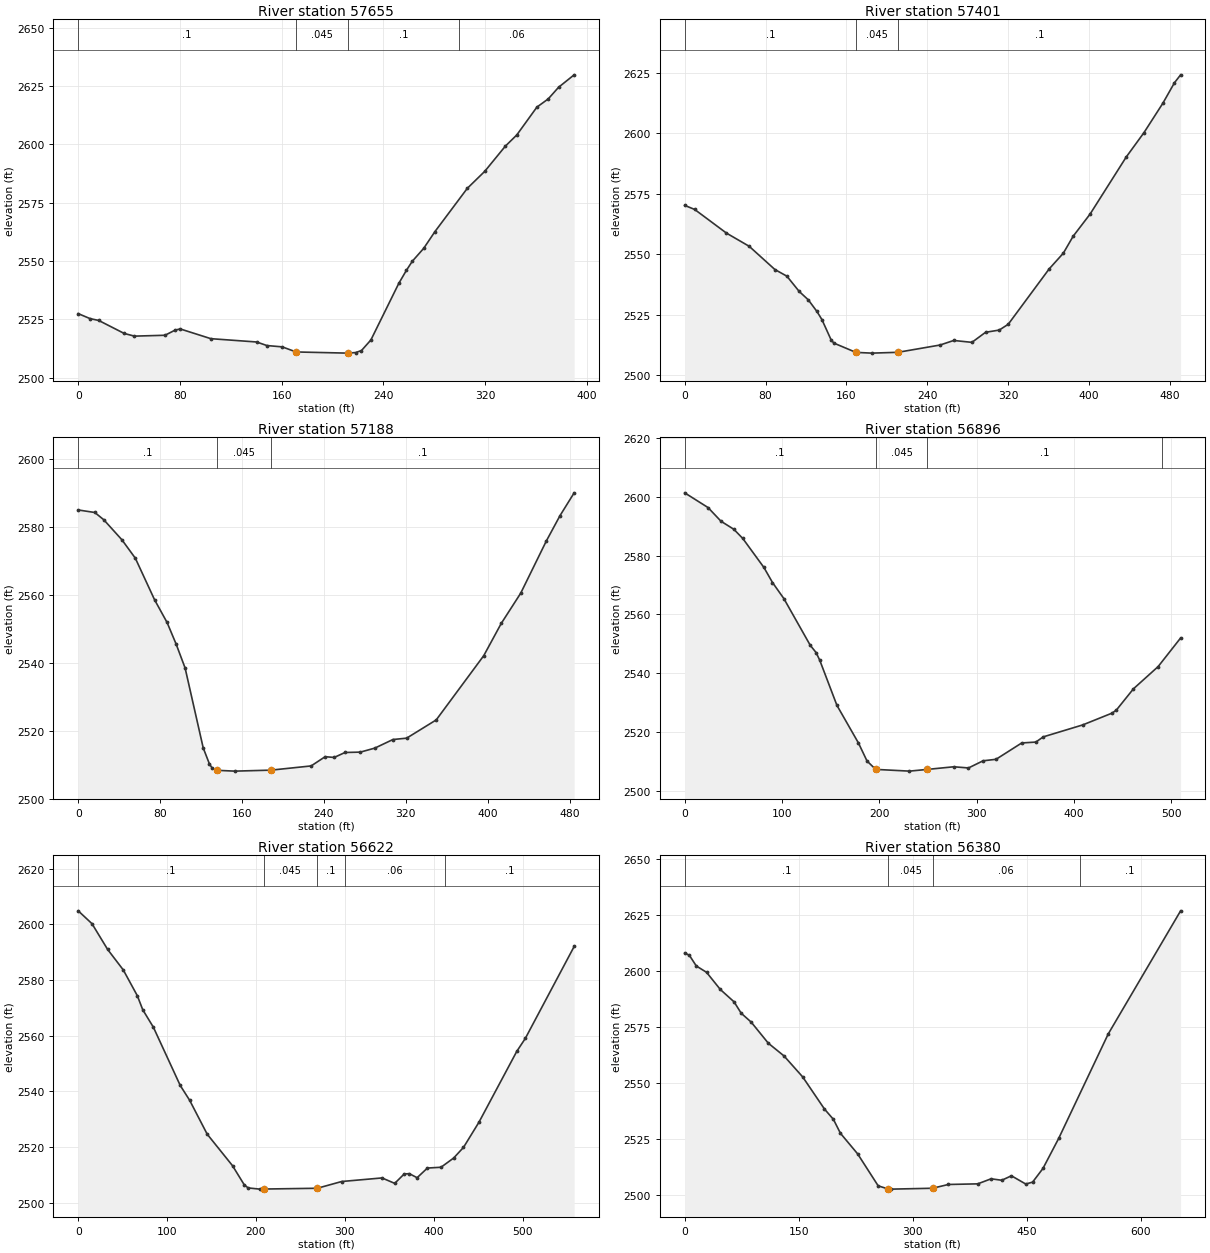
Type RM Length L Ch R = 1 ,57655   ,249.5,254,250
XS GIS Cut Line= 3
2359512.06428705700541.9735707282359671.53644564700550.366842233
2359878.57047609700651.086100288
#Sta/Elev= 30
       0 2527.45     9.4  2525.3    16.1 2524.53    36.2 2518.95    44.2 2517.81
    68.2 2518.18    76.2 2520.39    80.2 2520.89   104.3 2516.72   140.3  2515.3
   148.3 2513.78   160.4 2513.21   171.3 2511.03   211.8 2510.53   218.2 2510.78
   222.7 2511.64   230.1 2516.17     252 2540.37     258 2545.98   262.7 2549.91
   271.6  2555.4   280.5 2562.62   305.9 2581.12   319.6 2588.39   335.8 2599.18
   344.8 2603.98   360.6  2615.9   369.5 2619.41   377.7 2624.43   389.9 2629.74
#Mann= 4 ,-1,0
       0      .1       0   171.3    .045       0   211.8      .1       0
  299.69     .06       0
Bank Sta=171.3,211.8
XS Rating Curve= 0 ,0
Exp/Cntr(USF)=0,0
Exp/Cntr=0.3,0.1

Type RM Length L Ch R = 1 ,57401   ,216.4,212.9,212.9
XS GIS Cut Line= 2
2359355.38988563700653.8838574562359791.84000387700877.704430912
#Sta/Elev= 30
       0 2570.24     9.9 2568.55    41.3 2558.79    63.8 2553.34    89.2 2543.75
   101.1 2540.99   113.3 2534.67   122.3  2531.2   130.8 2526.42   135.7 2523.09
   144.7 2514.81   147.5 2513.36   169.4 2509.51   185.2 2509.21     211 2509.55
   252.6 2512.56   266.1 2514.44   284.1 2513.66   297.6 2517.82   311.1 2518.73
     320 2521.13   360.5    2544   374.5 2550.49   384.2 2557.48     401 2566.67
   436.7 2590.21   454.3 2600.31   472.9  2612.4   484.4 2620.89   490.5 2624.16
#Mann= 3 ,-1,0
       0      .1       0   169.4    .045       0     211      .1       0
Bank Sta=169.4,211
XS Rating Curve= 0 ,0
Exp/Cntr(USF)=0,0
Exp/Cntr=0.3,0.1

Type RM Length L Ch R = 1 ,57188   ,291.5,291.6,291.6
XS GIS Cut Line= 2
2359257.46838475 700849.726859232359696.71626015701053.963132509
#Sta/Elev= 30
       0 2585.04    16.2  2584.3      25 2582.15    42.7 2576.25    55.8 2570.83
    74.6 2558.58    86.8  2551.9    95.6 2545.57   104.4  2538.5   122.1 2514.95
   128.1 2510.29   130.9 2508.96   135.3 2508.36     153 2508.12   188.3 2508.41
   227.5 2509.65   241.2 2512.37     250 2512.15   260.6 2513.61   275.6 2513.72
   289.7  2514.9   307.4 2517.43   320.8 2517.83   349.7 2523.21   396.1 2542.13
   413.2 2551.63   432.2 2560.53   457.3 2575.95   470.6 2583.38   484.4 2590.09
#Mann= 3 ,-1,0
       0      .1       0   135.3    .045       0   188.3      .1       0
Bank Sta=135.3,188.3
XS Rating Curve= 0 ,0
Exp/Cntr(USF)=0,0
Exp/Cntr=0.3,0.1

Type RM Length L Ch R = 1 ,56896   ,273,274,272
XS GIS Cut Line= 2
2359078.41192598701087.5362185272359540.04185873701302.963520479
#Sta/Elev= 30
       0 2601.32      24 2596.31    37.3 2591.66    50.5 2588.92    59.7 2585.79
    81.4 2575.93    90.2 2570.82   101.9 2565.34     129 2549.46     135 2546.99
   138.8 2544.34   156.4 2529.03   178.5 2516.24   187.3 2510.12   196.2 2507.27
   230.9 2506.68   249.1 2507.26   276.4 2508.16   291.5 2507.76   306.5 2510.19
   319.8  2510.7   346.2 2516.26   360.7 2516.56   368.3 2518.33   408.9  2522.4
     439 2526.41   443.4 2527.44     461 2534.69   486.3 2542.23   509.4 2551.96
#Mann= 4 ,-1,0
       0      .1       0   196.2    .045       0   249.1      .1       0
     490     .06       0
Bank Sta=196.2,249.1
XS Rating Curve= 0 ,0
Exp/Cntr(USF)=0,0
Exp/Cntr=0.3,0.1

Type RM Length L Ch R = 1 ,56622   ,242,242.6,245.8
XS GIS Cut Line= 3
2358934.00871202701323.3869524832359228.11148064701456.478666125
     2359426.628      701582.618
#Sta/Elev= 30
       0 2604.84    15.5 2600.22    33.1 2590.97    50.7 2583.61    66.5 2574.35
    72.6 2569.32    84.6 2563.01   114.8  2542.1   125.3 2536.83   145.1 2524.62
   173.6 2513.29   186.8 2506.43   191.2  2505.3   204.3 2504.87   208.5  2504.9
     269 2505.18   296.5 2507.61   341.8 2508.89   356.1 2506.94   366.8 2510.32
   372.6 2510.42   381.3 2508.97   392.9 2512.44   408.2 2512.73   422.4 2516.03
   433.5 2519.87   450.9 2528.91   493.5 2554.39     503 2558.98     558 2592.03
#Mann= 5 ,-1,0
       0      .1       0   208.5    .045       0     269      .1       0
     300     .06       0  412.82      .1       0
Bank Sta=208.5,269
XS Rating Curve= 0 ,0
Exp/Cntr=0.3,0.1

Type RM Length L Ch R = 1 ,56380   ,92.5,100.2,103.9
XS GIS Cut Line= 2
 2358746.6569149 701482.218501222359324.69612729701785.452186405
#Sta/Elev= 30
       0    2608     6.2 2606.92    15.3 2602.18    28.8 2599.35    46.9 2591.71
      65  2586.2    74.4 2581.13    87.5 2577.19   110.1 2567.77   130.7 2562.12
   155.3 2552.77     184 2538.45   195.8 2533.84     205 2527.66   227.6 2518.51
   254.7 2504.24   268.2 2502.82   272.1 2502.79   326.3 2503.18     347 2504.86
   385.7 2505.14   403.3 2507.39   417.3 2506.74     430 2508.73   448.9 2505.06
   457.9 2505.91   471.5 2511.99   492.2 2525.36   557.4 2571.88   652.7 2626.74
#Mann= 4 ,-1,0
       0      .1       0   268.2    .045       0   326.3     .06       0
     520      .1       0
Bank Sta=268.2,326.3
XS Rating Curve= 0 ,0
Exp/Cntr(USF)=0,0
Exp/Cntr=0.3,0.1

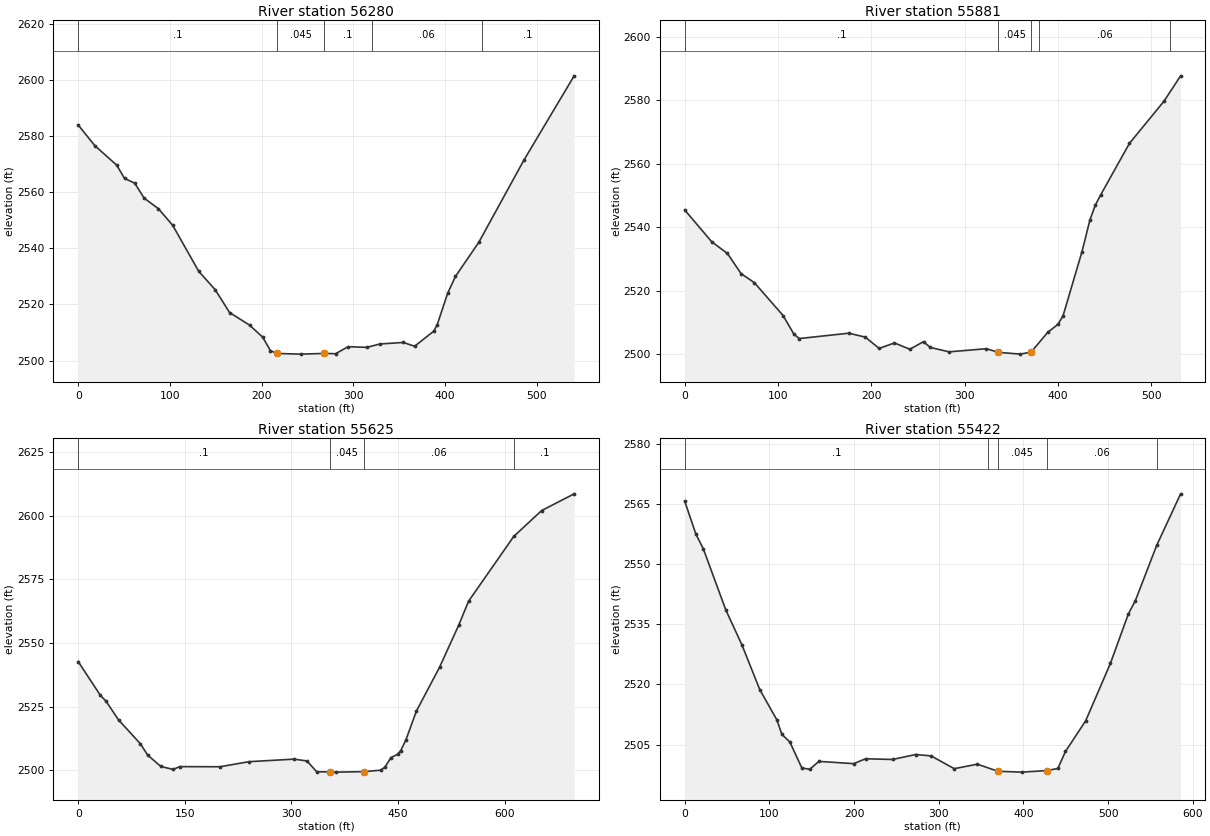
Type RM Length L Ch R = 1 ,56280   ,403.6,398.7,401
XS GIS Cut Line= 2
2358764.57236074701545.7401858812359182.68585037701888.840511876
#Sta/Elev= 30
       0 2583.88      18 2576.58      42 2569.58    50.5 2564.88    61.6 2563.19
    71.9 2557.86    87.4  2554.1     103  2548.2   131.5 2531.77   149.5  2525.2
   165.1 2517.11   186.9 2512.63   201.3  2508.3   209.6 2503.57   216.8 2502.53
   242.7  2502.3   268.6 2502.55   280.7 2502.44   294.4 2504.95   314.8 2504.71
     329 2505.91   354.6 2506.46   366.9  2505.1   387.6 2510.43   391.5 2512.74
   402.9 2523.92   411.4 2529.95     437 2542.17   485.9 2571.27   540.9  2601.4
#Mann= 5 ,-1,0
       0      .1       0   216.8    .045       0   268.6      .1       0
     320     .06       0     440      .1       0
Bank Sta=216.8,268.6
XS Rating Curve= 0 ,0
Exp/Cntr=0.3,0.1

Type RM Length L Ch R = 1 ,55881   ,265.8,256.2,253.3
XS GIS Cut Line= 3
2358530.32407545701825.6878567242358685.49522354701967.245781736
2358920.16874541702186.435829788
#Sta/Elev= 30
       0 2545.47    28.9 2535.45    45.8 2531.74    60.4 2525.39    74.6 2522.55
   105.4 2512.17     117  2506.3   122.7 2504.91   175.8  2506.6   193.5 2505.36
   208.3  2501.8   224.7 2503.53   241.1 2501.53   255.8 2503.93     263 2502.11
   283.2 2500.72   323.2 2501.71   335.9 2500.57   359.4    2500   371.1 2500.64
   388.8 2506.85   399.8 2509.39   405.3 2512.11   425.6 2532.36     434 2542.24
   439.7 2546.88   445.4 2550.13   476.4 2566.47   513.3 2579.72   531.2 2587.76
#Mann= 5 ,-1,0
       0      .1       0   335.9    .045       0   371.1      .1       0
  380.04     .06       0  520.04      .1       0
Bank Sta=335.9,371.1
XS Rating Curve= 0 ,0
Exp/Cntr(USF)=0,0
Exp/Cntr=0.3,0.1

Type RM Length L Ch R = 1 ,55625   ,195.7,202.7,193.4
XS GIS Cut Line= 4
2358299.77557798702036.7481111452358482.09623152702182.117394935
 2358772.9678902702339.6145510782358887.40330056 702409.43863968
#Sta/Elev= 30
       0 2542.68    31.2 2529.45    39.2 2527.14    56.8  2519.8    87.5 2510.46
    97.7 2506.03   116.2 2501.56   133.5 2500.38   142.9 2501.48   199.8 2501.43
   240.1 2503.41   303.8 2504.42     322  2503.7   335.6 2499.47   353.8 2499.39
   362.9 2499.32   402.2 2499.51   425.8 2500.08   431.7  2501.3   440.2 2505.01
   449.4 2506.29   453.9 2507.76   461.2 2511.95     476  2523.3   508.5 2540.44
   535.8 2557.16   549.4 2566.39     613  2591.8   652.1 2601.93     698 2608.52
#Mann= 4 ,-1,0
       0      .1       0   353.8    .045       0   402.2     .06       0
  613.95      .1       0
Bank Sta=353.8,402.2
XS Rating Curve= 0 ,0
Exp/Cntr=0.3,0.1

Type RM Length L Ch R = 1 ,55422   ,299.6,284.1,283.7
XS GIS Cut Line= 3
2358138.98263291702196.1003370022358315.49651878702306.635082816
2358647.15836195702486.680083395
#Sta/Elev= 30
       0 2565.69    13.3 2557.42      22  2553.8    48.6 2538.55    67.5 2529.91
    88.7 2518.71     109 2511.13   114.8 2507.56   124.1 2505.71   138.3 2499.23
   147.7 2498.86   158.4 2500.85   199.6 2500.28   213.6  2501.5   245.4 2501.32
   272.8 2502.56     291 2502.21   318.3 2499.03   345.6 2500.15   369.9 2498.38
     398 2498.17   427.5 2498.55   440.7 2499.08   449.6 2503.31   473.5 2510.95
   502.7 2525.26   523.8 2537.51   532.2  2540.9   557.3 2554.62   585.6 2567.49
#Mann= 5 ,-1,0
       0      .1       0  358.27     .06       0   369.9    .045       0
   427.5     .06       0  558.27      .1       0
Bank Sta=369.9,427.5
XS Rating Curve= 0 ,0
Exp/Cntr(USF)=0,0
Exp/Cntr=0.3,0.1