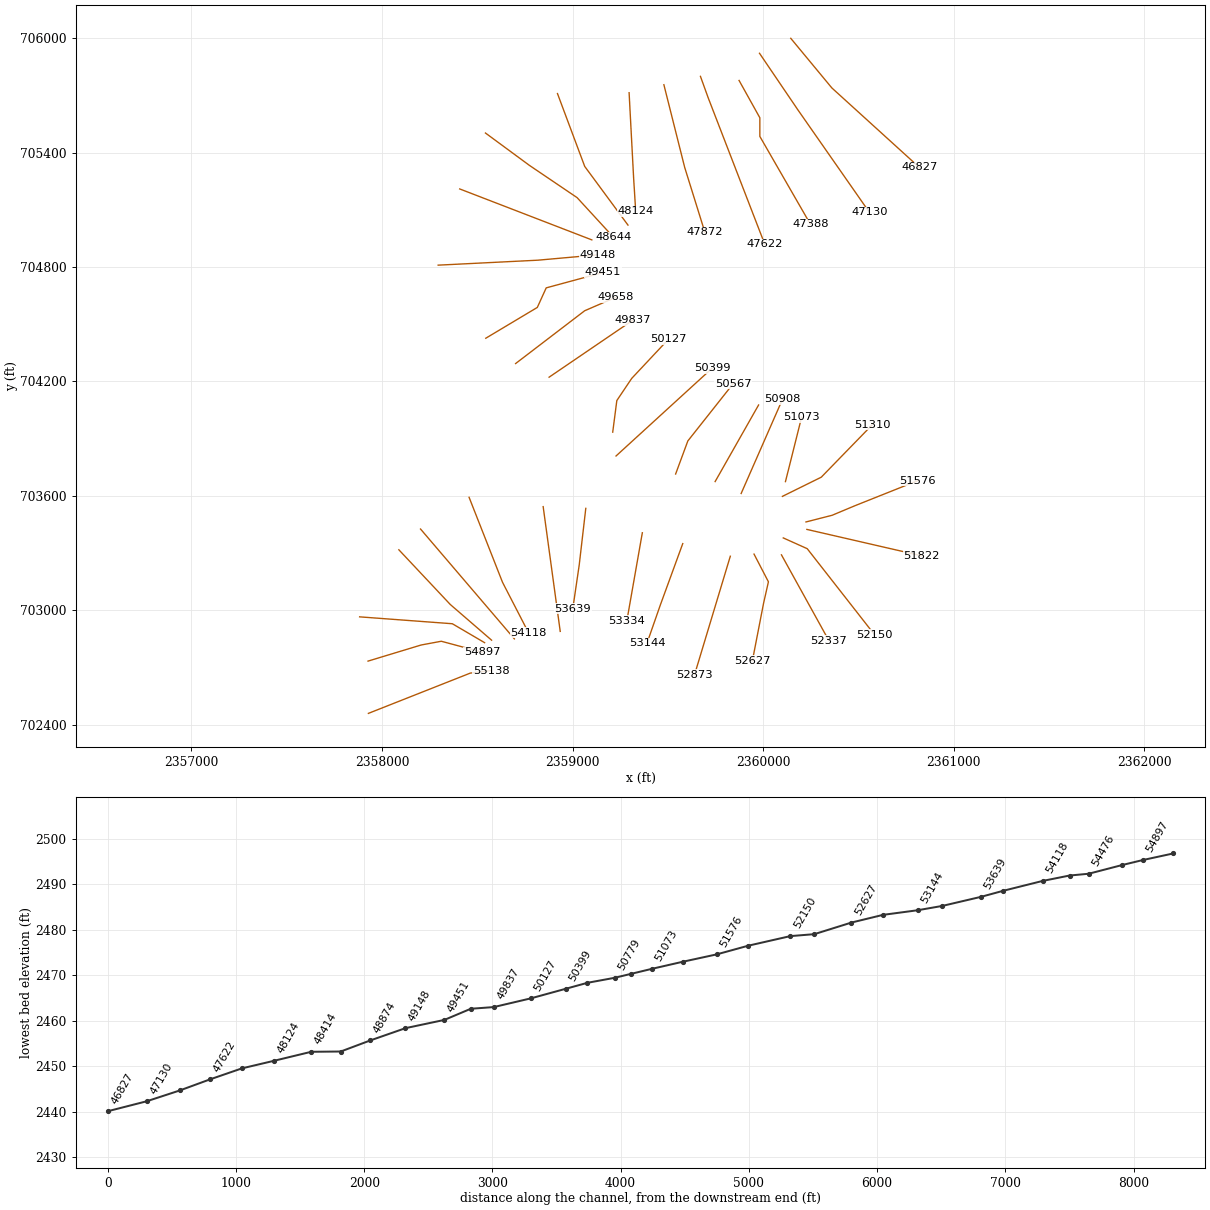
HEC-RAS study GLADYFK.prj: GLADYFK

--- GLADYFK.g01 (geometry) --- (continued)

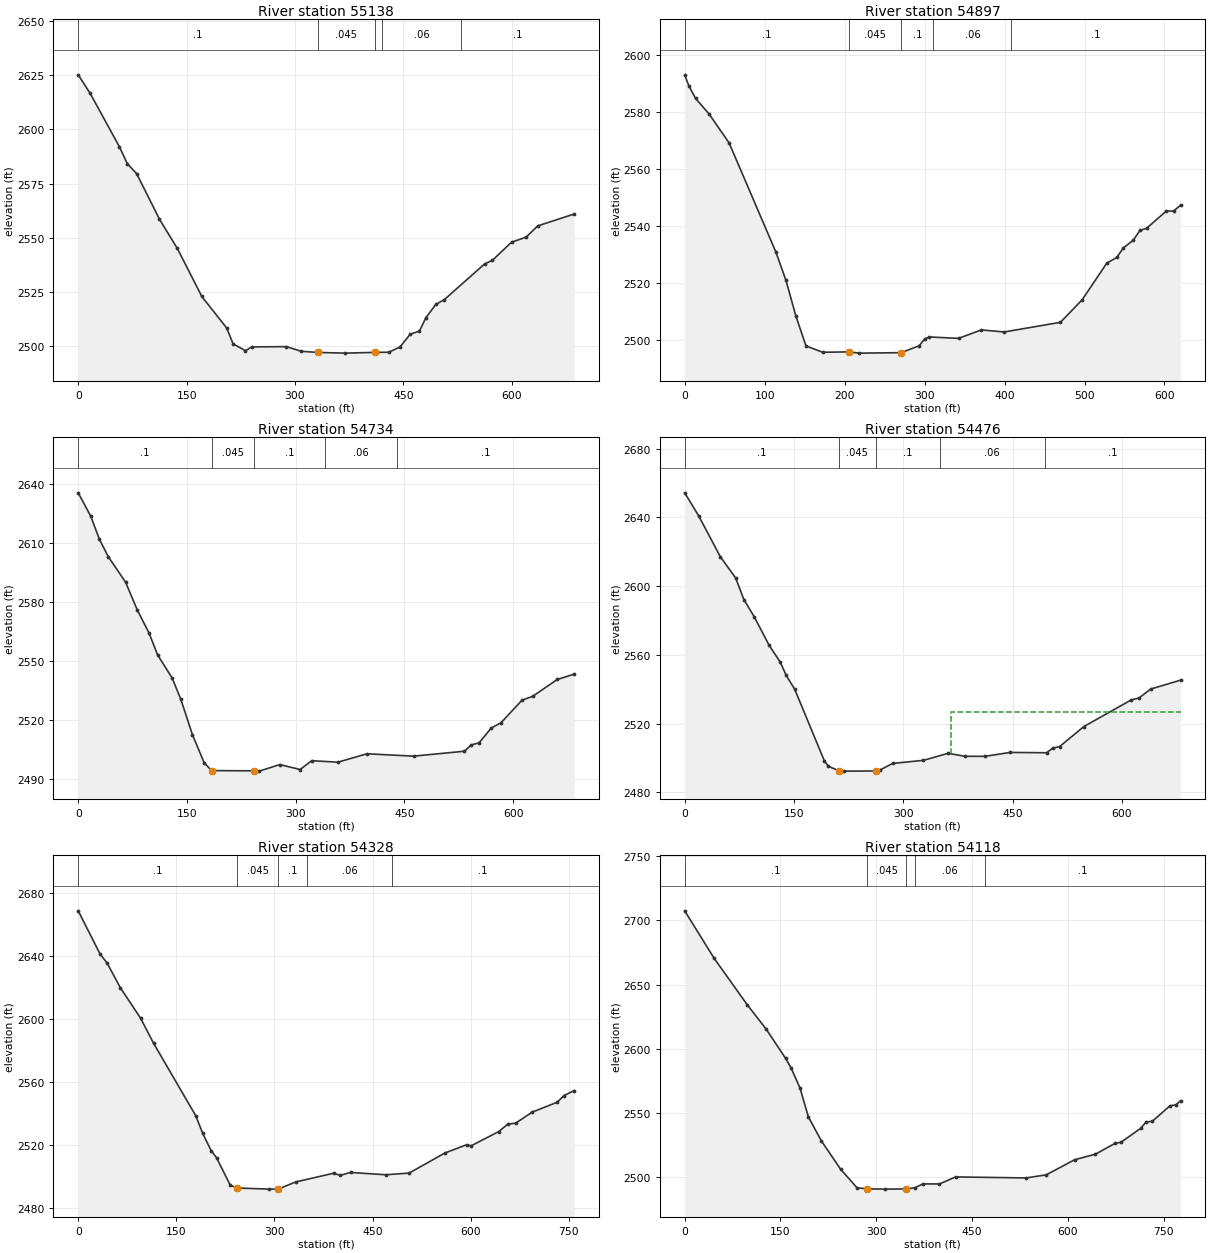
Type RM Length L Ch R = 1 ,55138   ,240.8,240.8,237.8
XS GIS Cut Line= 3
2357928.89514837702458.4422119532358463.39212335702669.706423906
2358574.20762613702683.378593468
#Sta/Elev= 30
       0 2625.21    16.4 2616.74      57 2592.02      68 2584.18    80.9 2579.57
   112.5 2558.56   137.2 2545.06   171.1 2522.91   205.7 2508.27   214.3 2501.06
   231.5 2497.89   240.1 2499.65   288.2 2499.76   308.9  2497.6   331.4  2497.1
   369.1 2496.77   410.1 2497.11     430 2497.19   445.5 2499.64   459.4 2505.48
   472.3 2506.95     481 2512.99   494.8 2519.22   506.8 2521.49   562.4 2537.92
   573.3 2539.62   599.7 2547.95   619.9 2550.29     636  2555.5   686.4 2560.96
#Mann= 5 ,-1,0
       0      .1       0   331.4    .045       0   410.1      .1       0
     420     .06       0     530      .1       0
Bank Sta=331.4,410.1
XS Rating Curve= 0 ,0
Exp/Cntr=0.3,0.1

Type RM Length L Ch R = 1 ,54897   ,171.8,162.7,151.2
XS GIS Cut Line= 4
2357927.03812095 702732.718284372358205.61131307702817.214430144
2358311.33977221 702836.89979012 2358525.3185339702779.475870641
#Sta/Elev= 30
       0 2593.02     5.4 2589.02    13.7 2584.72    30.4 2579.31    55.5 2569.15
     114 2530.82   126.6 2520.93   139.1 2508.29   151.7 2497.84   172.6  2495.6
   205.6 2495.74   218.5  2495.3   270.7 2495.46   293.3 2497.89   300.1 2500.28
   305.9 2500.98   342.5 2500.48     371 2503.45   399.5 2502.73   469.9 2506.12
   497.1 2514.04   527.9 2526.91   540.3 2528.88   548.6 2532.24     561 2534.95
   569.3 2538.37   577.6 2539.13   602.5 2545.23   611.3 2545.16   620.2  2547.3
#Mann= 5 ,-1,0
       0      .1       0   205.6    .045       0   270.7      .1       0
  311.11     .06       0  408.65      .1       0
Bank Sta=205.6,270.7
XS Rating Curve= 0 ,0
Exp/Cntr(USF)=0,0
Exp/Cntr=0.3,0.1

Type RM Length L Ch R = 1 ,54734   ,277.6,257.9,235.5
XS GIS Cut Line= 3
2357882.93181325702964.895023442 2358369.2624576702928.835743953
2358538.68883527702829.475639687
#Sta/Elev= 30
       0 2635.55    17.3 2623.66    29.3 2611.89    41.4 2603.16    65.4 2590.14
    81.5 2576.04    97.5  2564.5   109.5 2553.25   129.6 2541.46   141.6 2530.63
   157.6 2512.66   173.7 2498.47183.99712494.453242.39622494.351   249.9 2494.19
     278 2497.53   306.1 2495.01   322.1  2499.5   358.2 2498.73   398.3    2503
   462.5  2501.8   532.8  2504.3   542.1 2507.48   552.9 2508.56   569.9 2516.13
   583.1 2518.73   612.3 2530.26   626.9  2532.2   660.9 2540.76   684.1 2543.45
#Mann= 5 ,-1,0
       0      .1       0183.9971    .045       0242.3962      .1       0
     340     .06       0     440      .1       0
Bank Sta=183.9971,242.3962
XS Rating Curve= 0 ,0
Exp/Cntr(USF)=0,0
Exp/Cntr=0.3,0.1

Type RM Length L Ch R = 1 ,54476   ,149.2,148.9,149.4
XS GIS Cut Line= 3
2358088.80579049703316.7558492112358358.57080221703029.791808146
2358575.37415811702842.450804325
#Sta/Elev= 30
       0 2654.36    19.1 2641.05    48.8 2617.22      70 2604.73    81.3 2592.14
    95.5 2582.14   115.9 2565.52   131.2 2555.77   139.2 2548.11   150.9 2540.02
   191.7 2498.24   197.3 2495.09   211.5 2492.55     219  2492.3   261.9 2492.38
   268.1 2492.96   285.2 2496.78   327.5 2498.59   361.5 2502.66   384.5 2500.95
   411.8 2500.91   446.5 2503.19   496.4    2503   504.9 2505.64   514.5 2506.64
   547.7 2518.28   612.7 2533.77   623.3 2534.88   639.3  2540.1   680.4 2545.29
#Mann= 5 ,-1,0
       0      .1       0   211.5    .045       0   261.9      .1       0
     350     .06       0  493.85      .1       0
#XS Ineff= 2 , 0
                          365.23         2526.58
Permanent Ineff=
       F       F
Bank Sta=211.5,261.9
XS Rating Curve= 0 ,0
Exp/Cntr=0.3,0.1

Type RM Length L Ch R = 1 ,54328   ,219.4,209.1,198.7
XS GIS Cut Line= 2
2358202.46223007703425.7678944232358694.86749167702849.429917773
#Sta/Elev= 30
       0 2668.77    33.4 2641.35    44.2 2635.54    64.2 2620.04    95.3 2600.58
   115.1 2584.67   179.7 2538.54   190.2 2527.42   203.1 2516.43   211.6 2511.72
   232.3 2494.49   242.7 2492.63   292.1 2491.91   305.9 2491.98   332.2 2496.46
   390.3    2502   400.6 2500.69   416.4 2502.51   469.8 2501.04   505.8 2502.11
   560.5 2514.89   593.8 2520.13   600.5 2519.41   642.6 2528.47     657 2533.31
   668.4 2533.78   693.9 2540.84   732.1 2547.14   742.6 2551.41     758 2554.53
#Mann= 5 ,-1,0
       0      .1       0   242.7    .045       0   305.9      .1       0
     350     .06       0     480      .1       0
Bank Sta=242.7,305.9
XS Rating Curve= 0 ,0
Exp/Cntr(USF)=0,0
Exp/Cntr=0.3,0.1

Type RM Length L Ch R = 1 ,54118   ,313.3,306.6,298.6
XS GIS Cut Line= 3
2358457.25619076703592.264448922 2358632.7804663703146.064088602
2358768.95236796702882.244741836
#Sta/Elev= 30
       0 2707.37    46.3 2670.29    97.9 2634.27     128 2615.01   158.1 2592.43
   166.7 2584.97   180.5 2569.44   193.7 2546.94   213.9 2528.35     244 2506.31
   269.8 2491.78   285.4 2490.96   313.1 2490.73     347 2490.88   360.1 2491.77
     373  2494.8   398.8 2494.74   424.2 2500.23   534.5 2499.44     566 2501.85
   610.3 2513.58     643 2517.93     674 2526.41     683 2527.22   713.6 2537.93
   722.4 2543.01   732.1 2543.53   759.6 2555.57   768.6 2556.33   776.4 2559.48
#Mann= 5 ,-1,0
       0      .1       0   285.4    .045       0     347      .1       0
     360     .06       0     470      .1       0
Bank Sta=285.4,347
XS Rating Curve= 0 ,0
Exp/Cntr=0.3,0.1

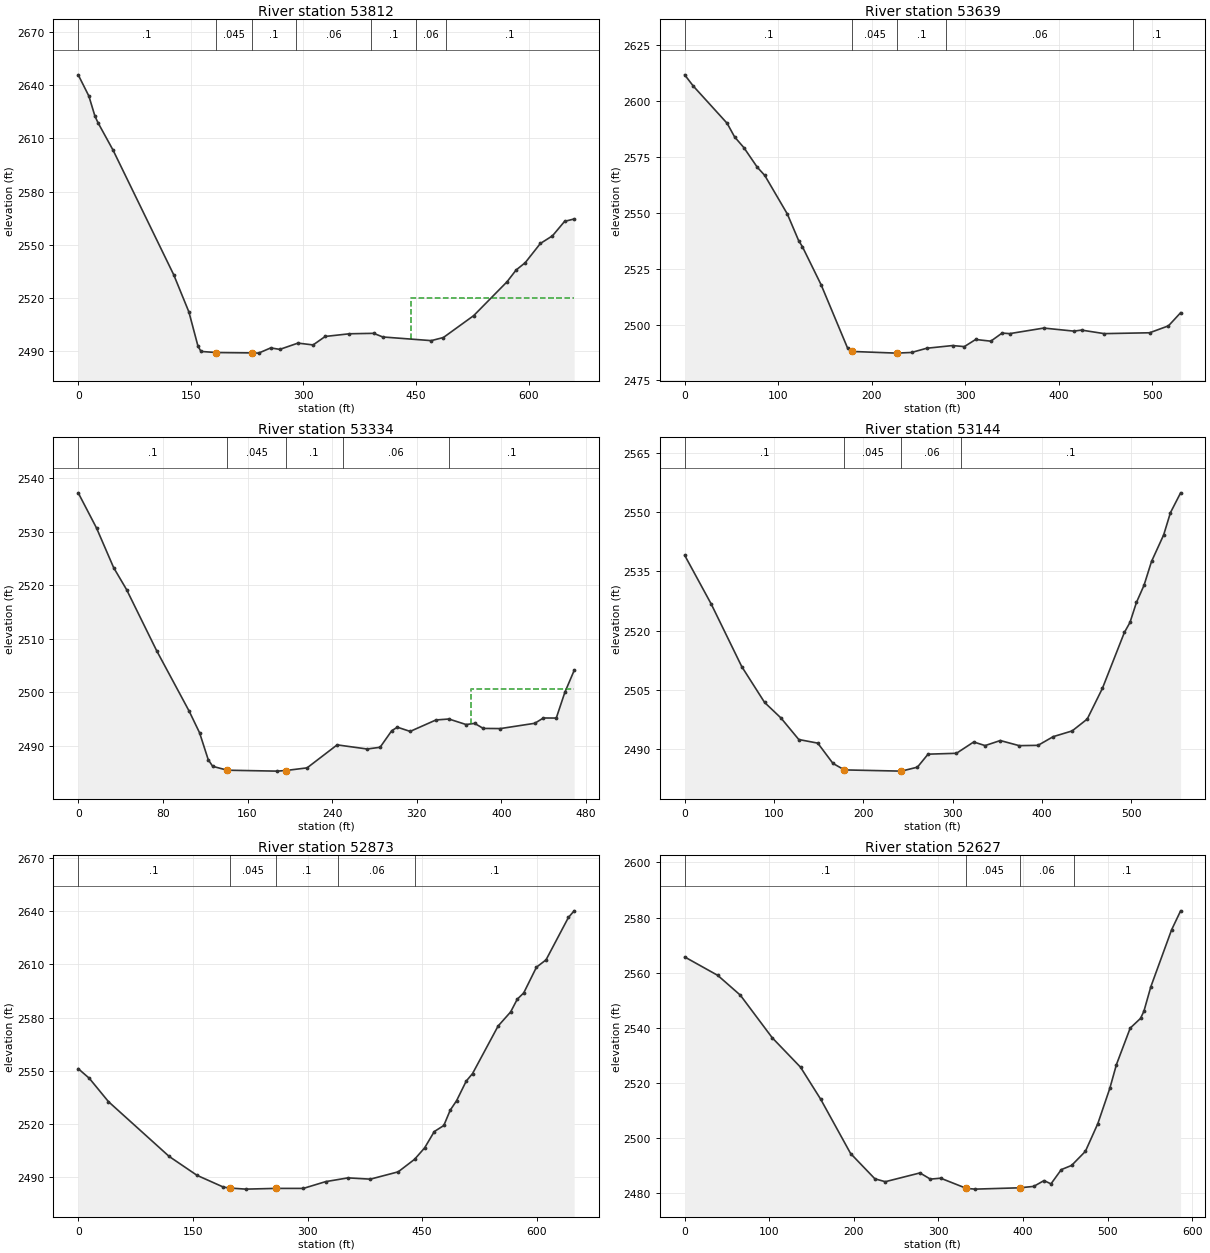
Type RM Length L Ch R = 1 ,53812   ,178.3,173.2,166.2
XS GIS Cut Line= 2
2358845.94637875703543.2736954872358935.47460813702888.598518128
#Sta/Elev= 30
       0 2646.02    14.2 2634.01    22.3 2622.63    26.3 2618.98    46.5 2603.35
   127.3 2532.86   147.5 2511.84   159.6 2492.49   163.6 2489.53   183.8  2488.9
   232.2 2488.69   240.3 2488.57   256.5 2491.52   268.6 2490.69   292.8 2494.24
     313 2493.21   329.1    2498   361.4 2499.52   393.7 2499.77   405.8 2497.71
   470.4 2495.64   486.6 2497.41     527 2509.81   571.4 2528.95   583.5 2535.61
   595.6 2539.73   615.8 2550.61   631.9 2554.93   648.1 2563.12   660.8 2564.47
#Mann= 7 ,-1,0
       0      .1       0   183.8    .045       0   232.2      .1       0
     290     .06       0     390      .1       0     450     .06       0
     490      .1       0
#XS Ineff= 2 , 0
                          443.98         2520.03
Permanent Ineff=
       F       F
Bank Sta=183.8,232.2
XS Rating Curve= 0 ,0
Exp/Cntr(USF)=0,0
Exp/Cntr=0.3,0.1

Type RM Length L Ch R = 1 ,53639   ,306.4,304.2,304.6
XS GIS Cut Line= 3
2359069.61014073703534.2514739382359035.13291522703236.914470117
2359001.50030228 703008.32506852
#Sta/Elev= 30
       0 2611.83     9.1 2606.85    45.4 2590.13    53.4 2584.03    63.4 2579.19
    77.6 2570.48    85.6 2566.83   109.8 2549.52   121.9  2537.6   125.9  2534.9
     146 2517.76   174.2 2489.52   179.1 2487.99   226.6 2487.24   227.3 2487.26
   242.7 2487.54   258.8 2489.42   286.5 2490.63   299.1 2490.16   311.2 2493.35
   327.4 2492.59   339.5 2496.22   347.6 2495.97     384 2498.46   416.3 2497.09
   424.4 2497.55   448.7 2495.97   497.2 2496.35   517.4 2499.45   530.4 2505.33
#Mann= 5 ,-1,0
       0      .1       0   179.1    .045       0   227.3      .1       0
     280     .06       0  479.33      .1       0
Bank Sta=179.1,227.3
XS Rating Curve= 0 ,0
Exp/Cntr=0.3,0.1

Type RM Length L Ch R = 1 ,53334   ,195.2,190.3,187
XS GIS Cut Line= 2
2359366.32921204703406.1835942452359285.19425416702944.553661492
#Sta/Elev= 30
       0 2537.29    17.3 2530.71    33.5 2523.29    45.7 2519.19    74.1 2507.77
   104.9 2496.43   114.7  2492.4   122.9 2487.36   127.1 2486.13   140.9  2485.4
   187.8 2485.23     196 2485.34   216.3 2485.84   244.7 2490.14   273.1 2489.37
   285.3 2489.69   296.3 2492.79   301.6 2493.45   313.7 2492.66   338.1  2494.8
   350.3 2494.98   366.5 2493.95   374.7 2494.16   382.8 2493.22     399 2493.19
   431.5 2494.18   439.6 2495.17   451.8 2495.16   459.9 2499.96   468.7 2504.06
#Mann= 5 ,-1,0
       0      .1       0   140.9    .045       0     196      .1       0
     250     .06       0     350      .1       0
#XS Ineff= 2 , 0
                          370.83         2500.65
Permanent Ineff=
       F       F
Bank Sta=140.9,196
XS Rating Curve= 0 ,0
Exp/Cntr(USF)=0,0
Exp/Cntr=0.3,0.1

Type RM Length L Ch R = 1 ,53144   ,268.7,271.1,272.3
XS GIS Cut Line= 3
2359578.41079014703349.2413293922359459.92266088703024.780236969
2359390.69316956702826.393063586
#Sta/Elev= 30
       0 2539.12    29.8  2526.7    63.9 2510.85    89.5 2501.74   107.8  2497.8
   127.8 2492.32   149.1  2491.4   166.1 2486.25   178.9  2484.6   242.8 2484.29
   260.7  2485.3   272.6  2488.6   304.4 2488.82   323.7 2491.69   336.5 2490.78
   353.5 2492.06   374.7 2490.76   395.8 2490.84   412.8 2493.05     434  2494.5
   450.9 2497.52   467.9 2505.32   492.5 2519.51   498.8 2522.07     506 2527.13
   514.5 2531.49   522.9 2537.54   536.5 2544.29   544.1 2549.94   555.5 2554.98
#Mann= 4 ,-1,0
       0      .1       0   178.9    .045       0   242.8     .06       0
     310      .1       0
Bank Sta=178.9,242.8
XS Rating Curve= 0 ,0
Exp/Cntr=0.3,0.1

Type RM Length L Ch R = 1 ,52873   ,248.1,246.4,255
XS GIS Cut Line= 2
2359827.95914479703283.0822788442359640.50941452702661.980187504
#Sta/Elev= 30
       0 2551.22    14.5  2545.8    39.6 2532.61     119 2501.71   155.4 2491.06
     190 2484.41   198.4 2483.88   219.3 2483.27   258.1 2483.68   294.5 2483.68
   323.7  2487.5     353 2489.62   382.2  2488.9   418.6 2493.02     440 2500.08
   453.2 2506.55   465.8 2515.74   478.3 2519.18   486.7 2527.84     495 2533.16
   507.6 2544.21   515.9 2548.48   549.3 2575.27   565.7 2583.23   574.4 2590.43
   582.8 2593.94   599.5 2608.48     612  2612.6   641.3 2636.53   648.8 2640.27
#Mann= 5 ,-1,0
       0      .1       0   198.4    .045       0   258.1      .1       0
     340     .06       0     440      .1       0
Bank Sta=198.4,258.1
XS Rating Curve= 0 ,0
Exp/Cntr(USF)=0,0
Exp/Cntr=0.3,0.1

Type RM Length L Ch R = 1 ,52627   ,275.4,289.7,306.6
XS GIS Cut Line= 4
2359952.48361293703294.1560962442360027.95804888703148.770609943
2360002.33010598703035.4553391252359943.88616956702734.649254344
#Sta/Elev= 30
       0 2565.72    39.1 2559.04    65.8 2551.87   103.5 2536.44     137 2525.76
   160.7 2514.22   196.2 2494.48   224.9 2485.32   237.2 2484.27   278.2 2487.45
   290.5 2485.21   302.7 2485.54   333.2 2481.84   343.4 2481.58   396.1 2482.06
   412.7 2482.57   424.9 2484.68   433.1 2483.48   445.3 2488.65   457.5 2490.17
   473.8 2495.27   488.5 2505.32   502.7 2518.11   510.5 2526.71   526.8 2539.94
     539 2543.45     543 2546.06   551.2 2554.94   575.7 2575.53   586.4 2582.43
#Mann= 4 ,-1,0
       0      .1       0   333.2    .045       0   396.1     .06       0
  459.99      .1       0
Bank Sta=333.2,396.1
XS Rating Curve= 0 ,0
Exp/Cntr=0.3,0.1

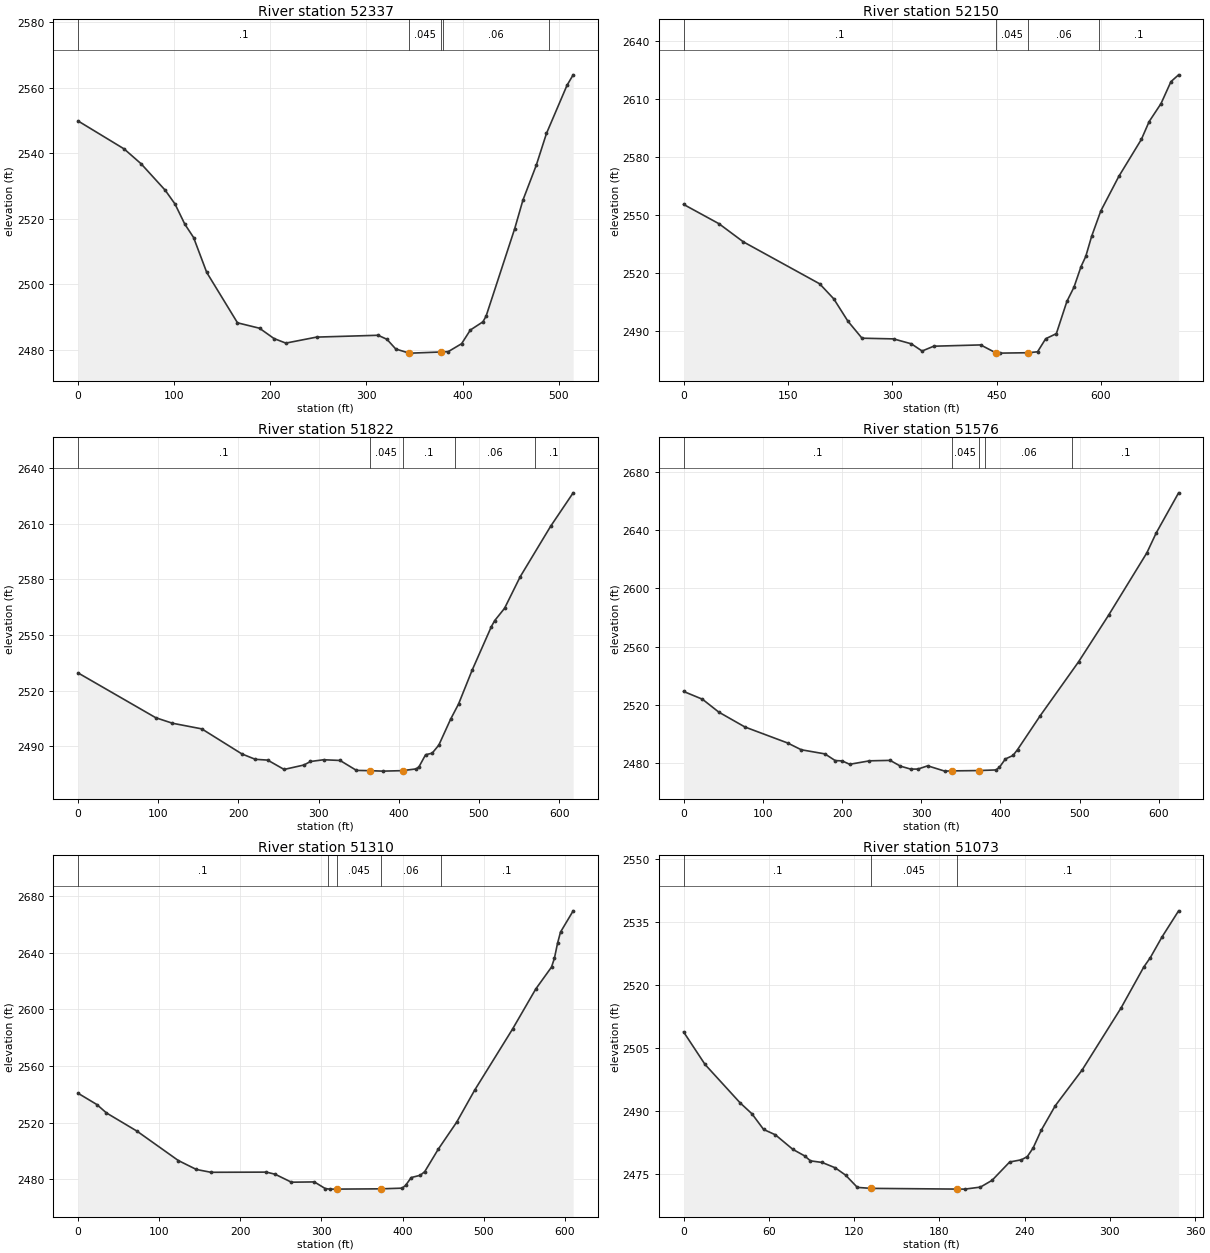
Type RM Length L Ch R = 1 ,52337   ,184,187.2,191.5
XS GIS Cut Line= 2
2360096.32305959703290.2996139832360345.60322328702839.580934186
#Sta/Elev= 30
       0 2549.87    47.8 2541.36    65.5 2536.82    90.6 2528.74   100.8 2524.53
     111 2518.38   120.1 2514.32   133.8 2503.65   165.8 2488.28   188.7 2486.63
   203.8 2483.48   216.1 2482.09   248.1 2483.92   312.1 2484.48   321.3 2483.25
   330.5 2480.29   344.1 2479.06   346.8 2479.03   377.4 2479.38   385.2  2479.5
     399 2481.91   408.1 2486.08   421.2 2488.59   424.5 2490.33   454.3 2517.06
   462.8 2525.71   476.7 2536.37   487.3 2546.07   508.7 2560.78   515.1 2563.97
#Mann= 5 ,-1,0
       0      .1       0   344.1    .045       0   377.4      .1       0
     380     .06       0     490      .1       0
Bank Sta=344.1,377.4
XS Rating Curve= 0 ,0
Exp/Cntr(USF)=0,0
Exp/Cntr=0.3,0.1

Type RM Length L Ch R = 1 ,52150   ,316.8,327.4,346.2
XS GIS Cut Line= 3
2360105.81860293703379.1527815882360231.51159111703322.692361493
     2360585.147      702870.695
#Sta/Elev= 30
       0 2555.58    50.8  2545.6    85.9  2536.2   195.6 2514.49   215.9  2506.7
   236.2 2495.15   256.5 2486.33   301.8 2485.97   327.4 2483.42   342.9 2479.69
   359.6 2482.18   427.1 2482.85   449.5 2478.63   454.6  2478.6   495.2 2478.81
   508.9 2479.29   520.6 2486.06   535.9 2488.67   551.1  2505.4   561.3 2512.76
   571.4 2523.39   578.2 2528.65   586.6 2539.02   599.8 2552.18   625.7 2570.07
   658.2 2589.27   669.3 2598.44   686.4 2607.77   700.7 2619.15   711.7 2622.66
#Mann= 4 ,-1,0
       0      .1       0   449.5    .045       0   495.2     .06       0
  597.79      .1       0
Bank Sta=449.5,495.2
XS Rating Curve= 0 ,0
Exp/Cntr=0.3,0.1

Type RM Length L Ch R = 1 ,51822   ,241,246.4,263.9
XS GIS Cut Line= 2
2360229.77607652703423.752630907 2360831.5736434703285.263651081
#Sta/Elev= 30
       0 2529.49    96.9 2505.31   117.6 2502.36   154.2 2499.31   204.3 2485.77
     221 2482.88   236.4 2482.45   256.9 2477.41   281.6  2479.8   289.8  2481.7
   306.2 2482.64   326.7 2482.26   347.2 2476.89   363.7 2476.75   380.1  2476.5
   404.6 2476.76   421.7 2477.71   425.2 2478.88   433.4 2485.36   441.6 2486.19
   449.9 2490.56   464.6 2504.53   474.5 2512.72   491.3 2530.84   515.5 2554.57
   519.6 2557.77   531.9  2564.4   551.4 2581.44   589.4 2608.71   617.5 2626.75
#Mann= 5 ,-1,0
       0      .1       0   363.7    .045       0   404.6      .1       0
     470     .06       0     570      .1       0
Bank Sta=363.7,404.6
XS Rating Curve= 0 ,0
Exp/Cntr(USF)=0,0
Exp/Cntr=0.3,0.1

Type RM Length L Ch R = 1 ,51576   ,262.3,266.4,278.1
XS GIS Cut Line= 4
2360225.07066837703462.8869988042360362.39122219703498.004115016
2360481.13570485703547.7578330622360810.45790726703679.114666125
#Sta/Elev= 30
       0 2529.29    23.8 2523.94    44.5 2515.08    77.5 2504.87   131.2 2493.94
   148.6 2489.25   178.4 2486.42   191.4 2481.84   200.1 2481.62   209.7 2479.28
   234.7 2481.66   260.8 2481.97   273.8    2478   286.7 2475.98   295.9    2476
   308.2 2478.23   329.7 2474.59   338.4 2474.75   372.8 2474.98   394.3 2475.41
   398.6 2477.09   406.3 2482.96   415.9 2485.33   421.7 2489.42   450.3 2512.65
   498.7 2549.64   536.5 2581.55   584.9 2624.42   596.7 2638.08     625 2665.63
#Mann= 5 ,-1,0
       0      .1       0   338.4    .045       0   372.8      .1       0
  380.49     .06       0  490.49      .1       0
Bank Sta=338.4,372.8
XS Rating Curve= 0 ,0
Exp/Cntr=0.3,0.1

Type RM Length L Ch R = 1 ,51310   ,228.5,236.7,255.6
XS GIS Cut Line= 3
2360101.43260131703597.1724309662360305.38909887703697.891689021
2360572.29513272 703972.35166722
#Sta/Elev= 30
       0 2540.68      23 2532.77    34.9 2526.81    72.3 2514.03   123.5 2493.17
   145.8 2486.84   163.7 2484.86   232.1 2484.98   242.9 2483.47   262.9 2477.86
   291.2 2478.06   304.6 2473.36   310.2 2472.96   319.5 2472.98   373.2 2473.17
   399.4 2473.65   403.6 2475.54   410.6 2481.14   421.8 2482.75   427.3 2485.34
   443.9 2501.13   466.7 2520.32   488.7 2542.78   535.6 2586.14   564.2 2614.45
   583.6  2629.9   587.2 2636.19     591 2646.66   594.7 2654.65   610.3 2669.67
#Mann= 5 ,-1,0
       0      .1       0  307.47     .06       0   319.5    .045       0
   373.2     .06       0  447.47      .1       0
Bank Sta=319.5,373.2
XS Rating Curve= 0 ,0
Exp/Cntr(USF)=0,0
Exp/Cntr=0.3,0.1

Type RM Length L Ch R = 1 ,51073   ,167.8,165.4,160.7
XS GIS Cut Line= 2
2360117.38768709703674.5607180872360202.12111711 704012.46526155
#Sta/Elev= 30
       0 2508.79    15.1 2501.06    39.8 2491.93    48.1 2489.34    56.3 2485.62
    64.6 2484.34    76.9 2480.88    85.2 2479.33    89.3 2478.15    97.5 2477.77
   106.7  2476.5     114 2474.76   122.3 2471.84   131.9 2471.61   192.4 2471.44
   197.9 2471.43   208.9 2471.91   217.1 2473.52   229.5 2477.88   237.8 2478.41
   241.9 2479.16     246 2481.21   251.7 2485.42   261.6 2491.26   280.5 2499.75
   307.9  2514.5   323.9 2524.23   328.5 2526.46   336.7 2531.36   348.4 2537.58
#Mann= 3 ,-1,0
       0      .1       0   131.9    .045       0   192.4      .1       0
Bank Sta=131.9,192.4
XS Rating Curve= 0 ,0
Exp/Cntr(USF)=0,0
Exp/Cntr=0.3,0.1

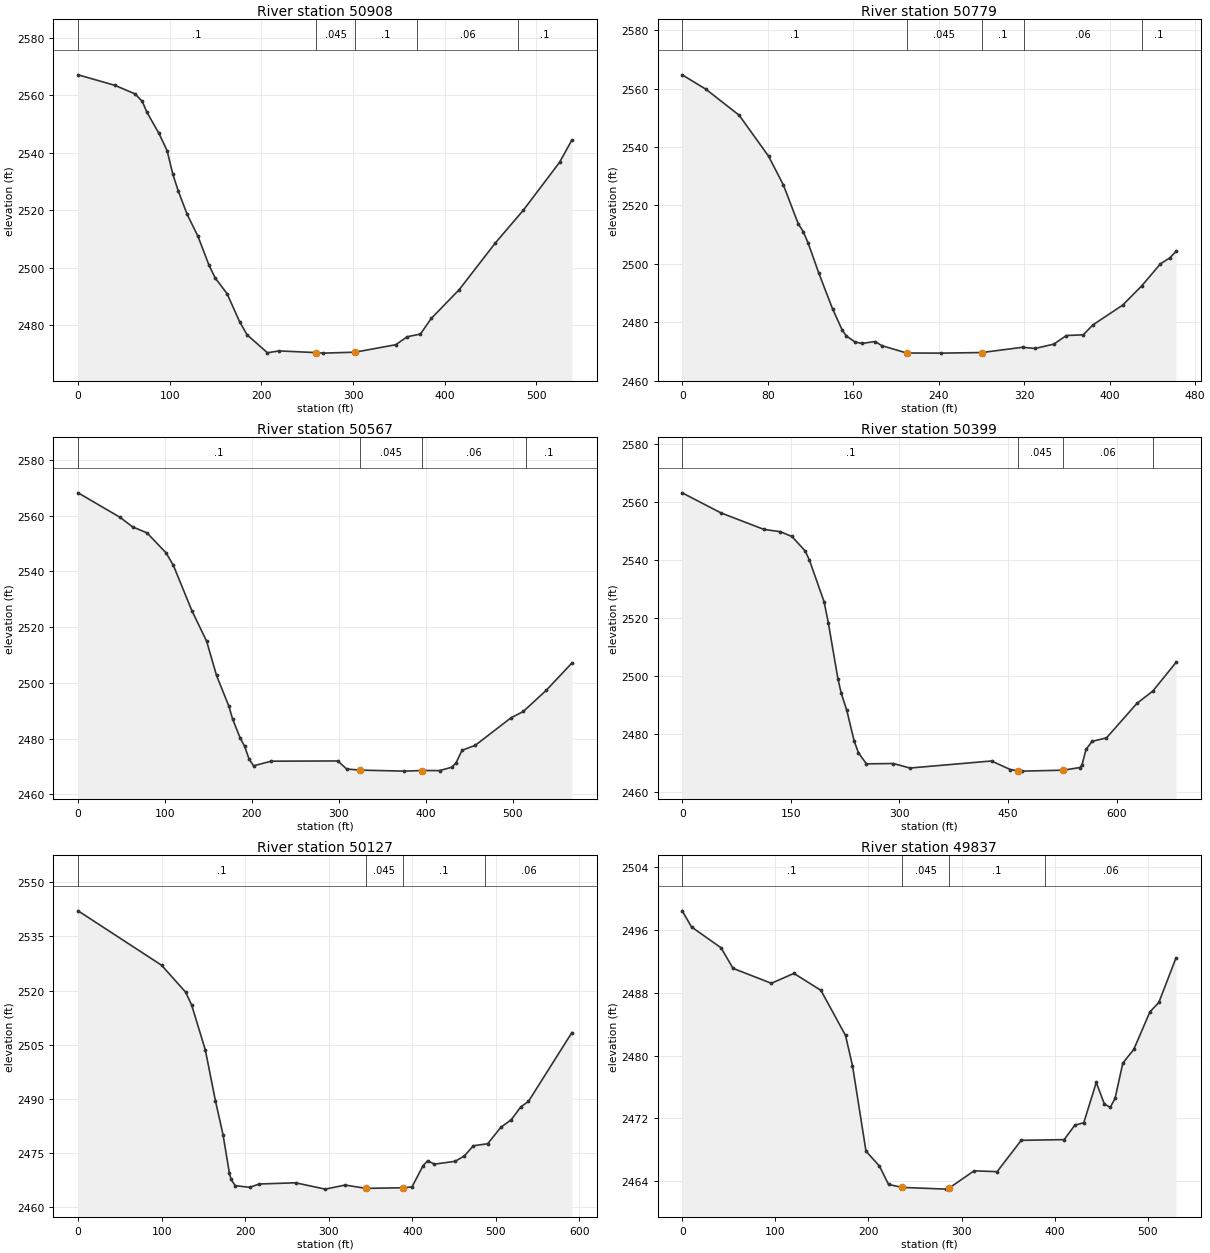
Type RM Length L Ch R = 1 ,50908   ,137.8,128.4,123.3
XS GIS Cut Line= 2
2359884.88619649703612.2803196742360101.43260131704105.804684143
#Sta/Elev= 30
       0 2567.09    40.3 2563.42    62.1 2560.47      70 2557.87    75.2 2554.01
    88.2 2546.74    97.1 2540.75   103.4 2532.51   109.4 2526.62   118.9 2518.65
   130.7 2511.02   142.8 2500.94   149.5 2496.51   162.6 2490.98   176.2 2481.27
   184.4 2476.68   206.6 2470.44   219.4 2471.08     260 2470.49   267.3 2470.31
   302.4 2470.64   346.7 2473.24   359.2 2476.01   373.6 2476.95   385.4 2482.36
     416 2492.42   455.5 2508.67     486 2520.05   525.4 2536.64   538.9 2544.42
#Mann= 5 ,-1,0
       0      .1       0     260    .045       0   302.4      .1       0
     370     .06       0     480      .1       0
Bank Sta=260,302.4
XS Rating Curve= 0 ,0
Exp/Cntr(USF)=0,0
Exp/Cntr=0.3,0.1

Type RM Length L Ch R = 1 ,50779   ,216.2,212.2,205.5
XS GIS Cut Line= 2
 2359748.3817624703674.7564227912359976.34930994704076.664265134
#Sta/Elev= 30
       0  2564.7    22.2 2559.77    53.4 2550.84    80.9  2536.8    94.8 2526.92
   108.6 2513.71   113.2 2511.07   117.8  2507.2   127.8 2496.88   140.7 2484.62
   149.9 2477.22   153.6 2475.34   161.7 2473.24   168.3 2472.76   180.6 2473.41
   186.7 2472.02     210 2469.49   241.9 2469.44   280.4 2469.64   318.5 2471.44
   330.3 2471.04   347.7 2472.51   359.6 2475.47   375.3 2475.71   384.5 2479.14
   412.1 2485.84     430 2492.45   447.6 2500.01   456.4 2502.05   462.1 2504.26
#Mann= 5 ,-1,0
       0      .1       0     210    .045       0   280.4      .1       0
     320     .06       0     430      .1       0
Bank Sta=210,280.4
XS Rating Curve= 0 ,0
Exp/Cntr(USF)=0,0
Exp/Cntr=0.3,0.1

Type RM Length L Ch R = 1 ,50567   ,173.6,167.4,162.6
XS GIS Cut Line= 3
2359541.03345243 703714.473157382359605.11971327703888.004642673
2359842.86592564704188.305638533
#Sta/Elev= 30
       0 2568.19    48.1 2559.43    62.6 2555.99    79.3 2553.81     101 2546.71
   109.5 2542.24   130.8 2525.97   147.9 2514.91   159.2 2502.69   173.4 2491.65
   177.7 2487.05   186.5 2480.18   191.6 2477.22   196.7 2472.65   201.8 2470.25
   222.2 2471.91   298.7 2471.99   308.9  2469.1   324.7  2468.7   375.3 2468.34
   395.9 2468.56   415.8 2468.53     430 2469.75   434.8 2471.31   441.6 2475.81
   456.9 2477.61   497.7 2487.41   512.1 2489.74   538.5 2497.33     568 2507.12
#Mann= 4 ,-1,0
       0      .1       0   324.7    .045       0   395.9     .06       0
  514.99      .1       0
Bank Sta=324.7,395.9
XS Rating Curve= 0 ,0
Exp/Cntr=0.3,0.1

Type RM Length L Ch R = 1 ,50399   ,269,272.9,279.4
XS GIS Cut Line= 2
2359228.28189777703809.0049507422359731.87818805704269.080573957
#Sta/Elev= 30
       0 2563.21    53.6 2556.27   112.9 2550.57   135.3 2549.79   151.6 2548.13
   169.9 2543.12   175.6 2540.06     196 2525.58   201.9 2518.26   215.2 2498.83
   219.7 2493.96   227.4 2488.01   237.5 2477.52   243.5 2473.34   254.5 2469.56
   291.7 2469.67   314.6 2468.11   427.3 2470.55   453.1 2467.59   464.4 2467.15
     470 2467.04   526.7 2467.37   549.3 2468.28   552.2  2469.1   557.8 2474.53
   566.3 2477.33   586.1 2478.52   628.3 2490.49     650 2494.67   682.1 2504.58
#Mann= 4 ,-1,0
       0      .1       0   464.4    .045       0   526.7     .06       0
     650      .1       0
Bank Sta=464.4,526.7
XS Rating Curve= 0 ,0
Exp/Cntr(USF)=0,0
Exp/Cntr=0.3,0.1

Type RM Length L Ch R = 1 ,50127   ,297.2,289.9,283.6
XS GIS Cut Line= 4
2359210.97223409703934.1527214782359232.46259888  704099.8893768
2359310.51586743704216.0975171822359504.74136824704423.117685745
#Sta/Elev= 30
       0 2542.09    99.9 2527.01   128.7 2519.54   135.9 2515.98   152.3 2503.49
   164.3 2489.49   173.5 2479.99     181 2469.46   183.1 2467.63     188  2465.9
   205.3 2465.43   216.9 2466.35   260.2 2466.69   295.7 2464.93   319.6 2466.06
   344.6 2465.14   388.3 2465.31   399.6 2465.54   412.8 2471.39   418.3 2472.79
   426.5 2471.86   451.2 2472.64   462.2 2474.11   473.1 2476.96   490.2 2477.51
     506 2482.08   518.5 2484.18   529.8 2487.73     539 2489.24     591 2508.33
#Mann= 4 ,-1,0
       0      .1       0   344.6    .045       0   388.3      .1       0
  487.11     .06       0
Bank Sta=344.6,388.3
XS Rating Curve= 0 ,0
Exp/Cntr=0.3,0.1

Type RM Length L Ch R = 1 ,49837   ,176.8,178.9,182.7
XS GIS Cut Line= 2
2358877.00794221704222.4512878212359315.32323189704520.878719095
#Sta/Elev= 30
       0 2498.42      10 2496.37    41.7 2493.72    54.6  2491.1    95.8  2489.2
     120 2490.46     149  2488.3   175.4 2482.57   182.9 2478.72   197.4 2467.84
   211.9 2465.93   221.6 2463.61   236.1 2463.23   283.5 2463.01   286.4 2463.12
   313.5 2465.34   338.2 2465.23   364.1 2469.22   410.2 2469.31   421.7 2471.15
   431.3 2471.46   444.7 2476.58   453.4 2473.85   459.7 2473.41   464.9 2474.56
   473.2 2479.04     485 2480.79   502.3 2485.56   511.9 2486.76   530.3 2492.42
#Mann= 4 ,-1,0
       0      .1       0   236.1    .045       0   286.4      .1       0
     390     .06       0
Bank Sta=236.1,286.4
XS Rating Curve= 0 ,0
Exp/Cntr(USF)=0,0
Exp/Cntr=0.3,0.1

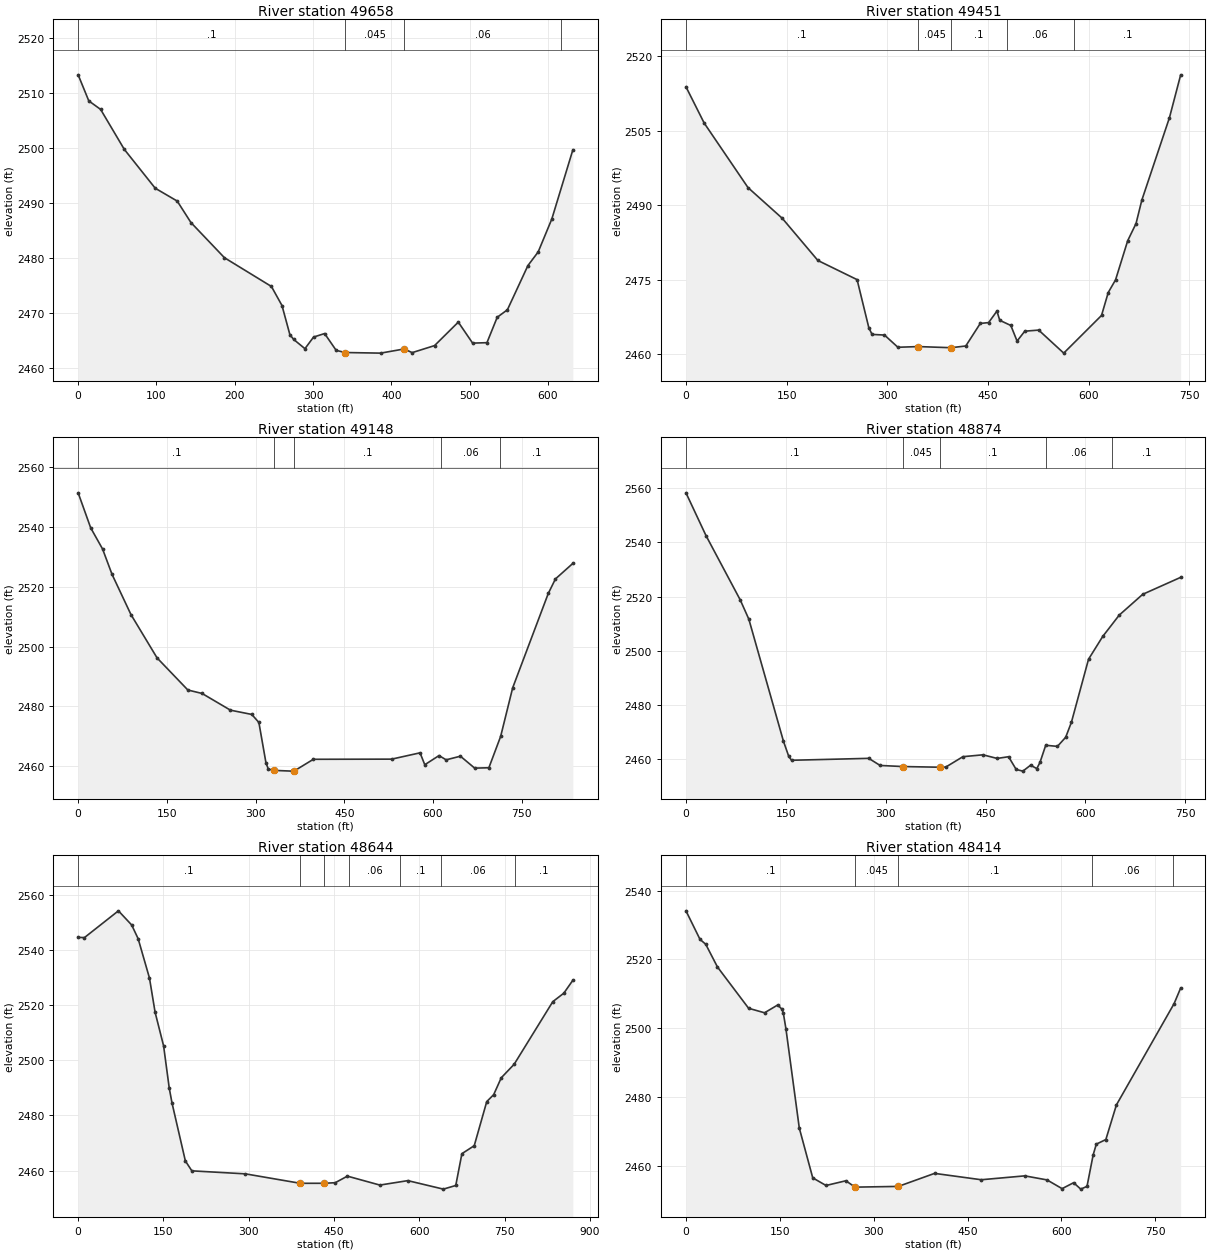
Type RM Length L Ch R = 1 ,49658   ,189.4,206.3,221.6
XS GIS Cut Line= 3
2358701.38909538 704294.052095972359063.78161967704571.109428909
2359224.86036931704640.866212686
#Sta/Elev= 30
       0 2513.25    13.6 2508.51    28.7 2506.96    58.9  2499.7    98.4 2492.63
   126.5 2490.29     144 2486.39   186.8 2479.99   246.8 2474.76   260.3 2471.29
   270.4 2465.98   275.3 2465.12   289.6 2463.45   300.6 2465.56   314.7  2466.2
   329.5 2463.14     341 2462.75   386.2 2462.64   416.4  2463.4   426.5 2462.73
   455.1 2464.01   485.4 2468.28   503.7 2464.46     522 2464.54   535.1 2469.16
   548.1 2470.52   574.3 2478.56   587.4 2481.04   604.8 2487.02   631.7 2499.61
#Mann= 4 ,-1,0
       0      .1       0     341    .045       0   416.4     .06       0
  616.17      .1       0
Bank Sta=341,416.4
XS Rating Curve= 0 ,0
Exp/Cntr=0.3,0.1

Type RM Length L Ch R = 1 ,49451   ,322.5,303.2,280.8
XS GIS Cut Line= 4
2358544.87277021704426.955401728 2358815.3226298704588.603593668
2358861.95191594704691.1880231692359160.37934721704772.012119139
#Sta/Elev= 30
       0 2513.83    27.1 2506.53    92.4 2493.53   143.6 2487.32   196.5 2478.85
   254.9 2474.99   272.4 2465.29   277.2 2463.96   295.7 2463.83   315.7 2461.37
   346.1 2461.51   394.8 2461.28   416.8 2461.63   438.4 2466.17   450.8 2466.34
   463.2 2468.66   467.4  2466.8   483.9 2465.76   493.2 2462.62   504.7 2464.61
   525.4 2464.83   562.7 2460.19     619 2467.78     629  2472.4   639.9 2474.95
     658 2482.84   670.4 2486.29     679 2490.99   720.2 2507.62   736.9 2516.24
#Mann= 5 ,-1,0
       0      .1       0   346.1    .045       0   394.8      .1       0
  477.76     .06       0  577.76      .1       0
Bank Sta=346.1,394.8
XS Rating Curve= 0 ,0
Exp/Cntr(USF)=0,0
Exp/Cntr=0.3,0.1

Type RM Length L Ch R = 1 ,49148   ,281.8,274.7,267.4
XS GIS Cut Line= 3
2358294.95280983704810.3911901672358818.37766824704836.465238152
2359129.55771091704864.275905212
#Sta/Elev= 30
       0 2551.46    21.2 2539.75    41.3 2532.67    57.3 2524.19    89.3 2510.74
   133.4 2496.26   185.5 2485.51   209.5 2484.36   257.5 2478.77   293.6 2477.34
   305.6 2474.65   317.6 2461.12   321.6 2459.05   331.9 2458.62   361.7 2458.38
   365.7 2458.48   397.7 2462.34   530.1 2462.39   578.1  2464.5   586.1 2460.52
   610.2 2463.58   622.2 2462.16   646.4 2463.37   670.5 2459.38   694.5 2459.51
   714.4 2469.99   734.7 2486.22   794.9 2517.79     807 2522.65   836.5 2527.86
#Mann= 5 ,-1,0
       0      .1       0   331.9    .045       0   365.7      .1       0
  614.07     .06       0  714.07      .1       0
Bank Sta=331.9,365.7
XS Rating Curve= 0 ,0
Exp/Cntr=0.3,0.1

Type RM Length L Ch R = 1 ,48874   ,235.7,230.1,222
XS GIS Cut Line= 2
2358408.09353087705210.3274088232359101.31558477704942.986168307
#Sta/Elev= 30
       0 2558.25    30.1 2542.48    81.4 2518.83    94.4  2511.7   146.4 2466.71
   154.4 2461.09   158.6 2459.68   274.5 2460.39   291.6 2457.77   325.6 2457.37
   381.2 2457.12   390.2 2457.17   415.9    2461     446 2461.69   467.4 2460.36
   484.5 2460.99     496 2456.28     506 2455.68   517.6 2457.87   526.9 2456.61
   531.7 2458.89   540.3 2465.21   557.9  2464.8   570.3 2468.16   578.9 2473.69
   604.6 2496.92   625.9 2505.31   650.7 2513.18     686 2520.85     743  2527.1
#Mann= 5 ,-1,0
       0      .1       0   325.6    .045       0   381.2      .1       0
     540     .06       0     640      .1       0
Bank Sta=325.6,381.2
XS Rating Curve= 0 ,0
Exp/Cntr(USF)=0,0
Exp/Cntr=0.3,0.1

Type RM Length L Ch R = 1 ,48644   ,243.7,229.7,204.2
XS GIS Cut Line= 4
     2358543.187       705503.712358773.72696762 705334.04190521
 2359024.0071545705164.7480089012359214.37586547704957.475561083
#Sta/Elev= 30
       0 2544.53    11.1 2544.46    70.8 2554.16    94.1 2549.03   105.5 2544.04
   125.4 2529.78   135.3 2517.37   150.2 2505.23   160.2 2489.82   165.1 2484.41
   188.5 2463.47   199.9 2459.88     294 2458.79   390.6 2455.36   432.7 2455.37
     452 2455.58   473.4 2457.96   530.5 2454.72   579.6 2456.33   642.1 2453.25
   663.9 2454.57   674.7  2466.1   696.4    2469   718.4 2484.99   730.6 2487.51
   743.9 2493.62   766.6 2498.53   834.5 2521.22   853.9  2524.3   869.8 2528.98
#Mann= 7 ,-1,0
       0      .1       0   390.6    .045       0   432.7      .1       0
  476.24     .06       0  566.24      .1       0   638.4     .06       0
   768.4      .1       0
Bank Sta=390.6,432.7
XS Rating Curve= 0 ,0
Exp/Cntr=0.3,0.1

Type RM Length L Ch R = 1 ,48414   ,296.9,289.4,275.5
XS GIS Cut Line= 3
2358921.01567838705710.8150800232359064.01215586705328.454933703
2359290.94134839705020.701645201
#Sta/Elev= 30
       0 2534.15    22.4 2525.86    31.6 2524.42    50.3 2517.82   100.1  2505.8
   125.6 2504.49   146.7 2506.77   152.9  2505.6   155.5 2504.52   159.8 2499.78
   181.1 2470.96   202.6 2456.47   223.8 2454.25   255.5 2455.62   270.3 2453.77
   339.4 2453.98   397.3 2457.77   471.9 2455.92   541.5 2457.05     577 2455.87
   601.1 2453.33   619.5 2455.06   630.9 2453.19   640.9 2453.99   650.8  2463.2
   655.8 2466.28     671 2467.61   687.9 2477.69   780.1 2507.16   790.6 2511.71
#Mann= 5 ,-1,0
       0      .1       0   270.3    .045       0   339.4      .1       0
  648.22     .06       0  778.22      .1       0
Bank Sta=270.3,339.4
XS Rating Curve= 0 ,0
Exp/Cntr(USF)=0,0
Exp/Cntr=0.3,0.1

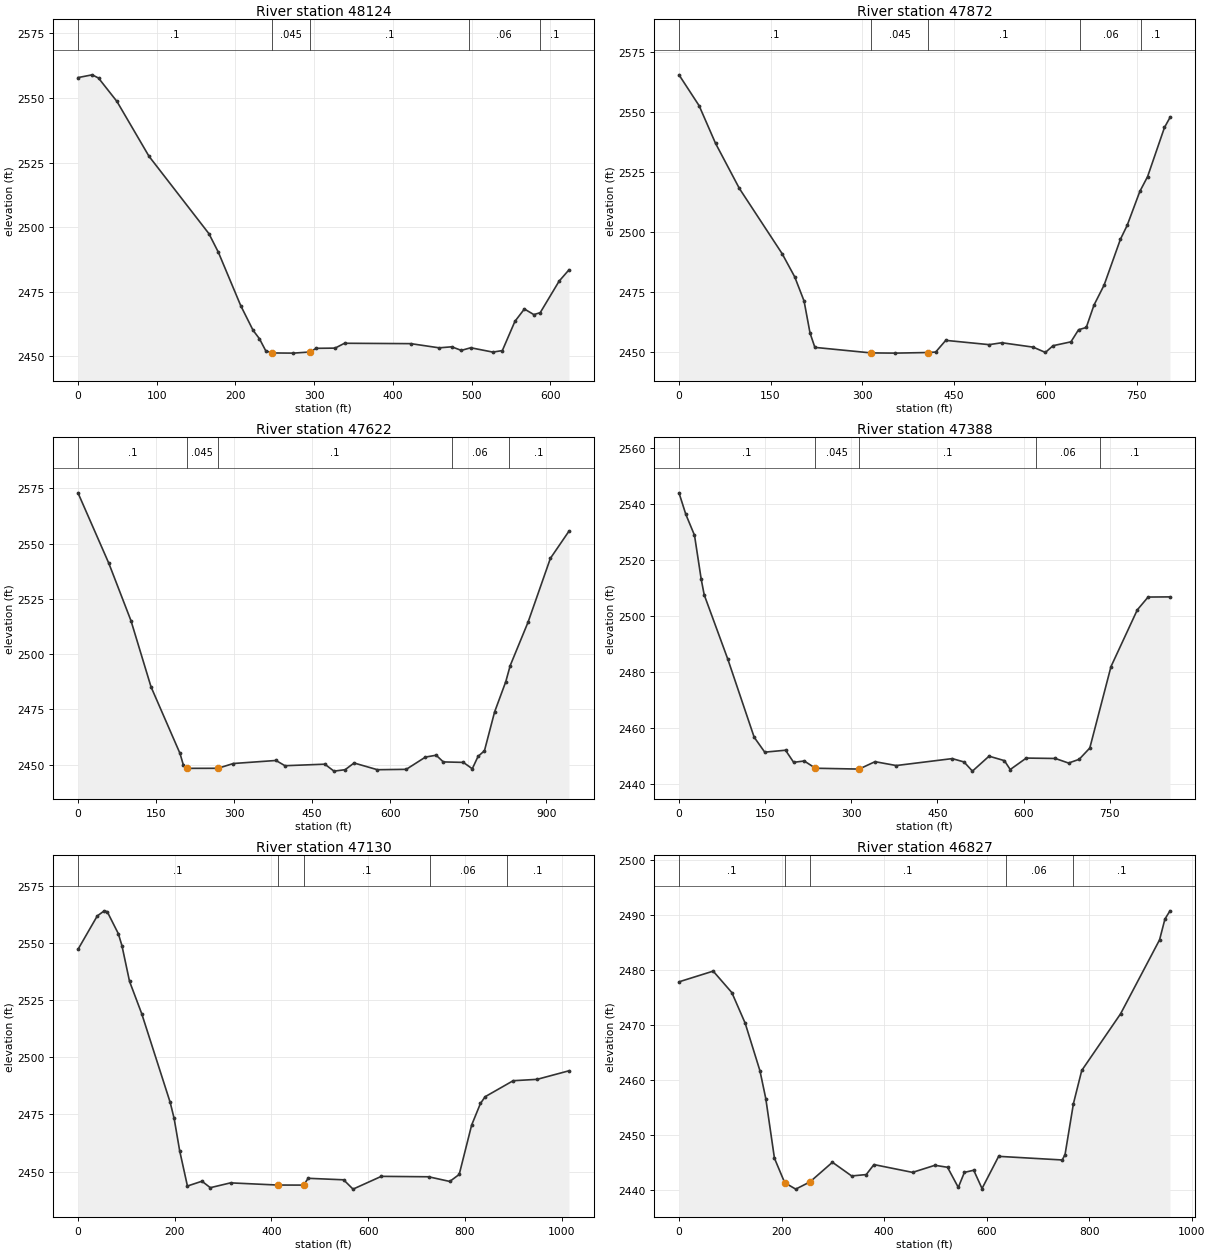
Type RM Length L Ch R = 1 ,48124   ,247.3,252.4,275.4
XS GIS Cut Line= 3
 2359296.9187401705715.2423669272359320.52047463705269.487064078
2359331.54253257705092.724404236
#Sta/Elev= 30
       0  2557.9    18.1 2558.97    26.1 2557.72    49.5 2548.66    90.2 2527.44
   166.3 2497.47   178.3 2490.27   206.7  2469.6   222.4 2460.04   230.4 2456.82
   238.4 2452.16   246.4 2451.29   273.7 2451.22   294.5 2451.66   302.5 2453.08
   326.5 2453.16   338.5 2455.04   422.7 2454.89   458.7 2453.27   474.7 2453.67
   486.8 2452.28   498.8  2453.3   526.8 2451.62   538.9  2452.2   554.9 2463.53
   566.9 2468.31   578.9 2466.14     587 2466.88     611 2479.09   623.5 2483.46
#Mann= 5 ,-1,0
       0      .1       0   246.4    .045       0   294.5      .1       0
  496.38     .06       0  586.38      .1       0
Bank Sta=246.4,294.5
XS Rating Curve= 0 ,0
Exp/Cntr=0.3,0.1

Type RM Length L Ch R = 1 ,47872   ,245.7,249.9,269.6
XS GIS Cut Line= 3
2359479.41544633 705757.185691112359588.52797589 705323.53333004
2359694.84274828704982.206955519
#Sta/Elev= 30
       0 2565.34      33 2552.49    59.9 2536.84      99 2518.05   169.1  2490.9
   189.7 2481.26     205 2471.22   214.8 2457.88   222.7 2451.93   314.6 2449.63
   354.7 2449.54   408.3  2449.8   420.7 2449.99   437.2 2454.85   508.3 2453.07
   529.2 2453.86   580.5 2452.03   600.5 2449.82     613 2452.63   642.4 2454.24
   654.9 2459.28   667.5 2460.21   680.1  2469.5   696.8 2477.89   723.5 2496.93
   734.5 2502.67   755.3 2516.83     768 2522.98   795.7 2543.44   804.7 2547.59
#Mann= 5 ,-1,0
       0      .1       0   314.6    .045       0   408.3      .1       0
  657.17     .06       0  757.17      .1       0
Bank Sta=314.6,408.3
XS Rating Curve= 0 ,0
Exp/Cntr(USF)=0,0
Exp/Cntr=0.3,0.1

Type RM Length L Ch R = 1 ,47622   ,243.2,234.3,225.1
XS GIS Cut Line= 3
2359671.29024322705801.0268019512359711.41135024705689.827768586
2360008.86728839704919.922366927
#Sta/Elev= 30
       0 2573.03    59.4 2541.09   101.9 2515.16   140.4 2485.25   196.1 2455.11
   202.8 2449.66     209 2448.37     269 2448.39   298.7 2450.56   380.5 2451.93
   397.8 2449.56   474.4 2450.25     492 2447.11   513.4 2447.75   530.6 2450.79
   575.4 2447.75   630.9 2447.92   667.8 2453.47   688.4 2454.31   702.1 2451.28
   740.7 2451.06   757.8 2448.18   768.9 2453.77   781.2 2456.33   800.7 2473.89
   822.2  2487.6   830.7 2494.87   865.1 2514.57   907.9 2543.38   943.6 2555.68
#Mann= 5 ,-1,0
       0      .1       0     209    .045       0     269      .1       0
  718.22     .06       0  828.22      .1       0
Bank Sta=209,269
XS Rating Curve= 0 ,0
Exp/Cntr=0.3,0.1

Type RM Length L Ch R = 1 ,47388   ,237.7,257.4,272.4
XS GIS Cut Line= 4
2359873.89920704705779.567748456 2359983.0117366705583.724746682
 2359983.0117366705485.8032457952360248.79866758705024.173313042
#Sta/Elev= 30
       0 2543.86    11.9 2536.19      27 2528.74    38.7 2513.05    43.9 2507.52
    85.2 2484.47   130.9 2456.77   149.3 2451.45   185.5 2452.14   199.6 2447.83
   218.1  2448.3   237.6 2445.72   313.6 2445.42   341.3 2448.06   378.2 2446.68
   475.7 2449.15   496.2 2447.96   510.9 2444.69   539.8 2450.02   566.5 2448.43
   576.7 2445.26   604.6 2449.34   655.2  2449.2   678.2 2447.57   696.7  2448.9
   715.2 2452.92   752.1 2481.94   797.9 2502.15   816.7 2506.72   854.8 2506.78
#Mann= 5 ,-1,0
       0      .1       0   237.6    .045       0   313.6      .1       0
  622.11     .06       0  732.11      .1       0
Bank Sta=237.6,313.6
XS Rating Curve= 0 ,0
Exp/Cntr(USF)=0,0
Exp/Cntr=0.3,0.1

Type RM Length L Ch R = 1 ,47130   ,286.2,303.8,296.5
XS GIS Cut Line= 3
  2359981.145164705922.2199715122360181.44083044705626.888034049
2360558.14038333705087.103208189
#Sta/Elev= 30
       0 2547.25    39.9  2561.9    54.4 2564.14    60.5 2563.77    83.4 2554.16
    90.9 2548.91   106.6 2533.28   131.8 2519.12   190.7 2480.25   198.8 2473.27
   210.3 2459.09   226.3 2443.68   256.4 2445.78   273.6 2442.95   315.4 2445.06
   412.6 2444.11   466.3 2444.08     476 2447.06   549.2  2446.4   568.7 2442.32
   627.2 2447.91   724.9 2447.73   768.7 2445.68   788.2 2448.75   813.9 2470.36
   832.1 2479.81   841.8 2482.77   899.8 2489.78   949.1 2490.37  1015.1 2494.12
#Mann= 5 ,-1,0
       0      .1       0   412.6    .045       0   466.3      .1       0
  726.85     .06       0  886.85      .1       0
Bank Sta=412.6,466.3
XS Rating Curve= 0 ,0
Exp/Cntr=0.3,0.1

Type RM Length L Ch R = 1 ,46827   ,311.5,314.8,322.7
XS GIS Cut Line= 3
2360145.28165236706000.5905647442360360.70895431705740.399148101
2360819.54112989 705323.53333004
#Sta/Elev= 30
       0 2477.88    66.7 2479.83   103.1 2475.92   129.1 2470.35   157.9 2461.69
   169.3 2456.62   186.2 2445.76   206.2  2441.3   227.7 2440.13   255.4 2441.44
   299.3 2445.02   336.8 2442.53   365.2 2442.78   380.3  2444.6   455.6 2443.18
   499.2 2444.47   523.8 2444.11   544.8 2440.44   556.7 2443.18   574.9 2443.57
   591.1 2440.24   623.5  2446.1   747.5 2445.44     753 2446.41   769.4 2455.71
   785.6 2461.74   861.3 2472.05   937.4 2485.53   947.8  2489.3   957.7 2490.81
#Mann= 5 ,-1,0
       0      .1       0   206.2    .045       0   255.4      .1       0
   637.8     .06       0   767.8      .1       0
Bank Sta=206.2,255.4
XS Rating Curve= 0 ,0
Exp/Cntr(USF)=0,0
Exp/Cntr=0.3,0.1