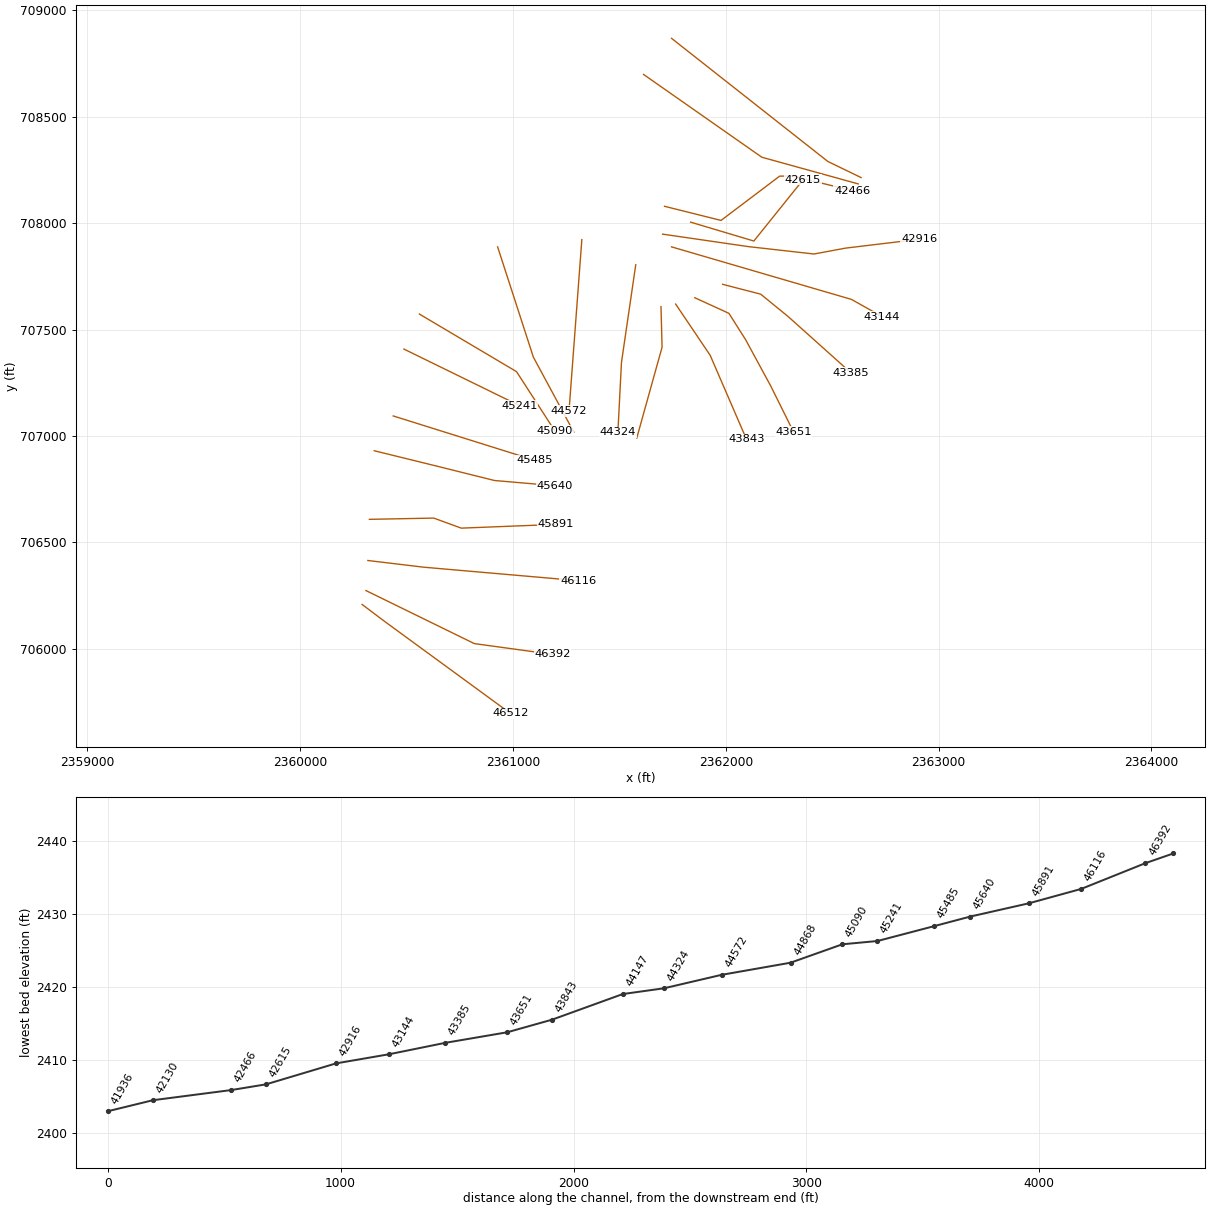
HEC-RAS study GLADYFK.prj: GLADYFK

--- GLADYFK.g01 (geometry) --- (continued)

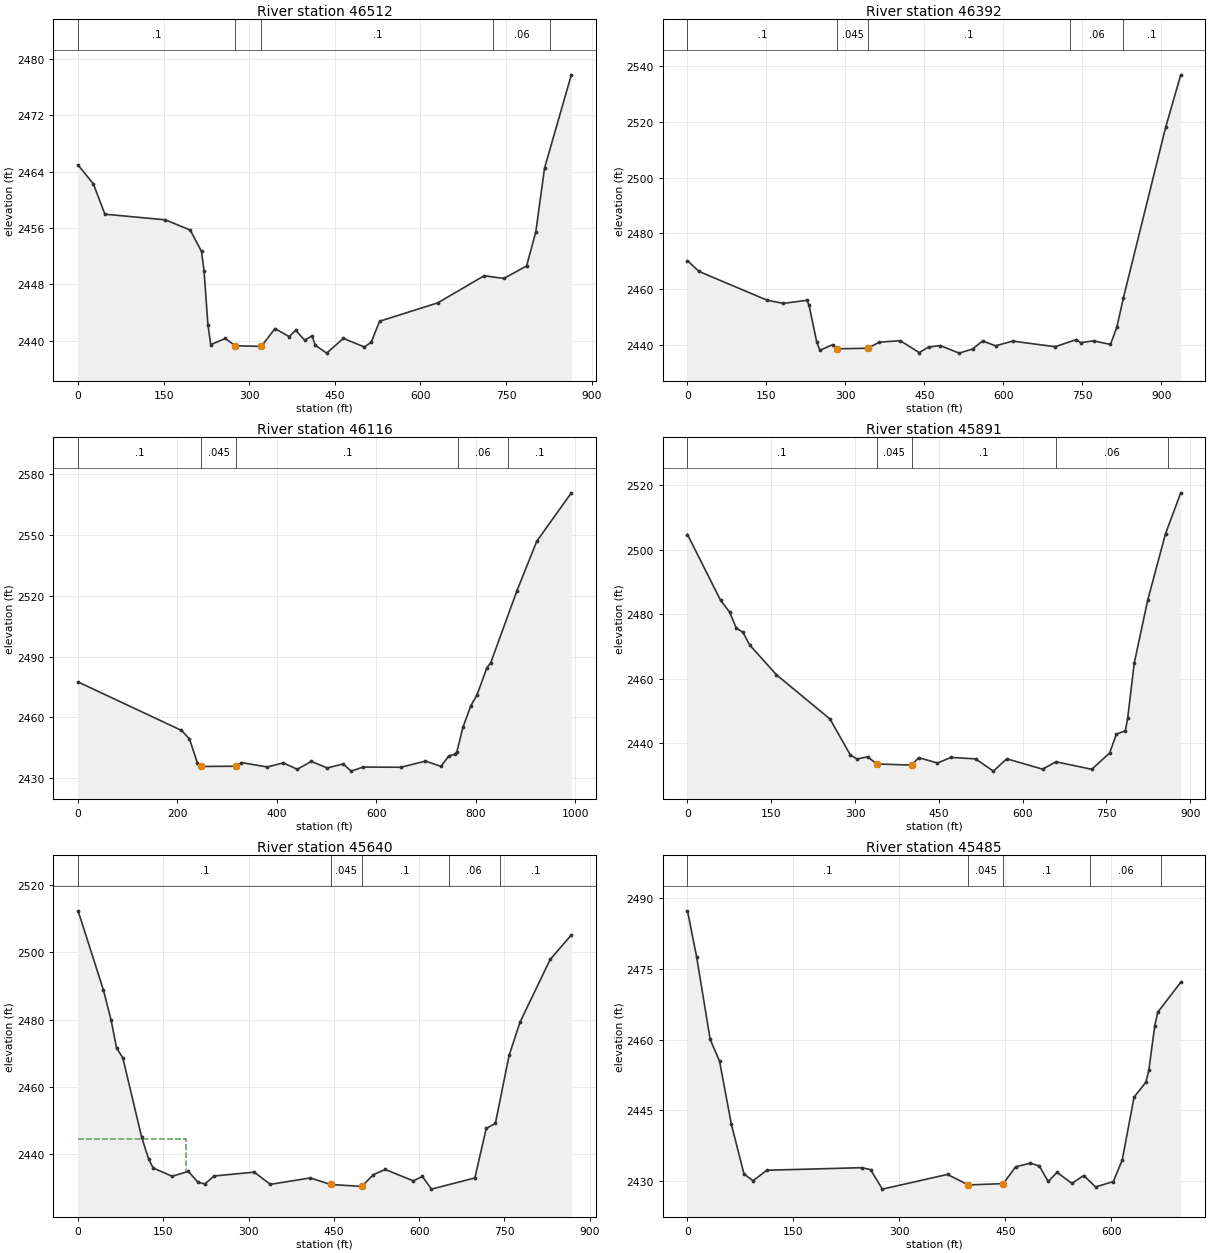
Type RM Length L Ch R = 1 ,46512   ,116.9,120,125.5
XS GIS Cut Line= 3
2360290.62727325706208.8678158142360400.57006348706126.299126019
2360987.53375815705697.475950986
#Sta/Elev= 30
       0 2464.92    26.9 2462.23      47 2457.95     153 2457.15   196.5  2455.7
   216.3 2452.66   220.8 2449.91   227.5 2442.29   232.5 2439.45   258.2 2440.33
   275.4 2439.29   321.2 2439.21   345.1 2441.74   369.8 2440.59   381.3 2441.49
   397.1 2440.09     410 2440.69   415.7 2439.37   435.7 2438.25   464.9 2440.34
   501.6 2439.13   513.5 2439.77   528.4 2442.77   630.4 2445.38   711.6 2449.22
   746.3 2448.84     786 2450.61   802.1 2455.42   817.5  2464.5   864.4 2477.71
#Mann= 5 ,-1,0
       0      .1       0   275.4    .045       0   321.2      .1       0
   727.5     .06       0   827.5      .1       0
Bank Sta=275.4,321.2
XS Rating Curve= 0 ,0
Exp/Cntr=0.3,0.1

Type RM Length L Ch R = 1 ,46392   ,261.8,276,284.6
XS GIS Cut Line= 3
2360308.72897175706274.1466276032360817.92077636706025.146239634
 2361184.4269654705974.786610606
#Sta/Elev= 30
       0 2470.13    21.6 2466.29   150.8 2455.97   181.9 2454.79   226.5  2455.9
   230.6 2454.32   245.5 2440.87   251.5 2437.94   275.4 2439.94   284.4 2438.47
   342.2 2438.68   364.5 2440.87     404 2441.38   440.2 2437.12   457.8 2439.11
   480.3 2439.61   515.9 2436.92   541.6 2438.42   560.4  2441.3   585.2 2439.55
   617.5 2441.24   698.3 2439.23   738.7 2441.79   746.7 2440.65   771.1 2441.34
   803.3 2440.04   815.4 2446.23   827.9  2456.8   908.2 2518.12   936.8 2536.91
#Mann= 5 ,-1,0
       0      .1       0   284.4    .045       0   342.2      .1       0
  726.81     .06       0  826.81      .1       0
Bank Sta=284.4,342.2
XS Rating Curve= 0 ,0
Exp/Cntr(USF)=0,0
Exp/Cntr=0.3,0.1

Type RM Length L Ch R = 1 ,46116   ,238.2,224.9,220.2
XS GIS Cut Line= 3
 2360317.6678082706415.3692147322360580.50670049 706383.88103961
2361305.50283786706320.730158192
#Sta/Elev= 30
       0 2477.43     208 2453.51   224.1 2449.33   240.2  2437.4   248.3  2435.7
   318.6 2435.81   318.6 2435.82   328.6 2437.62   380.8 2435.44   412.9 2437.45
   441.1  2434.3   469.2  2438.2   501.3 2434.96   533.4 2436.94   549.5 2433.39
   573.6 2435.41   649.8  2435.3     699 2438.35   730.1 2435.75   746.2 2440.96
   758.2 2441.68   762.3    2443   774.3 2455.01   790.4 2465.76   802.5  2470.9
   822.5 2484.39   830.5 2487.04   882.7 2522.25   922.9 2546.94   992.5 2570.86
#Mann= 5 ,-1,0
       0      .1       0   248.3    .045       0   318.6      .1       0
  764.72     .06       0  864.72      .1       0
Bank Sta=248.3,318.6
XS Rating Curve= 0 ,0
Exp/Cntr=0.3,0.1

Type RM Length L Ch R = 1 ,45891   ,252.6,250.9,257
XS GIS Cut Line= 4
2360324.92666082706608.6160584922360627.04058232706614.541988842
2360756.79152974706567.3432066872361199.40508589706584.760464345
#Sta/Elev= 30
       0 2504.68    59.3 2484.29    75.3  2480.7    87.3 2475.73    99.3  2474.4
   111.3 2470.49   159.3 2461.25   255.3 2447.53   291.3 2436.51   303.4 2435.17
   322.8 2435.85   338.5 2433.66   401.3 2433.27     414  2435.6   447.6 2433.93
   471.6 2435.66   515.7 2435.22   547.7 2431.42   571.7 2435.24   635.8 2432.03
   659.8 2434.31   723.8 2431.99   755.9 2437.04   767.9 2442.87   783.9 2443.92
   788.1 2447.74   799.9 2464.84   823.9 2484.27   855.9 2504.93   883.2 2517.59
#Mann= 5 ,-1,0
       0      .1       0   338.5    .045       0   401.3      .1       0
  660.24     .06       0  860.24      .1       0
Bank Sta=338.5,401.3
XS Rating Curve= 0 ,0
Exp/Cntr(USF)=0,0
Exp/Cntr=0.3,0.1

Type RM Length L Ch R = 1 ,45640   ,155.8,155.1,152.9
XS GIS Cut Line= 4
     2360347.754      706930.7122360643.96607457706857.922775822
2360912.38276303706791.0590473942361197.23480924706766.424000591
#Sta/Elev= 30
       0 2512.37    44.6 2488.81    58.1 2479.85    67.7 2471.59    78.7 2468.62
   111.6 2445.22     124 2438.55   132.2 2435.89   165.2 2433.44     194 2434.87
   210.5 2431.74   222.9 2431.13   239.3 2433.52   309.8 2434.66   338.2 2431.03
   408.3 2432.94   444.4 2430.99     499 2430.42   519.6 2433.94   540.2 2435.46
   589.5 2432.08   605.7 2433.37   621.6 2429.61   697.9 2432.94   717.9 2447.64
     734 2449.16   758.1 2469.35   777.1 2479.17   830.4 2497.92   867.6 2505.19
#Mann= 5 ,-1,0
       0      .1       0   444.4    .045       0     499      .1       0
  651.64     .06       0  741.64      .1       0
#XS Ineff= 2 , 0
          189.37  2444.5
Permanent Ineff=
       F       F
Bank Sta=444.4,499
XS Rating Curve= 0 ,0
Exp/Cntr=0.3,0.1

Type RM Length L Ch R = 1 ,45485   ,247.3,244.1,239.9
XS GIS Cut Line= 2
2360436.87962025707094.1514949562361103.28440769706885.479288787
#Sta/Elev= 30
       0 2487.36      13 2477.53    32.1 2460.07    45.4 2455.45    62.1 2442.07
      80  2431.5    92.8 2430.08   112.4 2432.31   246.6 2432.85   259.1 2432.45
   275.9  2428.3   368.1 2431.42   397.5 2429.19   447.1 2429.47   464.5 2433.03
   485.4 2433.81   498.1 2433.21   510.6 2429.92   523.2 2431.86   544.2 2429.52
   560.9 2431.19   577.7 2428.77   602.8  2429.9   615.4 2434.44   632.2 2447.83
   648.9 2450.99   653.1 2453.54   661.5 2462.95   665.7 2465.83   698.3  2472.2
#Mann= 5 ,-1,0
       0      .1       0   397.5    .045       0   447.1      .1       0
     570     .06       0     670      .1       0
Bank Sta=397.5,447.1
XS Rating Curve= 0 ,0
Exp/Cntr(USF)=0,0
Exp/Cntr=0.3,0.1

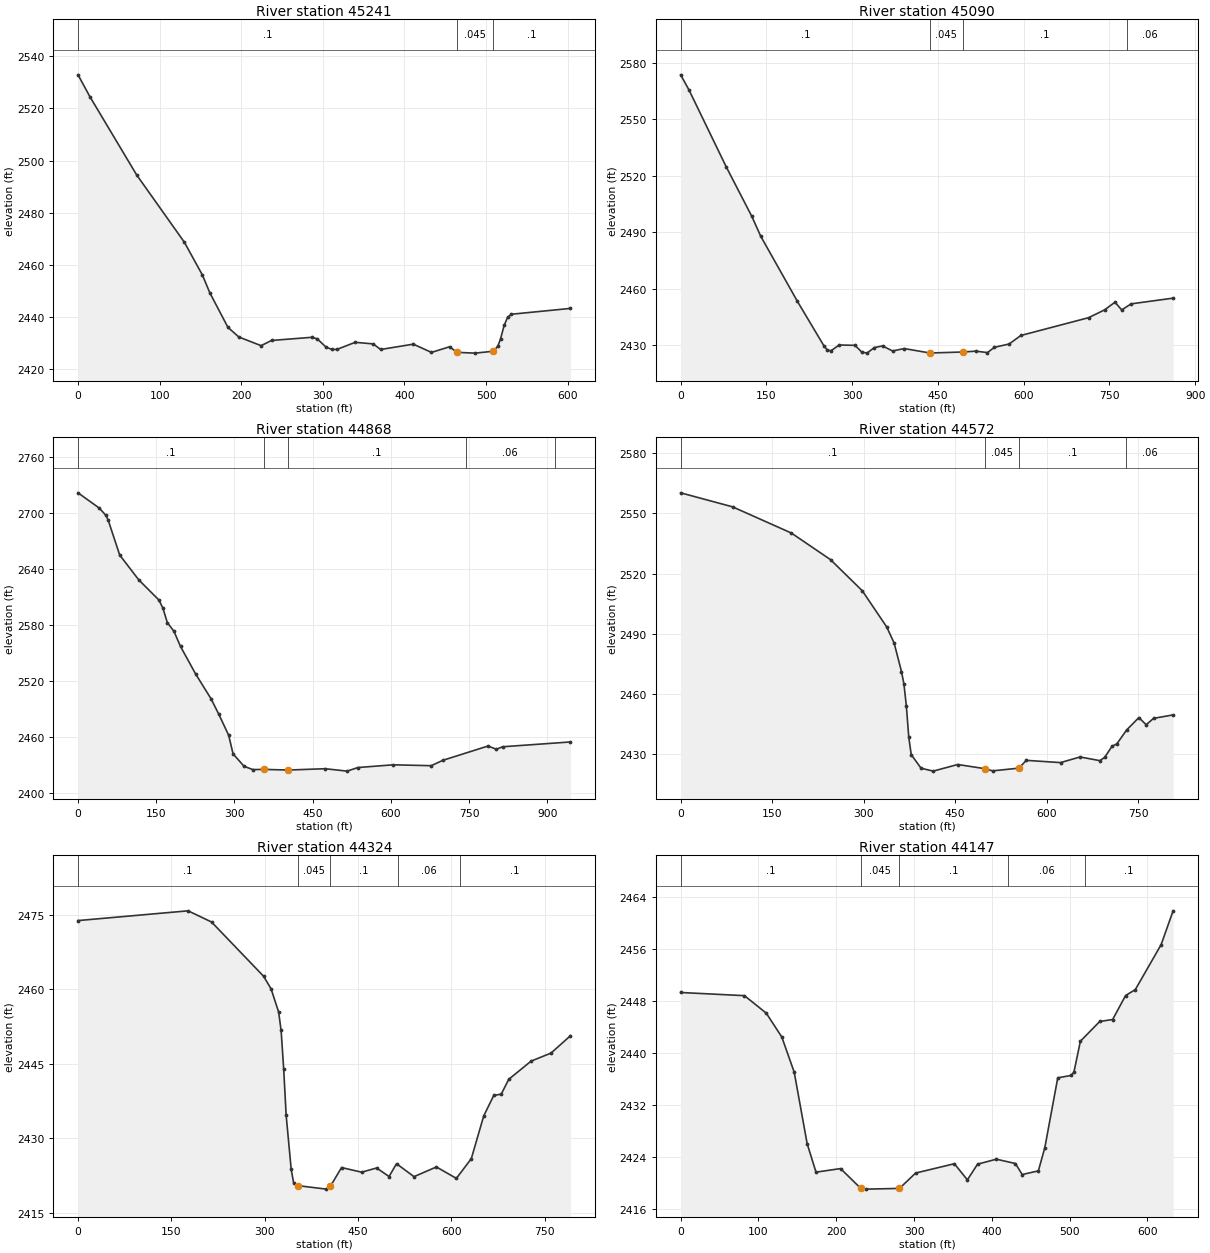
Type RM Length L Ch R = 1 ,45241   ,149.3,150.7,142.4
XS GIS Cut Line= 2
2360487.13113639707408.1797978792361029.23578316707143.107942157
#Sta/Elev= 30
       0 2532.81    14.5 2524.46    71.8  2494.5   130.3 2468.71   152.5  2456.1
   161.5 2449.34   183.7 2436.12   197.1 2432.42   224.3 2429.12   237.1 2431.11
   286.1 2432.31   293.1 2431.75   303.9 2428.54     311 2427.69     317 2427.65
   339.6  2430.4   361.7 2429.79   370.8 2427.66   410.8 2429.69   433.1 2426.54
   455.3  2428.7   464.2 2426.56   486.5 2426.26   508.8 2426.98   514.4 2428.91
   517.7  2431.7   522.1 2436.87   526.3 2439.93     531 2441.15   603.4 2443.38
#Mann= 3 ,-1,0
       0      .1       0   464.2    .045       0   508.8      .1       0
Bank Sta=464.2,508.8
XS Rating Curve= 0 ,0
Exp/Cntr(USF)=0,0
Exp/Cntr=0.3,0.1

Type RM Length L Ch R = 1 ,45090   ,235,222.4,202.2
XS GIS Cut Line= 3
2360559.70076244707572.6397162282361016.31909597707302.167476303
 2361195.9800942707024.530143955
#Sta/Elev= 30
       0 2573.72    14.5 2565.73    79.6 2524.88   124.5 2498.48     140 2487.97
   204.3 2453.29     251 2429.49   256.2 2427.65   262.7    2427   277.3 2430.14
     305 2429.95   316.7  2426.4     326 2425.81   338.6 2428.74   353.2 2429.64
   370.7 2426.95   391.1 2428.24   436.2 2425.87   493.4 2426.41   516.6 2426.86
   536.7  2426.1   548.7  2428.9   574.6 2430.66     595 2435.18   713.6 2444.65
   741.5 2448.79   759.8 2452.88   771.4 2448.78   788.1    2452   861.4 2455.03
#Mann= 4 ,-1,0
       0      .1       0   436.2    .045       0   493.4      .1       0
  780.71     .06       0
Bank Sta=436.2,493.4
XS Rating Curve= 0 ,0
Exp/Cntr=0.3,0.1

Type RM Length L Ch R = 1 ,44868   ,294.4,296.1,279.6
XS GIS Cut Line= 3
2360927.52073711707888.106775204 2361095.3861672707370.521699088
2361285.63365464707018.004295895
#Sta/Elev= 30
       0 2721.96    40.9 2705.52    53.5 2697.72    57.7 2692.87    79.9 2655.23
   116.6 2628.48   155.3 2606.83   162.9 2598.05   171.3 2582.66   183.9 2573.44
   196.6 2557.06   225.9 2527.26   255.4 2500.71   269.6  2484.8     289 2461.76
   297.4 2441.85   318.5 2428.48   335.3 2424.93   356.3 2425.16   402.9 2424.45
   474.1 2425.88   516.1 2423.29   537.1 2427.16   604.7 2430.06   677.5 2429.12
   700.2 2434.96   786.6 2450.25   802.5 2446.71   814.3 2449.42   944.7 2454.61
#Mann= 5 ,-1,0
       0      .1       0   356.3    .045       0   402.9      .1       0
  744.13     .06       0  914.13      .1       0
Bank Sta=356.3,402.9
XS Rating Curve= 0 ,0
Exp/Cntr(USF)=0,0
Exp/Cntr=0.3,0.1

Type RM Length L Ch R = 1 ,44572   ,244.3,247.2,241.7
XS GIS Cut Line= 2
     2361323.276      707922.0572361262.95353985707117.173561535
#Sta/Elev= 30
       0 2560.24    85.1 2553.26   181.4 2540.22   245.6 2526.97   297.7 2511.46
   337.8  2493.4   349.9 2485.42   361.9 2471.25   365.9 2465.08   369.9 2454.14
   373.9 2438.46   377.9 2429.84     394 2423.08   413.9 2421.63   454.1 2424.93
   498.3 2422.87   511.2 2421.76   554.4 2423.12   566.5    2427   622.6 2425.88
   654.7 2428.69     687 2426.85   694.8 2428.43   706.9 2433.96   714.9 2435.21
   730.9  2442.1     751  2448.3     763 2444.72     775  2447.9   807.1 2449.64
#Mann= 4 ,-1,0
       0      .1       0   498.3    .045       0   554.4      .1       0
     730     .06       0
Bank Sta=498.3,554.4
XS Rating Curve= 0 ,0
Exp/Cntr=0.3,0.1

Type RM Length L Ch R = 1 ,44324   ,181.6,177.1,174.6
XS GIS Cut Line= 3
2361576.60040013707804.174060158 2361509.4542281707345.341884574
2361492.66768509707018.004295895
#Sta/Elev= 30
       0 2473.81   176.9 2475.77   214.6 2473.52   298.1 2462.63   310.3 2460.07
   322.4 2455.42   326.4  2451.7   330.5 2444.04   334.5 2434.66   342.6 2423.77
   346.6 2421.01   353.5 2420.49   399.2 2419.79   405.6 2420.35   423.5 2424.13
   455.8  2423.2   479.9 2424.04   499.9 2422.33   511.9  2424.9     540  2422.3
     576 2424.25   608.1 2421.95   632.1 2425.92   652.1 2434.53   668.2 2438.64
   680.2 2438.89   692.2 2441.87   728.2 2445.54   760.3 2447.16   791.5 2450.65
#Mann= 5 ,-1,0
       0      .1       0   353.5    .045       0   405.6      .1       0
  513.72     .06       0  613.72      .1       0
Bank Sta=353.5,405.6
XS Rating Curve= 0 ,0
Exp/Cntr(USF)=0,0
Exp/Cntr=0.3,0.1

Type RM Length L Ch R = 1 ,44147   ,280.8,304,312
XS GIS Cut Line= 3
2361695.19028791707607.111235196 2361700.2944763707416.963905212
2361581.33466706706990.308571682
#Sta/Elev= 30
       0 2449.34      82 2448.85     110 2446.16     130 2442.48     146 2437.04
   162.6 2426.03     174 2421.62   205.6 2422.17   231.5 2419.12   238.8    2419
   281.3 2419.11   302.1 2421.48   351.9 2422.92   368.6 2420.43   381.7 2422.85
   405.9 2423.62   430.4 2422.95   439.1 2421.25   459.9 2421.82   468.2 2425.41
   484.8 2436.17   501.9 2436.54   505.6 2437.05   513.9 2441.82   538.8 2444.87
   555.4 2445.17     572 2448.87   584.5 2449.78   617.7 2456.72   633.1 2461.94
#Mann= 5 ,-1,0
       0      .1       0   231.5    .045       0   281.3      .1       0
  420.22     .06       0  520.22      .1       0
Bank Sta=231.5,281.3
XS Rating Curve= 0 ,0
Exp/Cntr=0.3,0.1

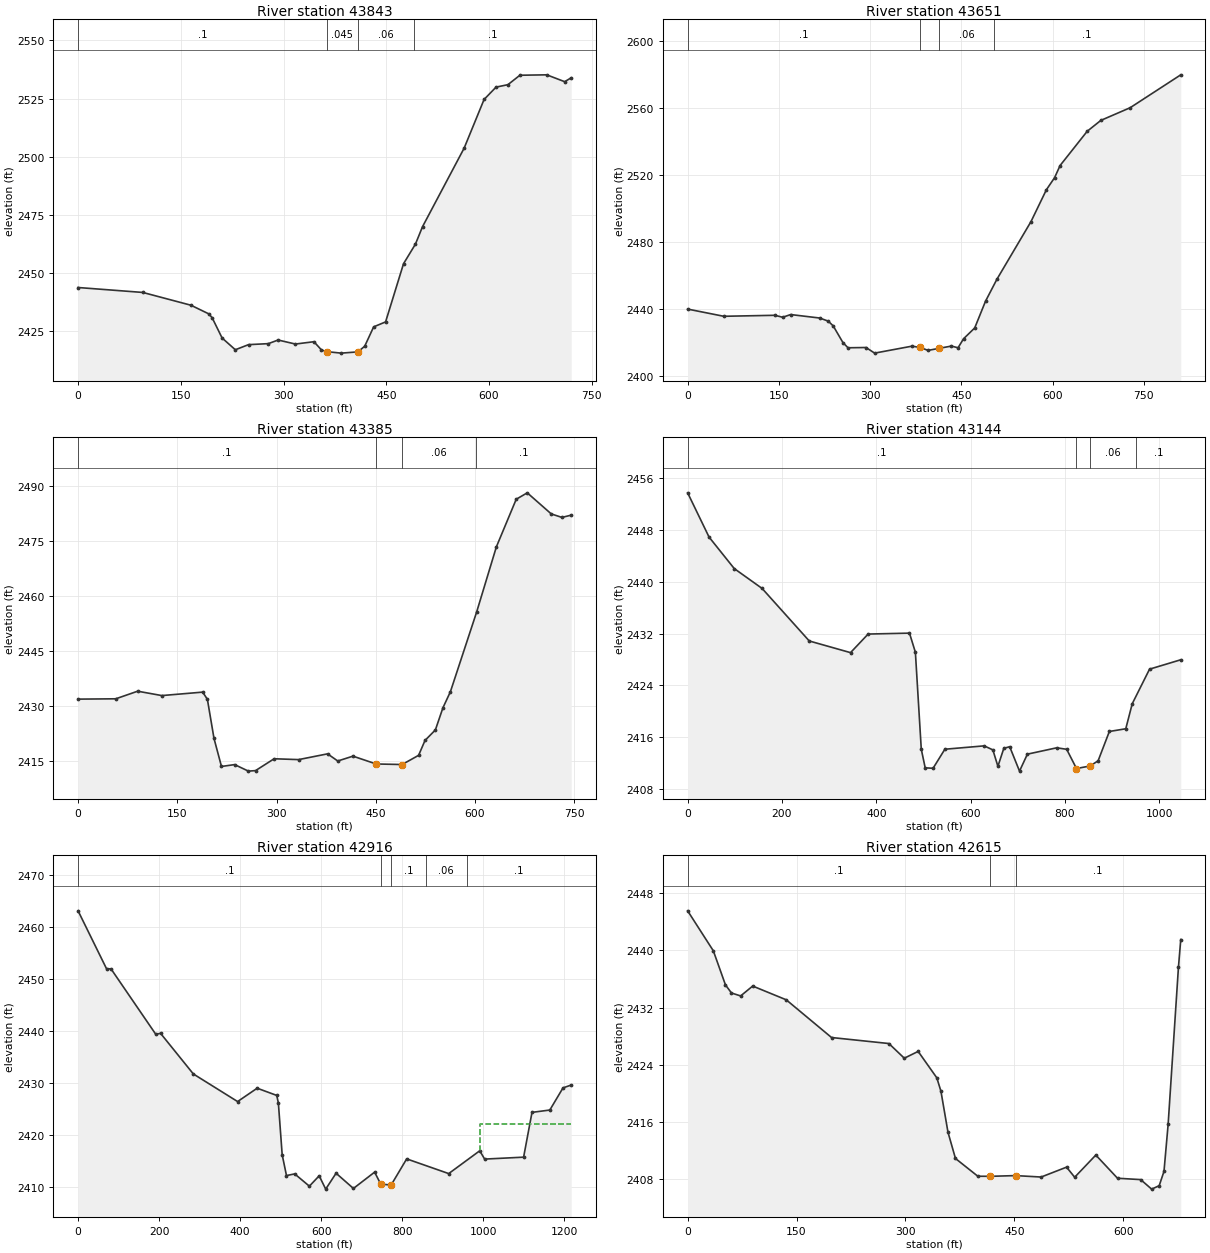
Type RM Length L Ch R = 1 ,43843   ,188.1,192,192.9
XS GIS Cut Line= 3
 2361764.0501304707619.5220870572361926.32004616707378.914970592
2362096.98323342706984.431209876
#Sta/Elev= 30
       0 2443.72    94.5  2441.6   164.8  2436.1     191 2432.36   195.8  2430.7
   210.3    2422   229.6 2416.94   248.9 2419.14   277.8 2419.57   292.1 2421.13
   317.3  2419.4   344.4  2420.4   355.3 2416.88   362.9 2416.13   384.2 2415.49
   408.5 2416.02   418.5 2418.45   431.6  2426.8     449 2428.92   475.2 2453.96
   492.6  2462.4   502.9 2469.87   563.7 2503.69   592.8 2524.63   610.3 2529.94
   627.6 2530.99   645.1 2535.05   684.3 2535.23   710.5 2532.28     720 2533.95
#Mann= 4 ,-1,0
       0      .1       0   362.9    .045       0   408.5     .06       0
  490.21      .1       0
Bank Sta=362.9,408.5
XS Rating Curve= 0 ,0
Exp/Cntr(USF)=0,0
Exp/Cntr=0.3,0.1

Type RM Length L Ch R = 1 ,43651   ,266.1,266.6,280.4
XS GIS Cut Line= 5
2361854.10561808707649.1746472792362014.33239249707575.994251505
2362093.05147571707451.9717150462362211.31299319707234.050207087
      2362317.92      707019.444
#Sta/Elev= 30
       0 2440.02    59.4 2435.73   143.4 2436.32   156.2 2435.15   169.4 2436.76
   217.2 2434.69   231.2 2432.82   239.3 2429.99   255.3 2420.05   263.6 2416.96
   293.2 2417.12   307.4 2413.77   368.7 2417.92   381.9 2417.17   395.3  2415.4
   413.5 2416.64   433.6 2417.97   444.5 2416.97   453.6 2422.35   471.9 2428.78
   489.7 2444.75   508.3 2457.75   564.4 2492.17   589.8 2511.21   603.2 2518.35
   612.2 2525.58   656.8 2546.01   679.2 2552.49   727.4 2560.05   810.6 2579.66
#Mann= 4 ,-1,0
       0      .1       0   381.9    .045       0   413.5     .06       0
  503.04      .1       0
Bank Sta=381.9,413.5
XS Rating Curve= 0 ,0
Exp/Cntr=0.3,0.1

Type RM Length L Ch R = 1 ,43385   ,240.4,241,251.9
XS GIS Cut Line= 4
2361984.95954207707712.203590106   2362163.76367707666.006606334
2362292.82623519707560.7691865252362586.59073785707297.780012714
#Sta/Elev= 30
       0 2431.94      57 2432.03    90.1  2434.1   126.6 2432.91   188.4 2433.85
   195.5 2431.89   205.5 2421.23   216.8 2413.59   236.7  2414.1   257.5 2412.32
   268.3 2412.46   296.4 2415.69   333.4 2415.46   377.2 2417.03   392.6 2415.08
   415.6  2416.4   450.6 2414.27   489.9 2414.12   514.8 2416.62   524.5 2420.68
   540.2 2423.55   551.6 2429.58   562.9 2433.96   602.5 2455.64   632.4 2473.44
   662.4 2486.41   679.1 2488.16   715.4 2482.41   731.5 2481.46   745.5 2482.08
#Mann= 4 ,-1,0
       0      .1       0   450.6    .045       0   489.9     .06       0
  601.21      .1       0
Bank Sta=450.6,489.9
XS Rating Curve= 0 ,0
Exp/Cntr(USF)=0,0
Exp/Cntr=0.3,0.1

Type RM Length L Ch R = 1 ,43144   ,229.5,227.5,243.6
XS GIS Cut Line= 3
2361744.61628673707888.1537606662362590.56452043707641.279306012
2362733.93066529707560.795238152
#Sta/Elev= 30
       0 2453.72    45.4 2446.89    98.8 2442.03   157.9 2438.96   257.9 2430.85
   345.4 2429.05   382.7 2431.92   470.4 2432.06   482.9 2429.11   495.4 2414.14
   503.7 2411.27   520.4  2411.2   545.4 2414.14   628.7 2414.66   647.2 2414.04
   657.9  2411.5   670.4 2414.28   682.9 2414.53   703.7 2410.76   720.4 2413.38
   782.6 2414.36   803.7 2414.13   824.5 2411.16   853.6 2411.56   870.4 2412.36
   894.2 2416.88     929  2417.3   942.7 2421.16   979.4  2426.5  1045.6 2427.95
#Mann= 4 ,-1,0
       0      .1       0   824.5    .045       0   853.6     .06       0
  951.24      .1       0
Bank Sta=824.5,853.6
XS Rating Curve= 0 ,0
Exp/Cntr=0.3,0.1

Type RM Length L Ch R = 1 ,42916   ,290.8,301,306.3
XS GIS Cut Line= 5
2361702.71078972707947.8757106112362106.83126957707889.157350291
2362414.23915595707854.6171383382362562.76206735  707882.2493079
2362908.16418688707923.697562244
#Sta/Elev= 30
       0 2463.06    70.2 2451.92    81.3 2451.89   191.5 2439.33   203.6 2439.48
   284.4 2431.67   393.6 2426.36   441.9 2428.93   490.2 2427.54   494.2  2426.1
   503.6 2416.13   514.2 2412.12   534.5 2412.44   570.7 2410.08   594.9 2412.07
     611 2409.51   636.6 2412.57   679.4 2409.64   731.7 2412.78   746.9 2410.45
   772.6 2410.32   810.8 2415.33   914.5  2412.5   991.1 2416.89  1003.1 2415.29
  1099.3 2415.66    1120 2424.28    1164 2424.73  1196.5 2428.99  1216.7 2429.54
#Mann= 5 ,-1,0
       0      .1       0   746.9    .045       0   772.6      .1       0
  857.71     .06       0  958.78      .1       0
#XS Ineff= 2 , 0
                          990.84         2421.98
Permanent Ineff=
       F       F
Bank Sta=746.9,772.6
XS Rating Curve= 0 ,0
Exp/Cntr(USF)=0,0
Exp/Cntr=0.3,0.1

Type RM Length L Ch R = 1 ,42615   ,149.9,148.9,142.9
XS GIS Cut Line= 3
 2361834.2636646708004.1629673332362131.59867643707915.504064635
2362362.76926349708203.030676023
#Sta/Elev= 30
       0 2445.52    35.4 2439.93    52.1 2435.17    60.4 2434.04      73 2433.63
    89.6 2435.01   135.8 2433.09   198.2 2427.82   277.2 2426.98   298.4 2424.93
   317.5 2425.88   343.2 2422.19   348.9 2420.31   358.6 2414.58   368.9 2410.92
   399.7 2408.44   417.1 2408.43   451.6 2408.53   486.9 2408.33   521.9 2409.71
   533.1  2408.3   562.2  2411.4   592.1 2408.16     624 2407.97   639.1 2406.64
   649.5 2407.12   656.1 2409.12   661.8 2415.67     676 2437.62   679.2 2441.51
#Mann= 3 ,-1,0
       0      .1       0   417.1    .045       0   451.6      .1       0
Bank Sta=417.1,451.6
XS Rating Curve= 0 ,0
Exp/Cntr=0.3,0.1

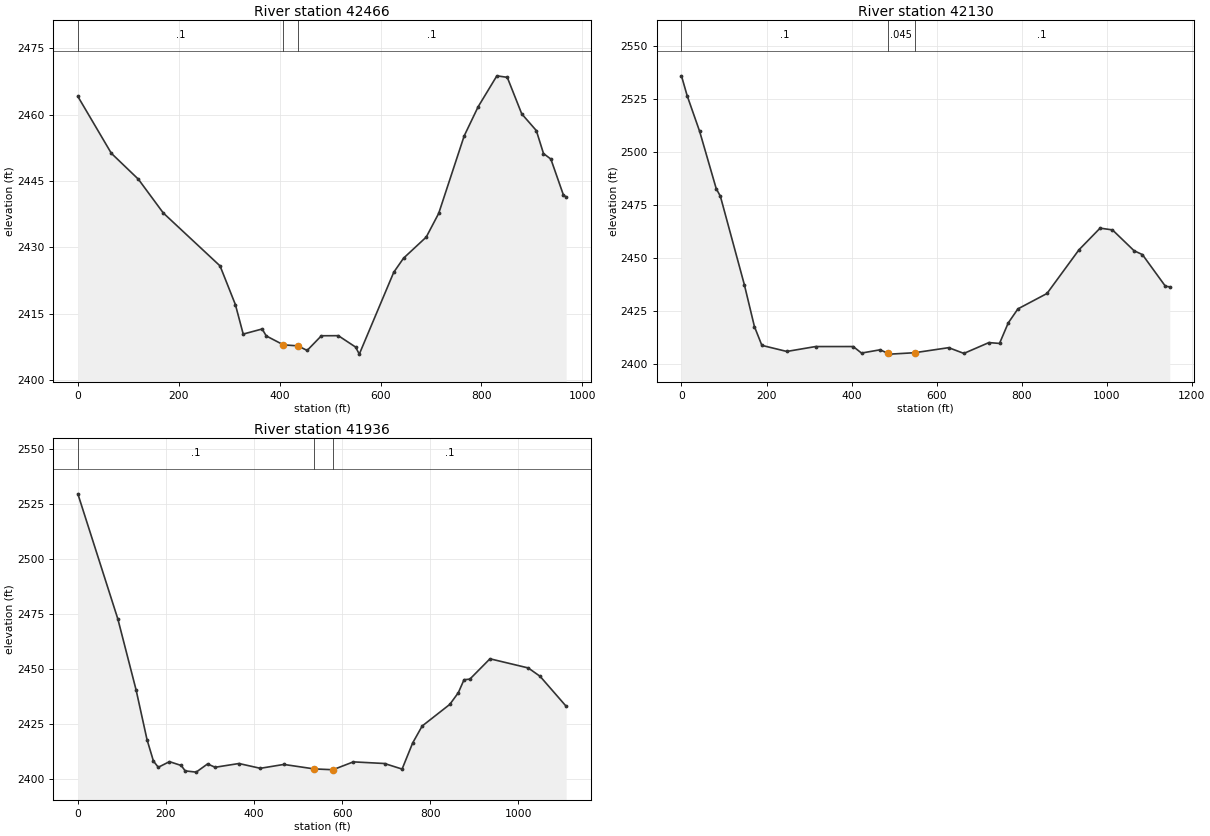
Type RM Length L Ch R = 1 ,42466   ,371.3,336.3,309.2
XS GIS Cut Line= 5
2361711.76638265708078.5741116452361977.45647764708012.314877157
2362252.67671425708220.1843950842362310.93162216708221.075735104
2362593.56844267708152.352481514
#Sta/Elev= 30
       0 2464.09    66.4 2451.24     120 2445.38   169.4 2437.75   281.9 2425.79
   312.3 2417.05   327.8 2410.39   365.3 2411.54   373.5 2409.97   407.6 2407.95
   436.3 2407.73   454.5 2406.69   482.8 2410.01   516.3 2410.03   550.5 2407.46
   557.9 2405.86   626.2 2424.36   645.6 2427.54   690.6 2432.31   715.3 2437.67
   765.8 2455.17   793.5 2461.76   830.6 2468.74   851.2  2468.4   879.9 2460.14
   908.8 2456.37     923 2451.18   937.6 2449.93   962.3 2441.87   967.9 2441.34
#Mann= 3 ,-1,0
       0      .1       0   407.6    .045       0   436.3      .1       0
Bank Sta=407.6,436.3
XS Rating Curve= 0 ,0
Exp/Cntr(USF)=0,0
Exp/Cntr=0.3,0.1

Type RM Length L Ch R = 1 ,42130   ,200.3,194.2,192.3
XS GIS Cut Line= 3
2361613.21331539 708697.879526622362169.12563194708309.021631366
2362622.07465712708183.764447627
#Sta/Elev= 30
       0 2535.75    13.4 2526.37    42.7 2509.58    81.7 2482.56    91.5 2478.95
   147.8  2437.3   171.6 2417.47   189.1  2408.6   247.7 2405.73   315.3 2408.04
   403.9 2408.05   423.4 2404.97   467.4 2406.52   485.2 2404.82   490.9 2404.47
   548.4 2405.13   628.4 2407.52   664.2 2404.81     723 2409.91     748 2409.52
   768.5 2419.19   791.3 2425.82   859.6 2433.07   934.7 2453.65   984.5  2463.9
  1013.6 2463.07  1064.4 2453.25  1084.1 2451.41  1138.1 2436.49  1148.4  2436.2
#Mann= 3 ,-1,0
       0      .1       0   485.2    .045       0   548.4      .1       0
Bank Sta=485.2,548.4
XS Rating Curve= 0 ,0
Exp/Cntr=0.3,0.1

Type RM Length L Ch R = 1 ,41936   ,570.5,558.7,533.2
XS GIS Cut Line= 3
2361744.72280638708867.3258775122362479.11688769708289.286665129
2362635.47175661708213.478243833
#Sta/Elev= 30
       0 2529.62    90.9 2472.61   132.2 2440.41   157.1  2417.7   171.6    2408
   182.6 2405.17     208 2407.73   234.7 2405.98   243.6 2403.53   268.6 2402.96
   294.5 2406.69   311.6 2405.17   365.7 2406.88   414.2  2404.7   467.6 2406.46
   536.6 2404.42   579.1 2404.05   625.4 2407.63   696.2 2406.88     736 2404.35
   760.1 2416.27   781.6 2423.95   844.3 2433.79   863.6 2439.09   876.6 2445.01
   889.8 2445.28   935.5 2454.54  1022.3 2450.38  1049.2 2446.57  1108.4 2432.94
#Mann= 3 ,-1,0
       0      .1       0   536.6    .045       0   579.1      .1       0
Bank Sta=536.6,579.1
XS Rating Curve= 0 ,0
Exp/Cntr(USF)=0,0
Exp/Cntr=0.3,0.1