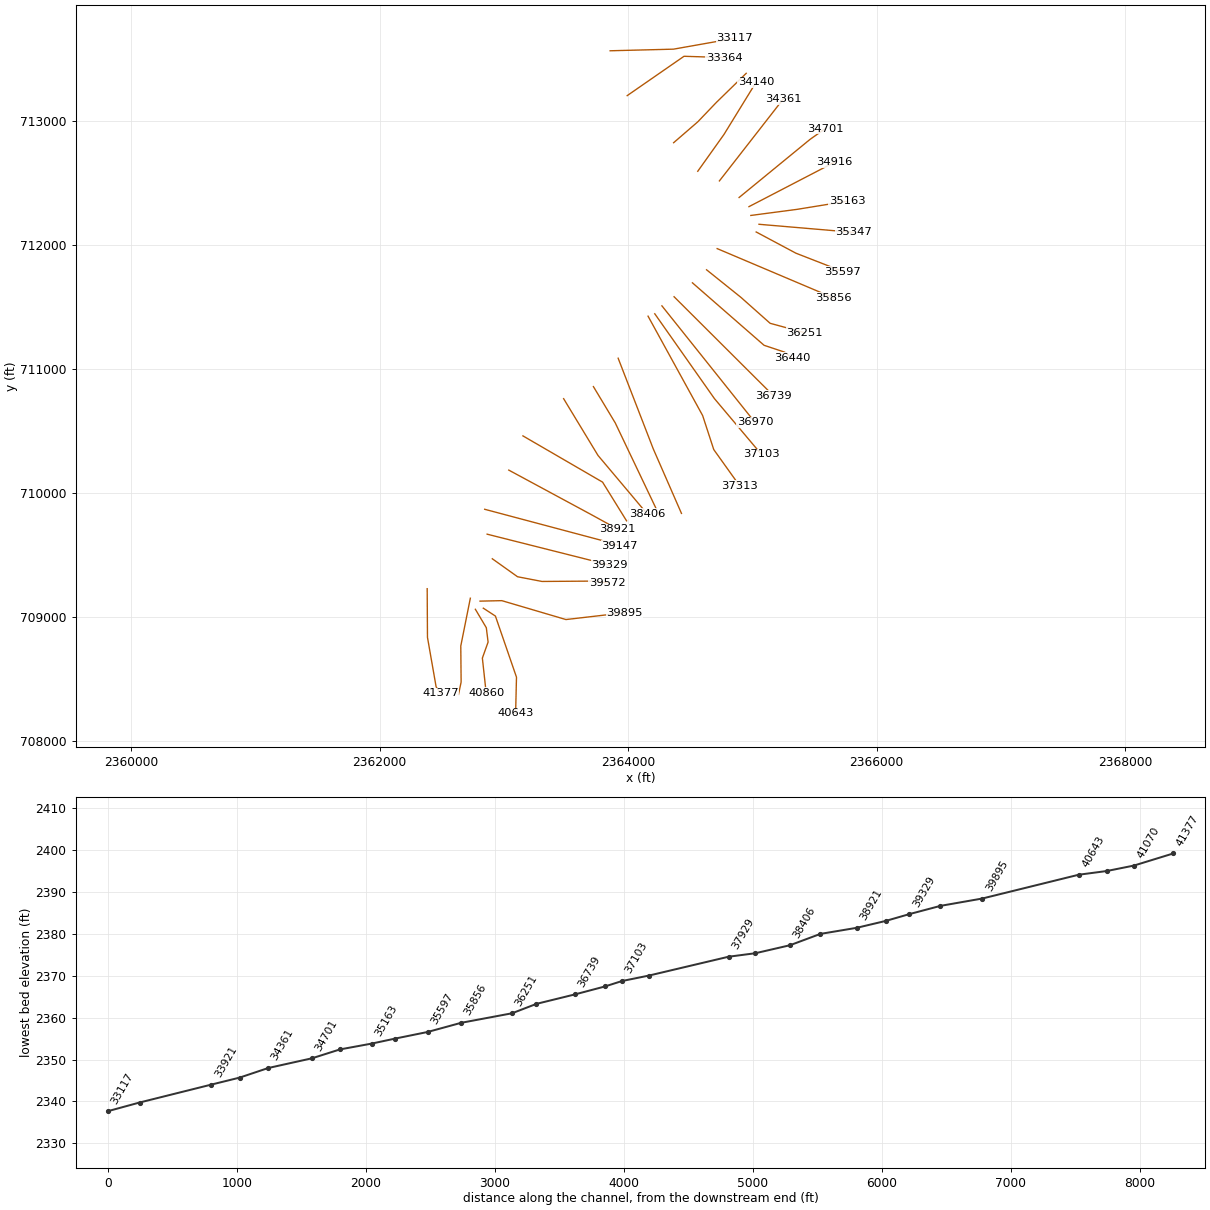
HEC-RAS study GLADYFK.prj: GLADYFK

--- GLADYFK.g01 (geometry) --- (continued)

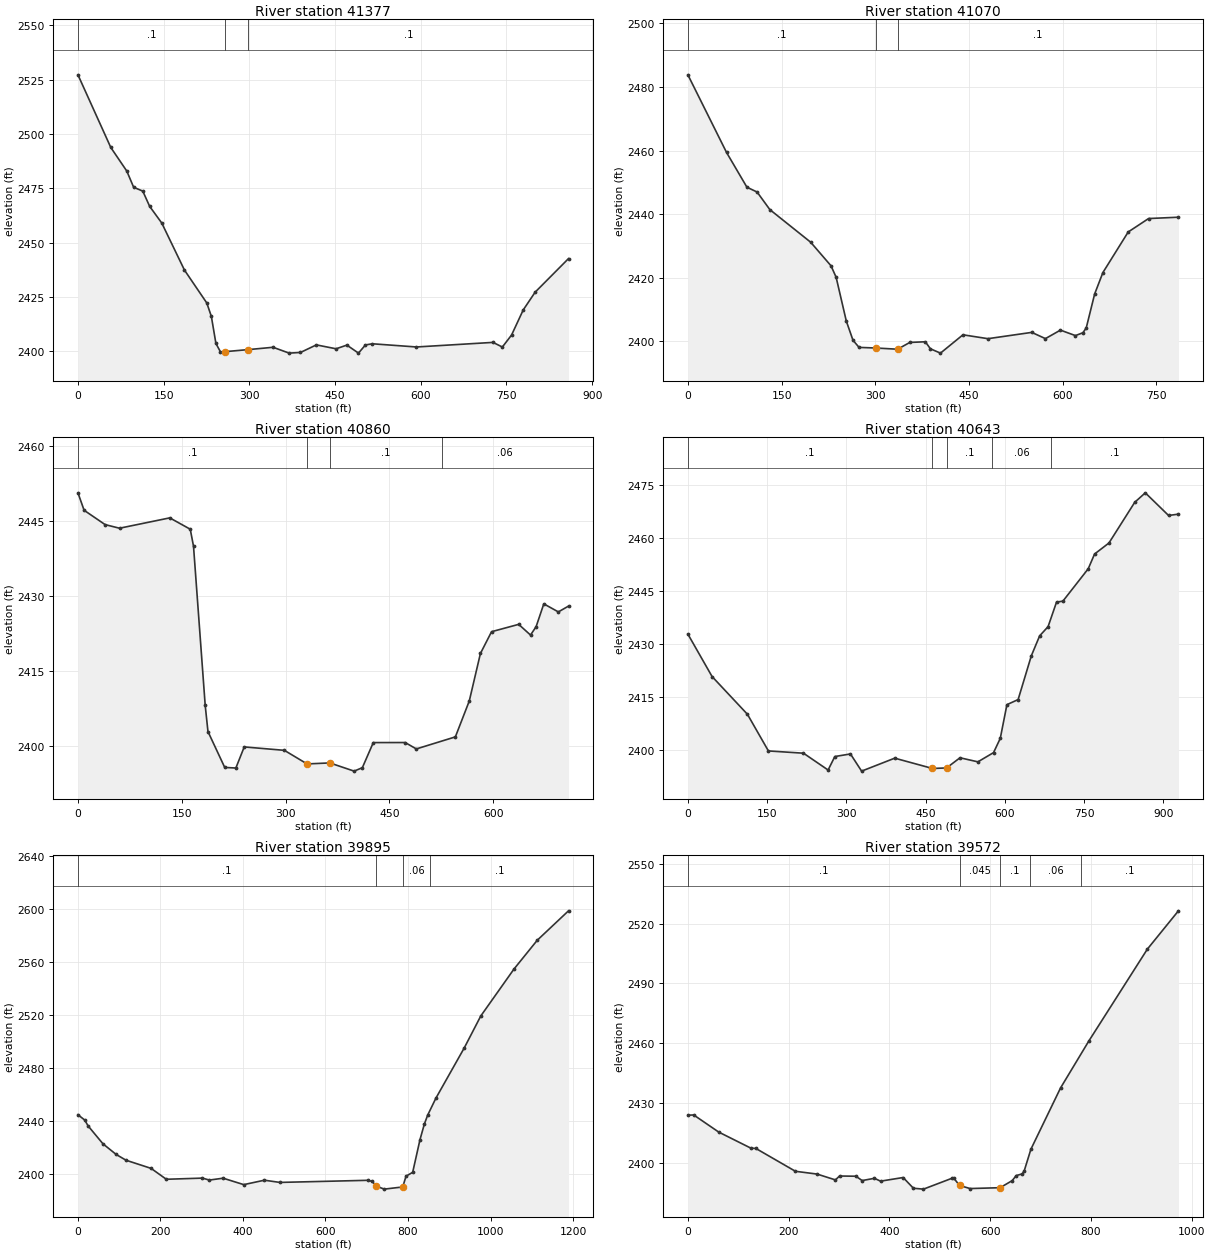
Type RM Length L Ch R = 1 ,41377   ,310.7,307,301.4
XS GIS Cut Line= 4
2362382.21338303 709230.714286972362384.47956634708838.664574991
2362454.22948409708439.7608603472362490.17453167708389.783197634
#Sta/Elev= 30
       0  2527.3    57.5 2493.87    85.5 2483.02    97.5 2475.56   113.5  2473.8
   125.5 2466.78   146.7 2459.11   186.4 2437.47   225.5 2422.33   233.5 2416.15
   241.5 2403.68   249.5 2399.81   257.5 2399.93   297.8 2400.86   341.5 2401.94
   369.7 2399.25   389.5 2399.56   417.3 2403.04   451.8 2401.25   470.7 2402.94
     491 2399.26   503.2 2403.02   515.4 2403.55   592.5 2402.08   726.5 2404.19
   742.8 2402.05     759  2407.6   779.3  2419.1   800.2  2427.3   858.6 2442.75
#Mann= 3 ,-1,0
       0      .1       0   257.5    .045       0   297.8      .1       0
Bank Sta=257.5,297.8
XS Rating Curve= 0 ,0
Exp/Cntr(USF)=0,0
Exp/Cntr=0.3,0.1

Type RM Length L Ch R = 1 ,41070   ,211.7,210,206.4
XS GIS Cut Line= 4
2362729.45183306709153.8599645292362652.58570322708769.236853237
2362655.31762451708478.7253557992362634.33984107 708378.47727202
#Sta/Elev= 30
       0 2483.81    61.9 2459.41    94.5 2448.49   110.8 2446.97   131.2 2441.45
   196.5 2431.21   229.1 2423.79   237.3 2420.18   253.6 2406.41   264.3 2400.38
     274 2398.14   300.8 2397.95   335.7 2397.57   355.2  2399.7   380.1 2399.91
   388.2  2397.7   404.3 2396.34   440.3  2402.1   480.3 2400.88   550.4 2402.86
   572.3  2400.9   596.3 2403.57   620.3 2401.85   632.3 2402.75   637.6 2404.25
   651.1 2414.94   664.3 2421.67   704.8 2434.42   737.4 2438.64   785.2 2439.06
#Mann= 3 ,-1,0
       0      .1       0   300.8    .045       0   335.7      .1       0
Bank Sta=300.8,335.7
XS Rating Curve= 0 ,0
Exp/Cntr=0.3,0.1

Type RM Length L Ch R = 1 ,40860   ,203.6,216.6,220.2
XS GIS Cut Line= 5
2362769.99948211 709064.855292472362858.11117345708916.004685715
2362872.35950854708800.7228017192362826.27228713708671.684730122
2362856.96341477708390.635294286
#Sta/Elev= 30
       0 2450.71     8.9 2447.22    39.3 2444.35    60.1 2443.63   132.7  2445.7
   162.3 2443.43     167 2440.04   183.9 2408.18   187.9 2402.95   212.1 2395.78
   228.2 2395.66   240.3 2399.88   298.3  2399.2   331.1 2396.48     364 2396.68
   399.1 2395.04     411 2395.73   426.8 2400.75   472.9 2400.76     489 2399.48
   545.4 2401.89   565.5 2409.07   581.6 2418.57   597.7 2422.93   636.9  2424.4
     654 2422.26   662.1 2423.94   673.2  2428.5   694.2 2426.89   708.9 2428.05
#Mann= 4 ,-1,0
       0      .1       0   331.1    .045       0     364      .1       0
  526.15     .06       0
Bank Sta=331.1,364
XS Rating Curve= 0 ,0
Exp/Cntr(USF)=0,0
Exp/Cntr=0.3,0.1

Type RM Length L Ch R = 1 ,40643   ,696.1,748.3,782
XS GIS Cut Line= 4
2362833.82099452709073.6706962942362931.24919236709010.085073416
2363100.87950189708517.8542645122363093.79409033  708226.4797212
#Sta/Elev= 30
       0 2432.84    45.8 2420.86   112.7 2410.21   152.4 2399.86   218.8 2399.22
   265.4 2394.47   278.1 2398.28   307.7 2399.01   328.8 2394.16   391.5 2397.82
   462.9 2394.91   489.6 2395.06     515 2397.93   548.9 2396.78   578.5 2399.39
   591.2  2403.4   603.8 2412.92     625 2414.36     650 2426.72   665.7 2432.34
   681.7 2434.95   697.7 2441.88   709.7 2442.14   757.7 2451.29   769.7 2455.45
   796.9 2458.56   845.7 2470.05   865.7 2472.72   909.7 2466.33   928.4  2466.7
#Mann= 5 ,-1,0
       0      .1       0   462.9    .045       0   489.6      .1       0
  576.34     .06       0  686.98      .1       0
Bank Sta=462.9,489.6
XS Rating Curve= 0 ,0
Exp/Cntr=0.3,0.1

Type RM Length L Ch R = 1 ,39895   ,326.9,323.5,314.8
XS GIS Cut Line= 4
2362807.57266272709130.3601277292362982.74410775709134.278692893
2363498.90925911708982.0792770822363971.41554047709036.883172946
#Sta/Elev= 30
       0  2444.7    16.6 2440.62    24.6 2436.24    60.6 2422.72    92.6 2414.68
   116.6  2410.3   177.3 2404.15   214.2 2395.92   301.8 2396.79   318.5 2395.32
   351.9 2396.73   401.9 2391.87   451.9 2395.21   489.5 2393.54   702.2 2395.13
   713.4 2394.28   722.7 2390.77   742.5 2388.47   787.22390.116   795.2 2398.25
   811.3 2401.16   829.1 2425.95   839.5  2437.5   847.5 2444.28   867.6 2457.21
   936.1 2495.05   976.4 2519.32  1056.9 2554.79  1113.3 2576.55    1189 2598.76
#Mann= 4 ,-1,0
       0      .1       0   722.7    .045       0   787.2     .06       0
  853.35      .1       0
Bank Sta=722.7,787.2
XS Rating Curve= 0 ,0
Exp/Cntr=0.3,0.1

Type RM Length L Ch R = 1 ,39572   ,255.8,242.3,227.4
XS GIS Cut Line= 5
2362906.34556672709471.5106978112363109.35535019709326.805019843
2363306.29495219 709288.854134692363709.17198441709291.651891858
2363829.43715681709278.349527786
#Sta/Elev= 30
       0 2423.86    11.6 2423.97    61.2 2415.38   125.1  2407.3   134.9 2407.16
   213.5 2395.68   256.5 2394.28   292.9 2391.35   301.1 2393.31   333.6  2393.2
   345.9 2391.02   370.3 2392.15   382.5 2390.72   427.3 2392.55   447.7 2387.16
   467.7 2386.72   523.7 2392.12     528 2392.16   539.42388.548   560.2 2387.01
   619.8 2387.44   643.8 2390.99   651.8 2393.53   663.8 2394.38   667.8 2396.02
     681  2406.8   739.8 2437.55   795.8 2461.07   912.1 2507.26   973.8  2526.5
#Mann= 5 ,-1,0
       0      .1       0   539.4    .045       0   619.8      .1       0
  679.87     .06       0  779.87      .1       0
Bank Sta=539.4,619.8
XS Rating Curve= 0 ,0
Exp/Cntr=0.3,0.1

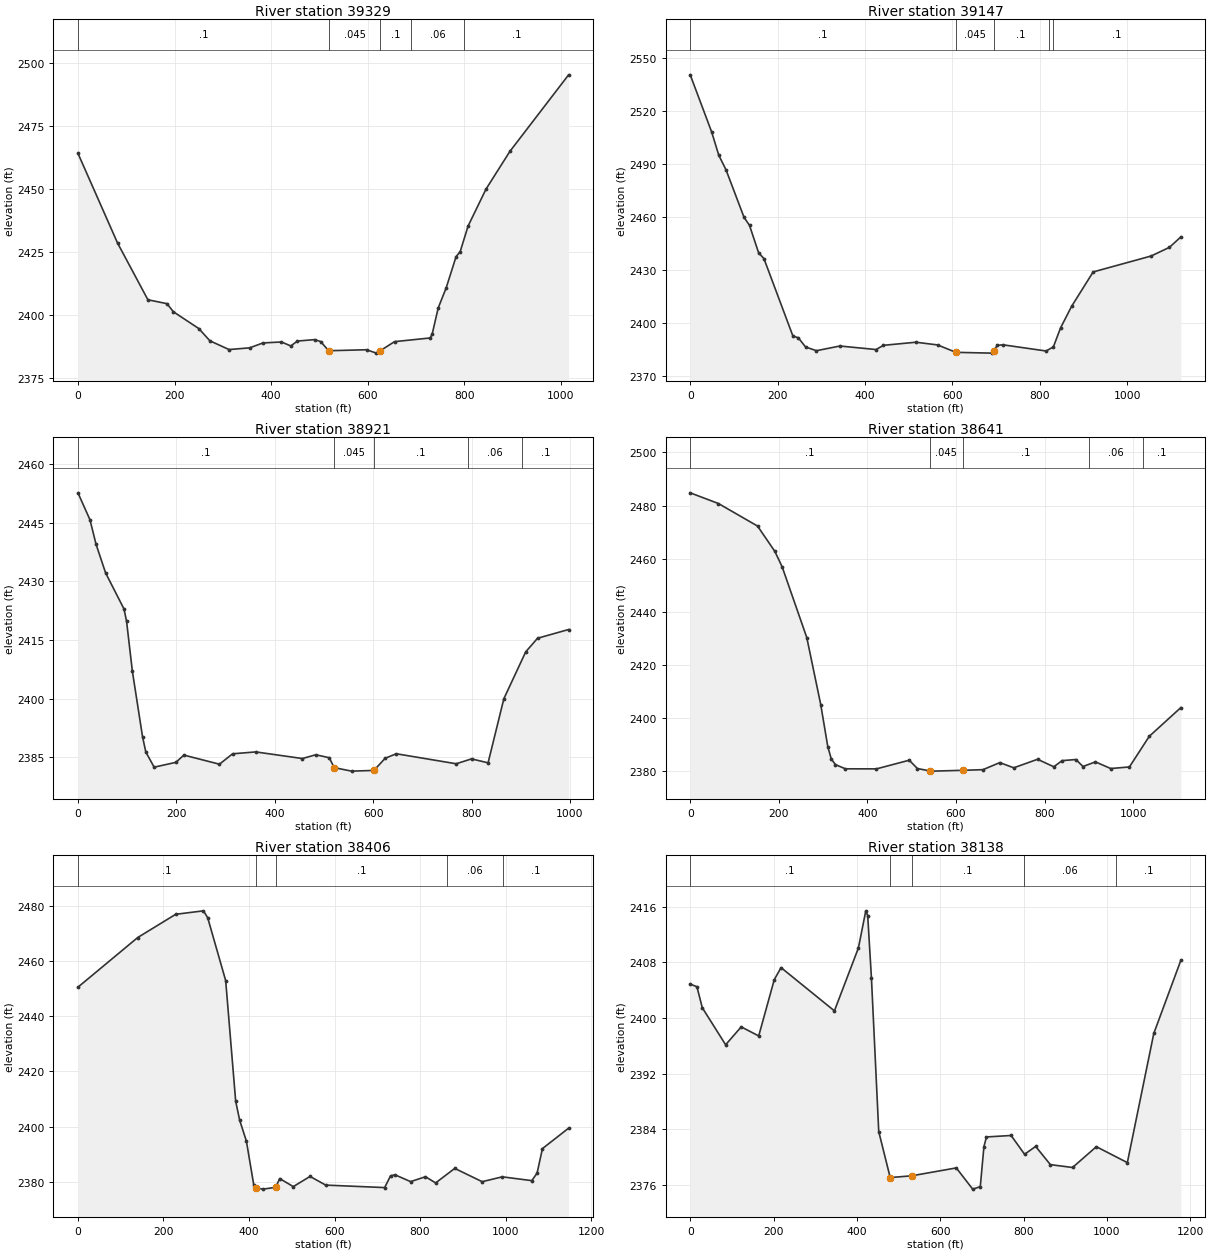
Type RM Length L Ch R = 1 ,39329   ,183.6,182,180.8
XS GIS Cut Line= 2
2362864.66125114 709669.624257292363850.09349816709420.934731228
#Sta/Elev= 30
       0 2464.13      82  2428.5   144.9 2405.94   184.4  2404.4   197.6 2401.18
   250.3 2394.51   273.4 2389.62     313 2386.16   355.7 2386.84   383.2 2388.79
   421.6 2389.17   440.9 2387.59   454.6 2389.54   490.4 2390.11   502.8 2389.33
   519.3 2385.69   597.7 2386.08   618.3 2384.74   626.6 2385.75   655.7  2389.3
   729.7 2390.77   733.8 2392.39   746.2 2402.69   762.7 2410.67   783.3 2423.13
   791.6 2425.01   808.1 2435.25   845.2 2449.92   894.7 2464.92  1016.3 2495.33
#Mann= 5 ,-1,0
       0      .1       0   519.3    .045       0   626.6      .1       0
     690     .06       0     800      .1       0
Bank Sta=519.3,626.6
XS Rating Curve= 0 ,0
Exp/Cntr(USF)=0,0
Exp/Cntr=0.3,0.1

Type RM Length L Ch R = 1 ,39147   ,234.5,225.8,215.5
XS GIS Cut Line= 3
2362845.07554289709870.1044172652363787.38171555709619.195165469
2363929.19001328709577.855596016
#Sta/Elev= 30
       0  2540.3    49.1    2508    65.4 2494.86    81.9 2486.66   123.2 2459.79
   135.7 2455.27   156.4 2439.88   168.8 2436.46     235  2392.8   247.4 2391.77
     264 2386.59   288.8 2384.49   342.6 2387.14   425.4 2385.14     442 2387.52
   516.5 2389.28   566.2 2387.75     608 2383.57   690.3 2383.12   694.5 2384.46
   702.8 2387.47   715.2 2387.84   814.5 2384.32   831.1 2386.66   847.6 2397.39
   872.8 2409.55   922.1 2428.97  1054.8 2437.97  1096.8 2442.88  1122.9 2448.78
#Mann= 5 ,-1,0
       0      .1       0     608    .045       0   694.5      .1       0
     820     .06       0     830      .1       0
Bank Sta=608,694.5
XS Rating Curve= 0 ,0
Exp/Cntr=0.3,0.1

Type RM Length L Ch R = 1 ,38921   ,280.6,280.9,278.4
XS GIS Cut Line= 3
2363038.74391938710185.6550238682363700.87978252709828.163830154
2363915.37449875709710.036305275
#Sta/Elev= 30
       0 2452.61    24.4 2445.73    36.8 2439.46    56.2 2432.14    93.6 2422.92
    98.8  2419.8   110.7 2406.94   131.3 2390.26     138 2386.34   154.9 2382.48
   199.2 2383.72   215.3 2385.57   287.7 2383.24   314.3  2385.9   361.5 2386.38
   456.2 2384.69   483.5 2385.65   510.8  2384.9     521 2382.36   556.2 2381.47
   601.7 2381.65   624.4 2384.75   647.1 2385.91   768.9 2383.35   800.1  2384.6
   833.7 2383.59   865.8 2399.99   910.2 2411.96   934.3 2415.44   997.4 2417.67
#Mann= 5 ,-1,0
       0      .1       0     521    .045       0   601.7      .1       0
  792.48     .06       0  902.48      .1       0
Bank Sta=521,601.7
XS Rating Curve= 0 ,0
Exp/Cntr(USF)=0,0
Exp/Cntr=0.3,0.1

Type RM Length L Ch R = 1 ,38641   ,239.2,235,223.9
XS GIS Cut Line= 3
2363152.71978141710461.1684637492363793.57191379710088.797635427
2363986.50102276 709777.22872116
#Sta/Elev= 30
       0 2484.78    63.7 2480.75     152 2472.27   191.1 2462.72   207.6 2456.89
   263.1 2430.31   294.6 2405.09   310.5 2389.27   318.5 2384.56   327.8 2382.48
   350.3 2380.89   420.4 2380.87   494.4 2384.13   512.9 2380.99   540.6 2380.11
   546.8 2380.02   614.7 2380.32   660.9 2380.57   698.9 2383.23   730.3 2381.27
   784.1 2384.48   820.7 2381.66   839.5 2383.97   870.6 2384.39   886.6 2381.76
   914.8  2383.5   949.1    2381   991.4 2381.59  1036.3 2393.14  1107.6 2403.95
#Mann= 5 ,-1,0
       0      .1       0   540.6    .045       0   614.7      .1       0
  901.18     .06       0 1021.18      .1       0
Bank Sta=540.6,614.7
XS Rating Curve= 0 ,0
Exp/Cntr=0.3,0.1

Type RM Length L Ch R = 1 ,38406   ,272.6,267.7,268.5
XS GIS Cut Line= 3
2363480.16782814710760.7495528872363756.83492589710303.782548748
2364151.62954851709834.381068306
#Sta/Elev= 30
       0 2450.56   139.8 2468.57   228.6 2476.99   293.5 2478.25   303.4 2475.76
   345.5 2452.94   368.9 2409.18   378.3 2402.23   393.9 2394.78     411 2378.99
   415.7 2377.81   432.5 2377.32   462.4 2377.96   471.8 2381.15   503.6 2378.23
   542.8 2381.93   579.4 2378.78   717.3 2377.88     731 2382.13   741.4 2382.51
     778 2380.04   812.8 2381.82   836.5 2379.57   881.2 2384.84   945.3 2380.02
   992.3 2381.78  1061.4  2380.4  1073.8 2383.14  1086.3 2392.02  1147.5 2399.43
#Mann= 5 ,-1,0
       0      .1       0   415.7    .045       0   462.4      .1       0
  864.19     .06       0  994.19      .1       0
Bank Sta=415.7,462.4
XS Rating Curve= 0 ,0
Exp/Cntr(USF)=0,0
Exp/Cntr=0.3,0.1

Type RM Length L Ch R = 1 ,38138   ,216.5,208.6,207.9
XS GIS Cut Line= 3
2363719.89717875710858.0795960162363895.87937742710565.148046484
2364255.43222523709810.478721642
#Sta/Elev= 30
       0 2404.88    16.1  2404.5      29 2401.48      85 2396.16   122.4 2398.73
   164.4 2397.43   201.7 2405.51     218 2407.25   346.1 2401.03   403.7 2410.07
   421.4 2415.41     426 2414.73     435 2405.71   452.5 2383.68     480 2377.07
   532.2 2377.33   638.6 2378.46     678 2375.41   696.2 2375.76     705 2381.53
   711.1 2382.91   770.2 2383.12   802.5 2380.42   829.1 2381.55   864.5 2378.93
   917.7 2378.52   974.8 2381.51  1049.2 2379.22  1112.7 2397.79  1177.7 2408.31
#Mann= 5 ,-1,0
       0      .1       0     480    .045       0   532.2      .1       0
  801.73     .06       0 1021.73      .1       0
Bank Sta=480,532.2
XS Rating Curve= 0 ,0
Exp/Cntr=0.3,0.1

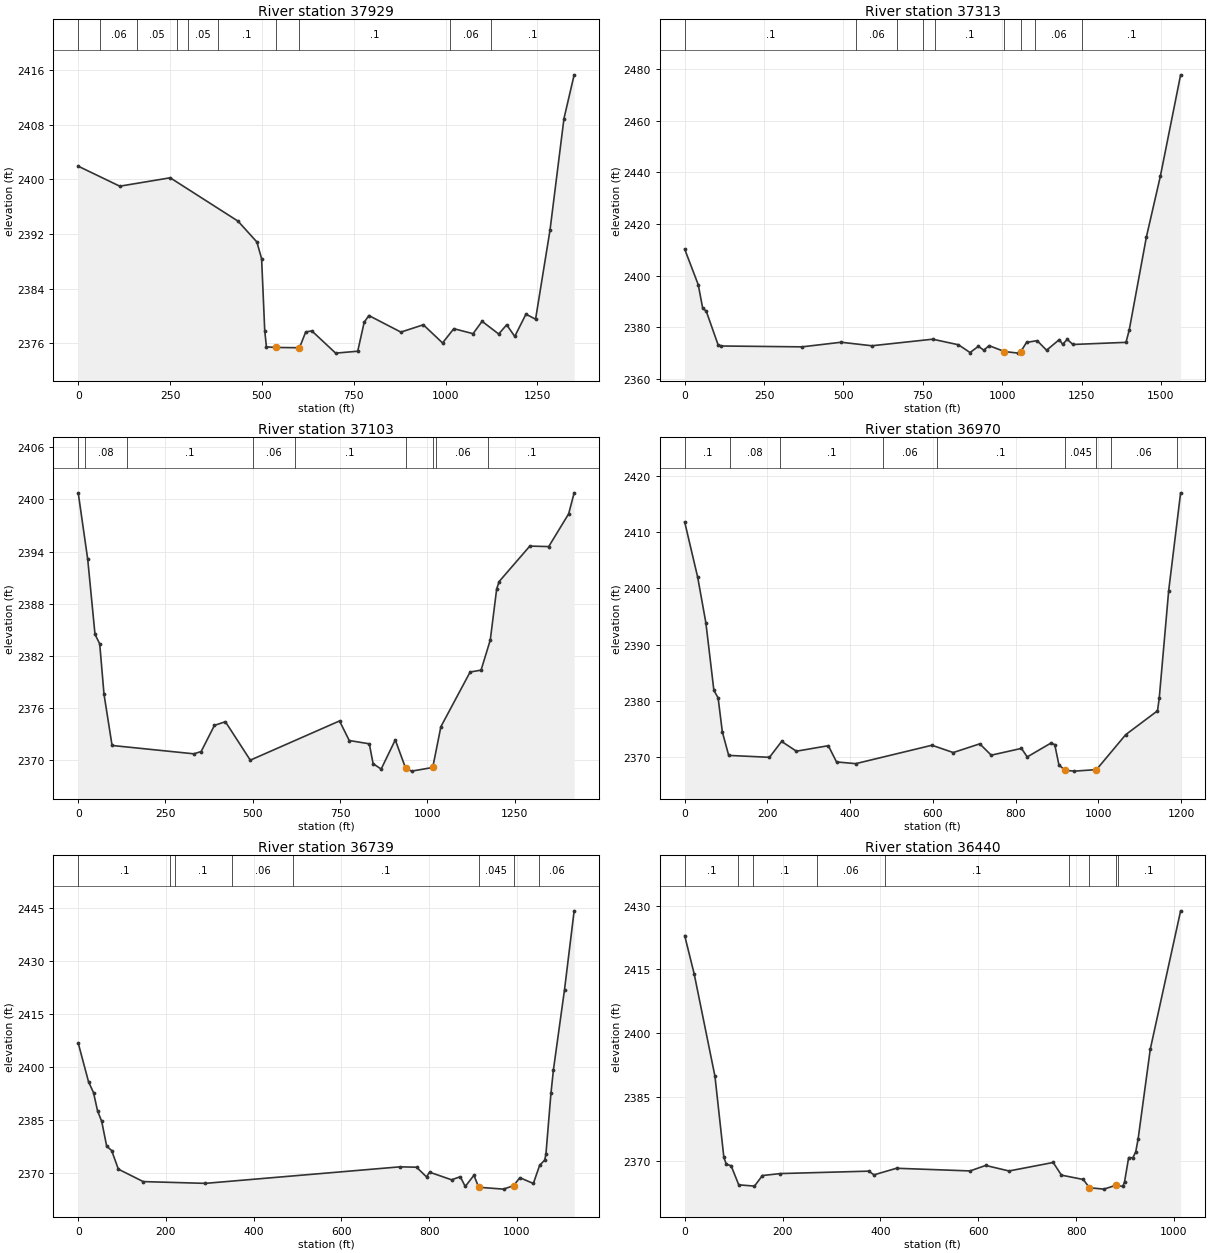
Type RM Length L Ch R = 1 ,37929   ,609.2,615.8,603
XS GIS Cut Line= 3
2363918.98977604711086.6975468812364201.56325003710356.482925982
2364428.46065208709837.000120087
#Sta/Elev= 30
       0 2401.95   113.1 2399.02   250.4 2400.25     435  2393.9   486.3 2390.85
   499.2  2388.4   507.7 2377.85   512.3 2375.49   537.1  2375.4   602.3 2375.36
   619.3 2377.68     636 2377.82   700.7 2374.57   760.8 2374.85   778.3 2379.07
     791 2380.08   878.3 2377.65   939.4 2378.72   991.7 2376.06  1022.3 2378.15
  1074.7 2377.42  1099.3 2379.23  1144.5 2377.37  1166.3 2378.72  1188.2 2377.01
  1218.7 2380.28  1244.9 2379.54  1284.2 2392.59  1322.2 2408.93  1349.9 2415.33
#Mann= 10 ,-1,0
       0      .1       0      60     .06       0     160     .05       0
     270      .1       0     300     .05       0     380      .1       0
   537.1    .045       0   602.3      .1       0 1012.98     .06       0
 1122.98      .1       0
Bank Sta=537.1,602.3
XS Rating Curve= 0 ,0
Exp/Cntr(USF)=0,0
Exp/Cntr=0.3,0.1

Type RM Length L Ch R = 1 ,37313   ,198.7,210.6,215.4
XS GIS Cut Line= 4
2364159.59689251711425.2261642332364598.84476791710625.067614129
 2364688.3729973710350.8874116452364898.20478491710057.122908984
#Sta/Elev= 30
       0 2410.32    42.8 2396.53    56.4 2387.68    68.2 2386.21     105 2373.39
   115.4 2372.84   369.7 2372.51   492.9 2374.29   589.6 2372.93   781.1 2375.47
   862.5 2373.31   898.9 2370.31   925.3 2372.72   942.1 2371.23     959 2372.97
  1007.3 2370.69  1051.5 2370.08  1058.8 2370.67  1076.8 2374.23  1110.4 2374.91
  1139.9  2371.2  1180.2 2375.32  1190.4 2373.49  1205.2 2375.38    1223 2373.43
  1390.1 2374.25  1400.2 2378.94  1454.6 2415.15  1498.3  2438.5  1562.2 2477.76
#Mann= 9 ,-1,0
       0      .1       0     540     .06       0     670      .1       0
     750     .06       0     790      .1       0  1007.3    .045       0
  1058.8      .1       0 1102.79     .06       0 1251.22      .1       0
Bank Sta=1007.3,1058.8
XS Rating Curve= 0 ,0
Exp/Cntr(USF)=0,0
Exp/Cntr=0.3,0.1

Type RM Length L Ch R = 1 ,37103   ,137.1,132.6,135.7
XS GIS Cut Line= 3
2364213.68158753711444.5211456912364694.07723404710760.978898537
     2365071.166       710313.14
#Sta/Elev= 30
       0 2400.75    27.2 2393.12    48.1 2384.49    61.6 2383.39    73.9  2377.6
      97 2371.71   331.3 2370.75   352.2 2371.01   390.3 2374.02   421.7 2374.44
     493 2370.02   748.7 2374.53   776.5 2372.28     834  2371.9   844.9 2369.61
     868    2369   908.4 2372.35   938.1 2369.09   955.5 2368.76  1015.7 2369.18
  1039.1 2373.87  1122.8 2380.15  1154.2 2380.37  1180.6 2383.83  1198.9  2389.7
  1205.9 2390.55  1293.9 2394.63    1348 2394.57  1405.2 2398.34  1420.9 2400.75
#Mann= 9 ,-1,0
       0      .1       0      20     .08       0     140      .1       0
     500     .06       0     620      .1       0   938.1    .045       0
  1015.7      .1       0 1025.47     .06       0 1175.47      .1       0
Bank Sta=938.1,1015.7
XS Rating Curve= 0 ,0
Exp/Cntr=0.3,0.1

Type RM Length L Ch R = 1 ,36970   ,225.7,231.5,234.6
XS GIS Cut Line= 2
2364271.23346345711508.3252115732365019.03853504710571.320759969
#Sta/Elev= 30
       0 2411.83    31.4    2402    51.3 2393.84    70.6 2381.84    80.8 2380.51
    91.1 2374.42   106.4 2370.26     205 2369.92   234.3 2372.75   270.1 2371.01
   347.3 2371.99     367  2369.1   413.4 2368.79   597.7 2372.07   649.2 2370.77
   713.3 2372.32     741  2370.3   814.1 2371.51     828 2369.99   885.2 2372.45
   894.5 2372.19   904.7 2368.55   919.62367.605   942.2 2367.46   995.4 2367.73
    1066 2373.95  1142.9  2378.2  1147.1 2380.43  1169.9 2399.57  1198.8 2417.02
#Mann= 9 ,-1,0
       0      .1       0     110     .08       0     230      .1       0
     480     .06       0     610      .1       0   919.6    .045       0
   995.4      .1       0    1030     .06       0    1190      .1       0
Bank Sta=919.6,995.4
XS Rating Curve= 0 ,0
Exp/Cntr(USF)=0,0
Exp/Cntr=0.3,0.1

Type RM Length L Ch R = 1 ,36739   ,278.5,298.3,312.3
XS GIS Cut Line= 2
2364368.98228482711581.7901001442365169.58786813710783.544790257
#Sta/Elev= 30
       0 2406.87    23.5 2395.94    34.9 2392.85      44 2387.74    53.6  2384.7
    64.9 2377.71    76.2 2376.49    91.5 2371.22   148.2  2367.7   289.8  2367.2
   733.2 2371.87   771.3 2371.77     794 2369.03     801 2370.36   851.2 2368.21
     871 2369.08   882.3 2366.32   902.1 2369.48     913  2366.1   969.6 2365.57
   992.6 2366.57  1006.8  2368.8  1037.6 2367.17    1052 2372.32  1063.4 2373.78
  1066.2 2375.38  1077.7 2392.64  1083.4 2399.35  1108.6 2421.93  1130.6 2444.25
#Mann= 8 ,-1,0
       0      .1       0     210     .08       0     220      .1       0
     350     .06       0     490      .1       0     913    .045       0
   992.6      .1       0    1050     .06       0
Bank Sta=913,992.6
XS Rating Curve= 0 ,0
Exp/Cntr=0.3,0.1

Type RM Length L Ch R = 1 ,36440   ,187.5,189.6,191
XS GIS Cut Line= 5
2364516.66362381711693.8578296542364859.47049964 711394.72236751
2365093.28267323711190.7087469872365259.48912975711135.306594812
2365316.03525923711088.783092256
#Sta/Elev= 30
       0 2422.95    19.3 2414.01    61.9 2389.85    80.1 2370.77    85.2 2369.16
    94.9 2368.82   110.5 2364.32   142.7 2364.02   158.9 2366.51   195.7 2366.97
   376.3 2367.54   386.9 2366.67     433 2368.22   583.3 2367.59   615.3 2368.88
   662.9 2367.58   753.2 2369.58   770.1  2366.6   814.7 2365.58   827.4 2363.64
   856.9 2363.31   881.3 2364.22   895.3 2363.96     899 2364.96   907.5 2370.74
   915.9 2370.67   921.9 2372.06   926.9 2375.16   951.7 2396.24  1013.7 2428.78
#Mann= 9 ,-1,0
       0      .1       0     110     .08       0     140      .1       0
     270     .06       0     410      .1       0  785.28     .06       0
   827.4    .045       0   881.3     .06       0  885.28      .1       0
Bank Sta=827.4,881.3
XS Rating Curve= 0 ,0
Exp/Cntr(USF)=0,0
Exp/Cntr=0.3,0.1

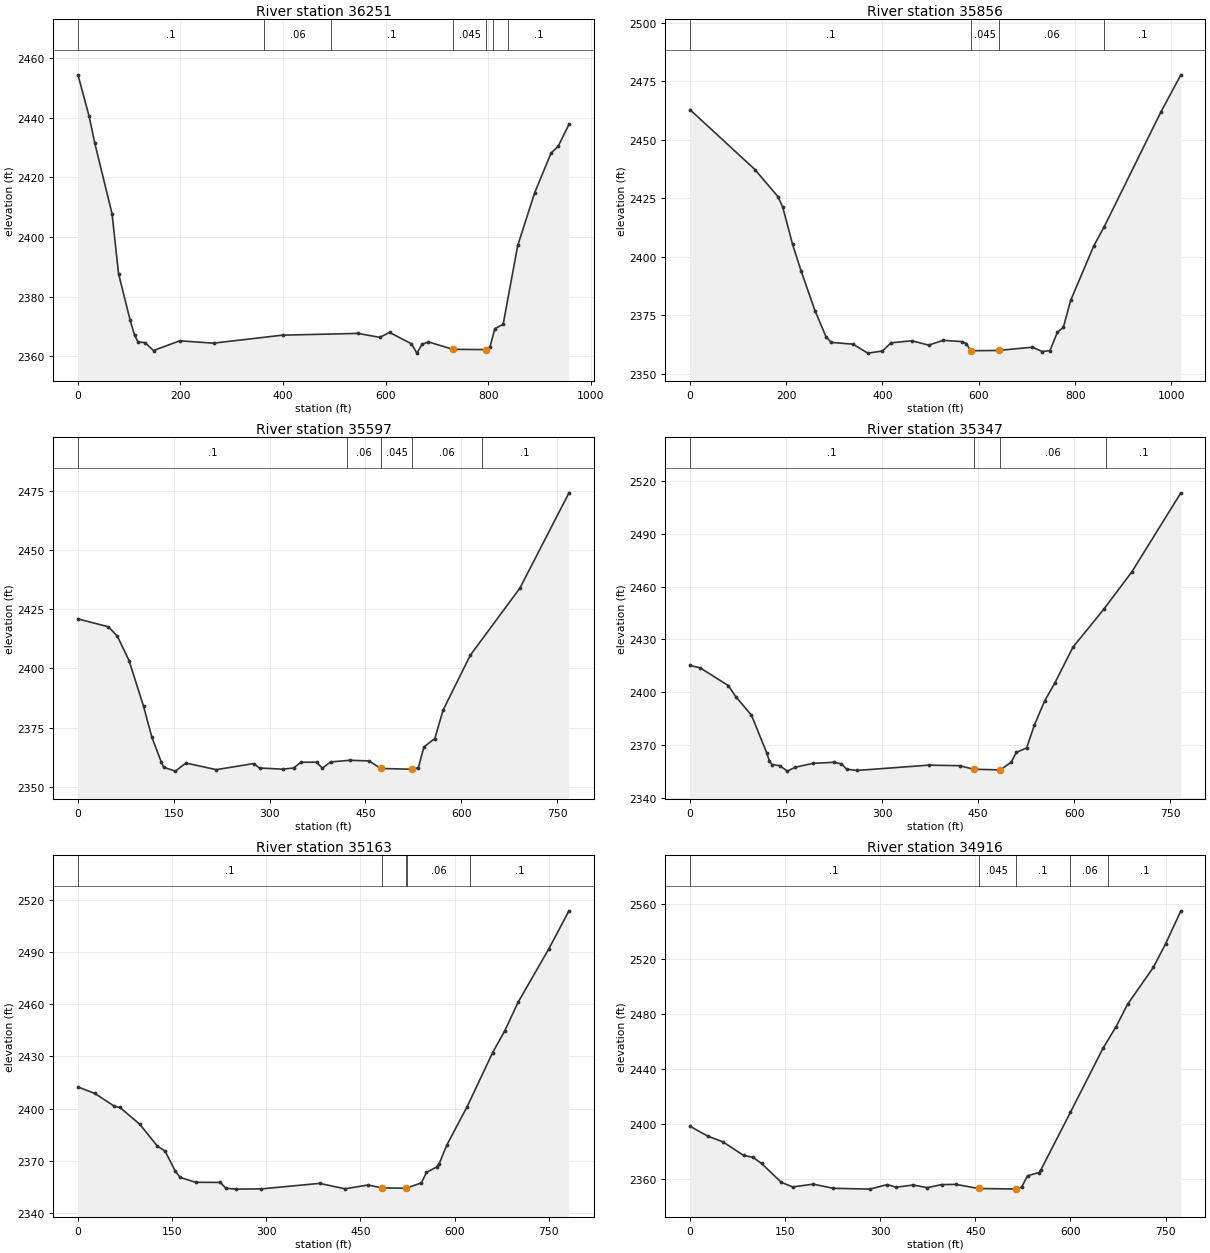
Type RM Length L Ch R = 1 ,36251   ,397.7,394.7,393
XS GIS Cut Line= 4
2364630.51585311711798.7897533972364906.16052839711577.462803416
2365142.22124098711367.7647916472365420.64530622711291.989086636
#Sta/Elev= 30
       0 2454.45    21.7 2440.57    32.9 2431.43    66.5 2407.85    79.1 2387.77
   101.9 2372.02   110.4 2367.04   117.6 2364.75   130.4 2364.62   147.4 2361.94
   198.6 2365.19   264.5 2364.41     399 2367.09   546.7 2367.68   588.8 2366.34
   607.7 2368.01   650.5  2364.2   661.2 2361.06   671.3 2364.06   683.7 2364.82
   731.6 2362.33   796.8 2362.24   803.9 2363.24   813.1 2369.26   829.4 2370.74
   857.8 2397.18     891 2414.92   922.8 2428.17   936.6 2430.44   957.8 2437.82
#Mann= 7 ,-1,0
       0      .1       0   363.5     .06       0   493.5      .1       0
   731.6    .045       0   796.8      .1       0  809.25     .06       0
  839.25      .1       0
Bank Sta=731.6,796.8
XS Rating Curve= 0 ,0
Exp/Cntr=0.3,0.1

Type RM Length L Ch R = 1 ,35856   ,260.4,259.6,260.2
XS GIS Cut Line= 2
2364715.76599129711969.3853612522365654.56895217711571.482119553
#Sta/Elev= 30
       0 2462.95   135.1 2437.29   182.9 2425.71   192.7 2421.31   213.3 2405.31
   230.7 2394.08   259.8 2376.98   282.8 2365.79   293.4 2363.38   338.8 2362.61
   369.5 2358.78     400 2359.68   417.5 2363.18     461 2364.08   495.7  2362.2
   526.1 2364.25   565.2 2363.71   573.9 2362.89   583.3 2359.79   641.2 2359.94
   711.4 2361.31   731.8 2359.47   747.7 2359.86   763.3 2367.75   775.5 2369.75
   790.7 2381.31   838.9  2404.7     860 2412.65   977.9 2461.81  1019.6 2477.78
#Mann= 4 ,-1,0
       0      .1       0   583.3    .045       0   641.2     .06       0
     860      .1       0
Bank Sta=583.3,641.2
XS Rating Curve= 0 ,0
Exp/Cntr(USF)=0,0
Exp/Cntr=0.3,0.1

Type RM Length L Ch R = 1 ,35597   ,240.1,249.1,253.9
XS GIS Cut Line= 3
     2365029.716      712103.3172365348.73385605711932.873953197
2365727.70747512711784.818906394
#Sta/Elev= 30
       0 2420.93    47.7 2417.59    61.7  2413.6    79.9 2403.34   102.6 2384.05
   115.7 2370.89   130.5 2360.41   134.3 2358.21   152.4 2356.59   168.9    2360
   216.7 2357.21   274.9 2359.79   284.2 2357.91   320.2 2357.42   337.4  2357.9
   349.2 2360.36   373.4 2360.36   382.6 2357.84   395.5 2360.47   425.5 2361.17
   455.6  2360.9     474 2357.72   523.3 2357.38   532.9 2358.05   541.5 2366.79
   558.6 2370.38   571.5 2382.37   614.2 2405.61   691.8 2433.95   768.6 2474.22
#Mann= 5 ,-1,0
       0      .1       0  421.69     .06       0     474    .045       0
   523.3     .06       0  631.69      .1       0
Bank Sta=474,523.3
XS Rating Curve= 0 ,0
Exp/Cntr=0.3,0.1

Type RM Length L Ch R = 1 ,35347   ,177.9,184,188.1
XS GIS Cut Line= 2
2365052.36424312712165.3226064292365816.08670742712100.079983851
#Sta/Elev= 30
       0 2415.09    15.9 2413.79      60 2403.68    72.1 2397.17    96.2 2386.82
   120.2 2365.24   124.3 2360.61   128.3 2358.79   140.3 2358.12   152.4 2355.03
   164.4 2357.25   192.3 2359.45   224.6 2360.06   236.7 2359.16   244.7 2356.13
   260.8 2355.41   373.2 2358.44   421.3 2358.12     443 2356.11   484.5 2355.72
   501.6 2360.13   509.7 2365.71   525.7 2368.22   537.8  2381.2   553.8 2394.92
   569.9 2405.25     598 2425.49   646.2 2447.08   690.3 2468.52   766.5 2513.26
#Mann= 4 ,-1,0
       0      .1       0     443    .045       0   484.5     .06       0
     650      .1       0
Bank Sta=443,484.5
XS Rating Curve= 0 ,0
Exp/Cntr(USF)=0,0
Exp/Cntr=0.3,0.1

Type RM Length L Ch R = 1 ,35163   ,234.5,247,249.3
XS GIS Cut Line= 3
2364986.60823756712236.4311427732365358.13214159712285.446094788
2365760.24185545712350.743475712
#Sta/Elev= 30
       0  2412.5      27 2408.74    58.1 2401.41    66.9 2400.71    98.4  2391.1
   126.4 2378.57   138.8 2375.63   155.3    2364     163  2360.5   187.4 2357.74
   226.6 2357.67   235.6 2354.33   251.6 2353.82   292.1 2353.97   384.9 2357.12
   425.4 2354.01   461.9 2356.19   484.4 2354.52   522.7 2354.34     547  2357.4
   555.1 2363.43   571.1 2366.51   575.4 2368.46   587.5 2379.14     620 2401.27
   660.5 2432.25   679.6 2444.61     701 2461.09   750.1 2491.92   782.1 2513.65
#Mann= 5 ,-1,0
       0      .1       0   484.4    .045       0   522.7      .1       0
  524.74     .06       0  624.74      .1       0
Bank Sta=484.4,522.7
XS Rating Curve= 0 ,0
Exp/Cntr=0.3,0.1

Type RM Length L Ch R = 1 ,34916   ,209.3,215.6,219.3
XS GIS Cut Line= 2
2364971.77041523 712307.321255572365658.73685296712664.236779085
#Sta/Elev= 30
       0 2398.25    28.4 2390.98    52.1 2386.87    84.7 2376.98    99.6 2375.56
   113.1  2371.1   144.1  2357.4   161.9 2354.01   194.5 2356.06   225.8 2353.05
   283.5 2352.42   311.5 2355.73     325 2353.84   352.1 2355.41   374.6  2353.5
   397.1 2355.73   419.7 2355.88   455.2 2352.88   514.3 2352.51   523.3 2353.98
   532.4 2362.16   550.4 2364.49   553.4 2366.38     600  2408.3   651.3 2454.83
   672.1 2470.77   690.1 2486.91   730.7 2513.78   750.2 2531.11   774.2 2555.02
#Mann= 5 ,-1,0
       0      .1       0   455.2    .045       0   514.3      .1       0
     600     .06       0     660      .1       0
Bank Sta=455.2,514.3
XS Rating Curve= 0 ,0
Exp/Cntr(USF)=0,0
Exp/Cntr=0.3,0.1

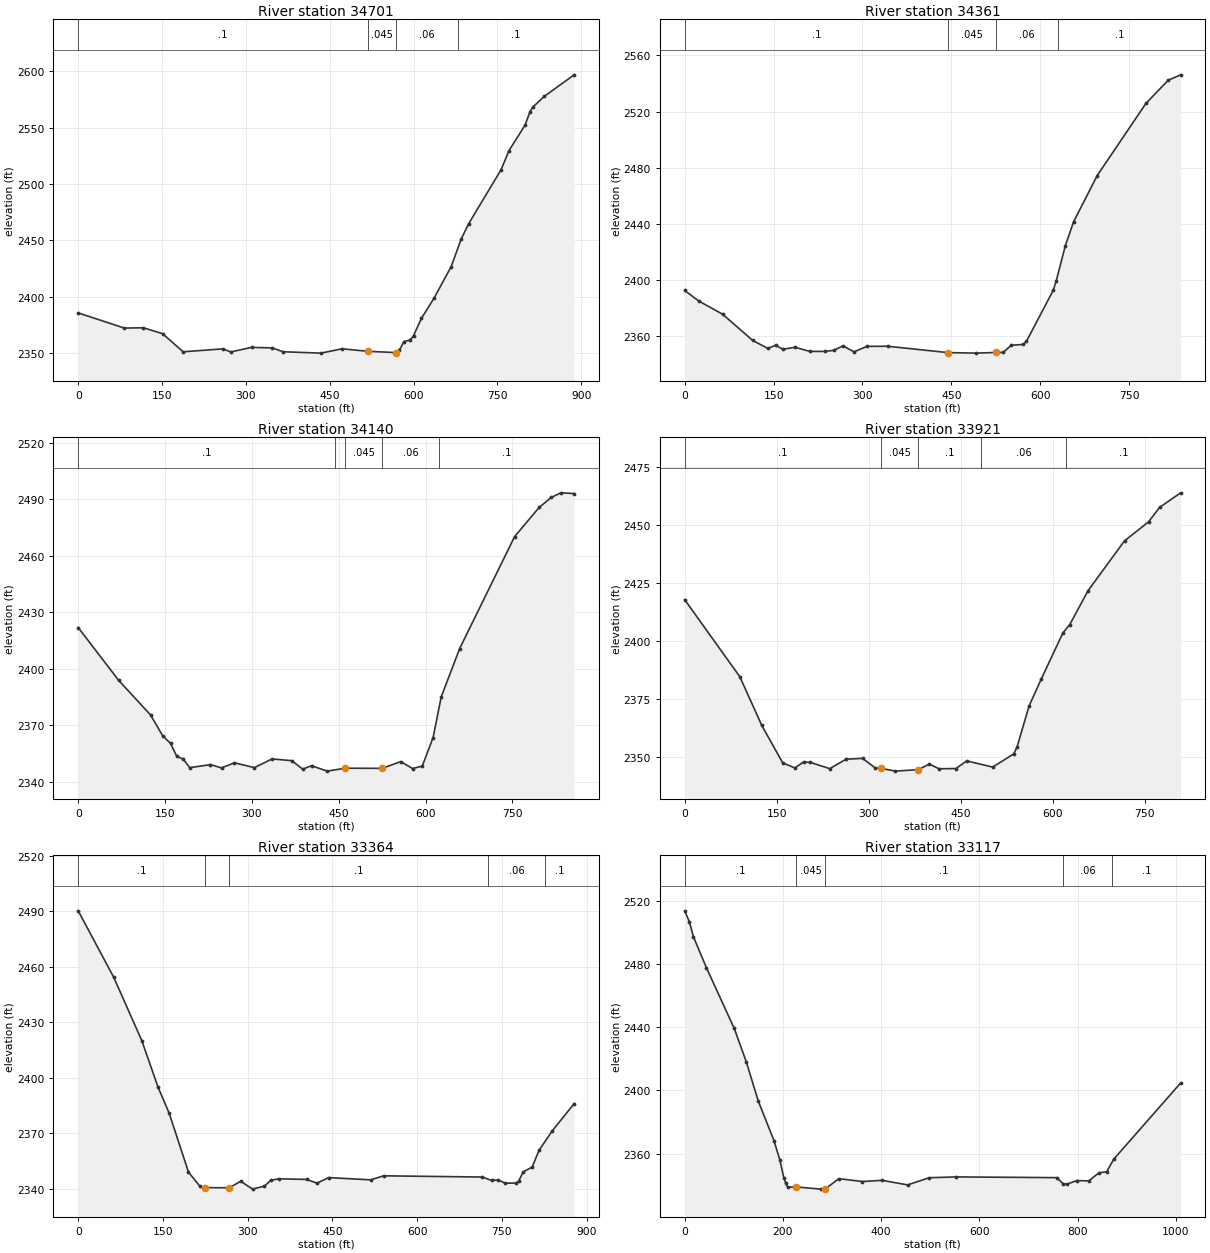
Type RM Length L Ch R = 1 ,34701   ,334.7,339.8,341.5
XS GIS Cut Line= 3
2364892.22447571 712380.916237562365461.93290639712848.035000591
2365584.62138033  712935.2135705
#Sta/Elev= 30
       0  2385.9    82.4 2372.51   116.7 2372.72   150.8 2367.57   187.7 2351.49
   258.6 2354.08     273 2351.36   310.3 2355.39   347.4 2354.93   366.3 2351.52
   434.4 2350.31     472 2354.14   517.7 2351.95   568.2 2350.79   574.5 2352.81
   582.8 2360.56   594.2 2361.92   599.9 2365.84   614.1 2381.13   636.2 2398.69
   667.2 2426.86   685.1 2451.25   698.2 2464.61   756.4 2512.57   770.7 2529.62
   799.4 2552.08     808 2563.62   813.1    2568   833.8 2577.57   887.2 2596.62
#Mann= 4 ,-1,0
       0      .1       0   517.7    .045       0   568.2     .06       0
     680      .1       0
Bank Sta=517.7,568.2
XS Rating Curve= 0 ,0
Exp/Cntr=0.3,0.1

Type RM Length L Ch R = 1 ,34361   ,214.1,221.4,224
XS GIS Cut Line= 2
2364733.82673289712514.5625272882365248.09211086713174.664355724
#Sta/Elev= 30
       0  2392.6    23.6 2385.13    64.2 2375.63   114.7 2357.03   140.2 2351.34
   153.5 2353.57   165.6 2350.73   185.9 2352.15   211.6 2349.18   237.3 2349.21
   251.8 2350.01     267 2353.18   285.7  2348.9   307.6 2352.79   342.3 2352.88
   444.5 2348.34   490.9 2347.98   525.1 2348.43   537.5 2348.51   550.9 2353.55
   571.2 2354.18   576.6 2356.33     622 2392.84     627 2399.55   642.2 2424.32
   656.2 2441.48   696.1 2474.44   778.3  2525.8   815.8 2542.27   836.8 2546.14
#Mann= 4 ,-1,0
       0      .1       0   444.5    .045       0   525.1     .06       0
     630      .1       0
Bank Sta=444.5,525.1
XS Rating Curve= 0 ,0
Exp/Cntr(USF)=0,0
Exp/Cntr=0.3,0.1

Type RM Length L Ch R = 1 ,34140   ,231.1,218.2,221
XS GIS Cut Line= 4
2364559.67085495712592.3198947922364770.37714647712888.321839446
2364939.16637873   713163.1213282365028.82487005713308.690446146
#Sta/Elev= 30
       0 2421.94    69.8 2393.94     125 2375.51   145.7 2364.59   159.5 2360.39
   170.2  2353.6   181.7 2352.05   192.5 2347.53   228.5 2349.14   247.6 2347.42
   269.9 2350.11   304.4 2347.54   334.9 2352.17     369 2351.24   387.8 2346.76
   403.1 2348.56   430.1 2345.69   461.2 2347.24   525.2 2347.17   557.2 2350.73
   577.6 2347.08   594.4 2348.36   613.1 2363.53   627.2 2385.16     659 2410.79
     754 2470.29   796.3 2485.75   817.4 2491.08   833.9 2493.51   856.8 2493.13
#Mann= 5 ,-1,0
       0      .1       0  443.34     .06       0   461.2    .045       0
   525.2     .06       0  623.34      .1       0
Bank Sta=461.2,525.2
XS Rating Curve= 0 ,0
Exp/Cntr=0.3,0.1

Type RM Length L Ch R = 1 ,33921   ,548.1,557.3,546.8
XS GIS Cut Line= 4
2364365.49672645712822.3508110722364560.28225339712990.813969508
2364709.00248107 713146.25278129 2364949.4671917713381.210666481
#Sta/Elev= 30
       0 2417.93    89.9 2384.74   125.8  2363.7   159.9 2347.58   179.7 2345.41
   193.9 2347.97   205.2 2347.78   236.7 2345.09   263.2 2349.17   290.2 2349.52
   310.6 2345.44     321 2345.18   343.8 2344.03   380.8 2344.66   399.2 2347.06
   414.7 2345.05   442.5 2345.14     460 2348.45   502.4 2345.76   536.4  2351.4
     542 2354.34   561.8 2372.14   581.6 2383.73   616.9 2403.61   628.1 2407.21
     658 2421.84   717.4 2443.29   756.7 2451.48   774.5 2457.68   808.9 2463.98
#Mann= 5 ,-1,0
       0      .1       0     321    .045       0   380.8      .1       0
  482.65     .06       0  622.65      .1       0
Bank Sta=321,380.8
XS Rating Curve= 0 ,0
Exp/Cntr(USF)=0,0
Exp/Cntr=0.3,0.1

Type RM Length L Ch R = 1 ,33364   ,262.4,247.2,231.9
XS GIS Cut Line= 3
2363991.71909367713201.3929175532364448.92043689 713518.21051652
2364770.45060372 713508.34812977
#Sta/Elev= 30
       0 2490.35    62.8 2454.43   112.5 2420.16     141 2395.18   161.1 2380.75
   195.2 2348.94   214.7 2341.55   224.4 2340.56   267.5 2340.45   287.6    2344
   308.6 2339.74   329.7 2341.38   341.2 2344.58   355.8 2345.33   404.5 2344.98
   422.7 2342.98   443.4 2345.98   517.6 2344.76   540.6 2346.94   715.6 2346.28
   731.6 2344.41   743.6 2344.73   755.6 2342.93   775.6 2343.04   779.6 2344.06
   787.6 2349.06   803.6 2351.68   815.6 2360.67   839.3 2371.35   877.9    2386
#Mann= 5 ,-1,0
       0      .1       0   224.4    .045       0   267.5      .1       0
  726.24     .06       0  826.24      .1       0
Bank Sta=224.4,267.5
XS Rating Curve= 0 ,0
Exp/Cntr(USF)=0,0
Exp/Cntr=0.3,0.1

Type RM Length L Ch R = 1 ,33117   ,237.8,236.7,235.7
XS GIS Cut Line= 3
2363854.52408096713562.6130847812364364.13446248713575.582190758
2364856.19456845713662.783809242
#Sta/Elev= 30
       0  2513.5     9.7 2506.48    17.7 2497.23    44.2 2477.59   100.9 2439.18
   125.7 2417.84   149.7 2393.38   181.7 2368.33   193.7 2356.18   201.7 2344.93
   205.7 2341.32   209.7 2338.88   226.5 2339.06   277.3 2337.66   286.5 2337.89
   313.8 2344.25   361.8 2342.47   402.1 2343.21   453.8 2340.33   497.8 2344.86
   552.6 2345.38   757.6 2344.91   769.8 2341.14   777.9 2340.78   798.2 2343.04
   822.6 2342.88   842.9  2347.9   859.2 2348.68   873.2 2356.52  1009.5 2404.71
#Mann= 5 ,-1,0
       0      .1       0   226.5    .045       0   286.5      .1       0
  769.78     .06       0  869.78      .1       0
Bank Sta=226.5,286.5
XS Rating Curve= 0 ,0
Exp/Cntr=0.3,0.1