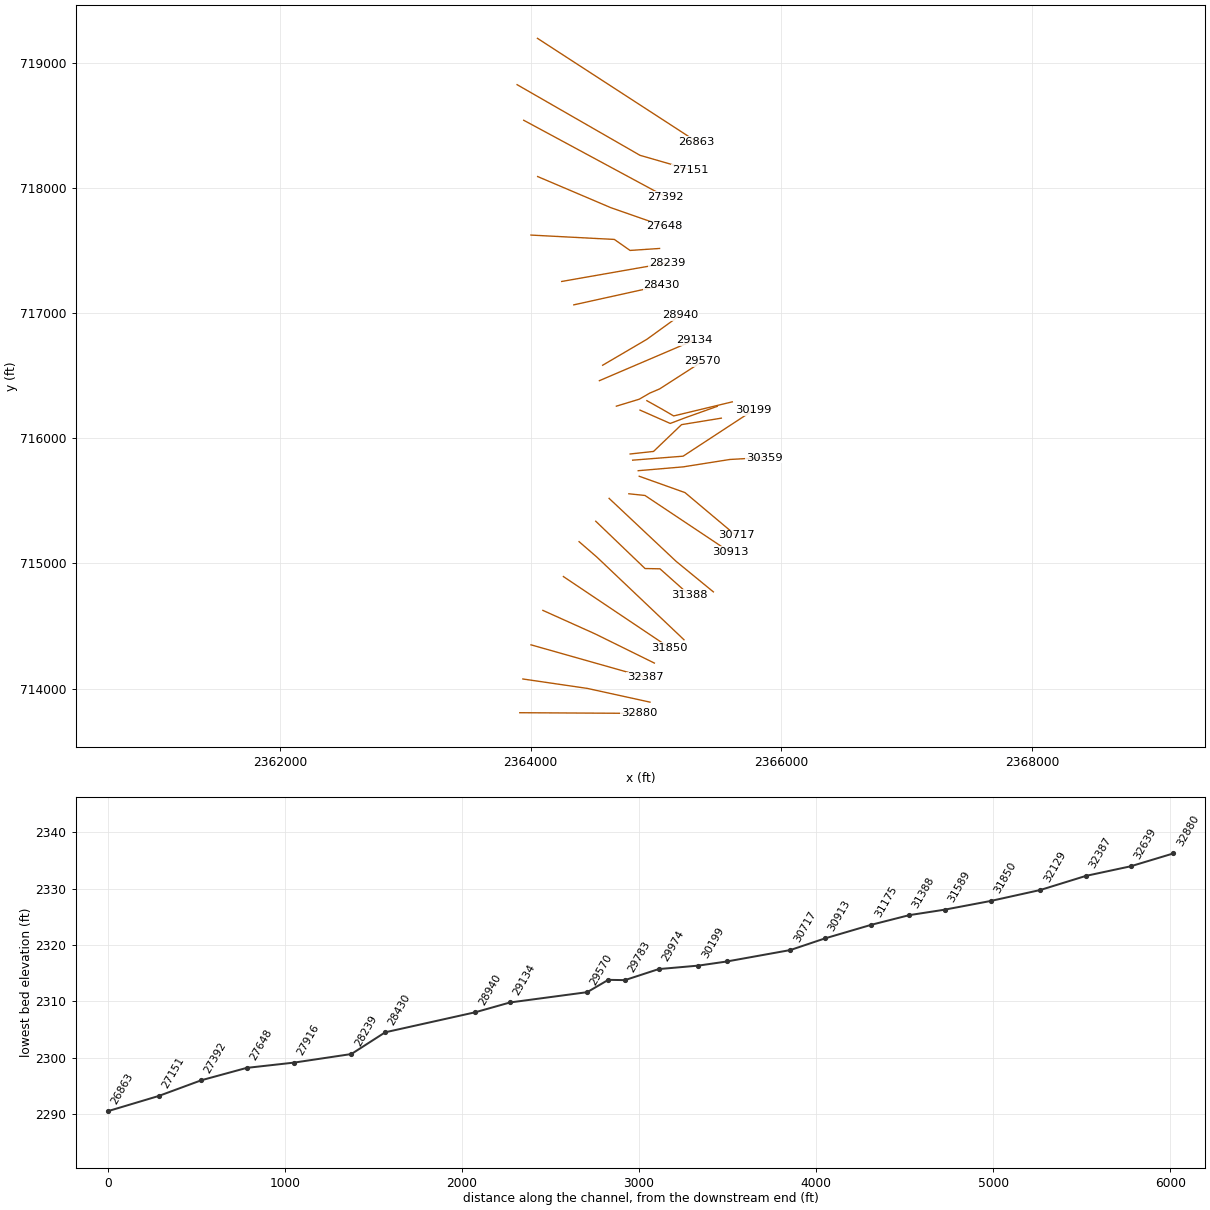
HEC-RAS study GLADYFK.prj: GLADYFK

--- GLADYFK.g01 (geometry) --- (continued)

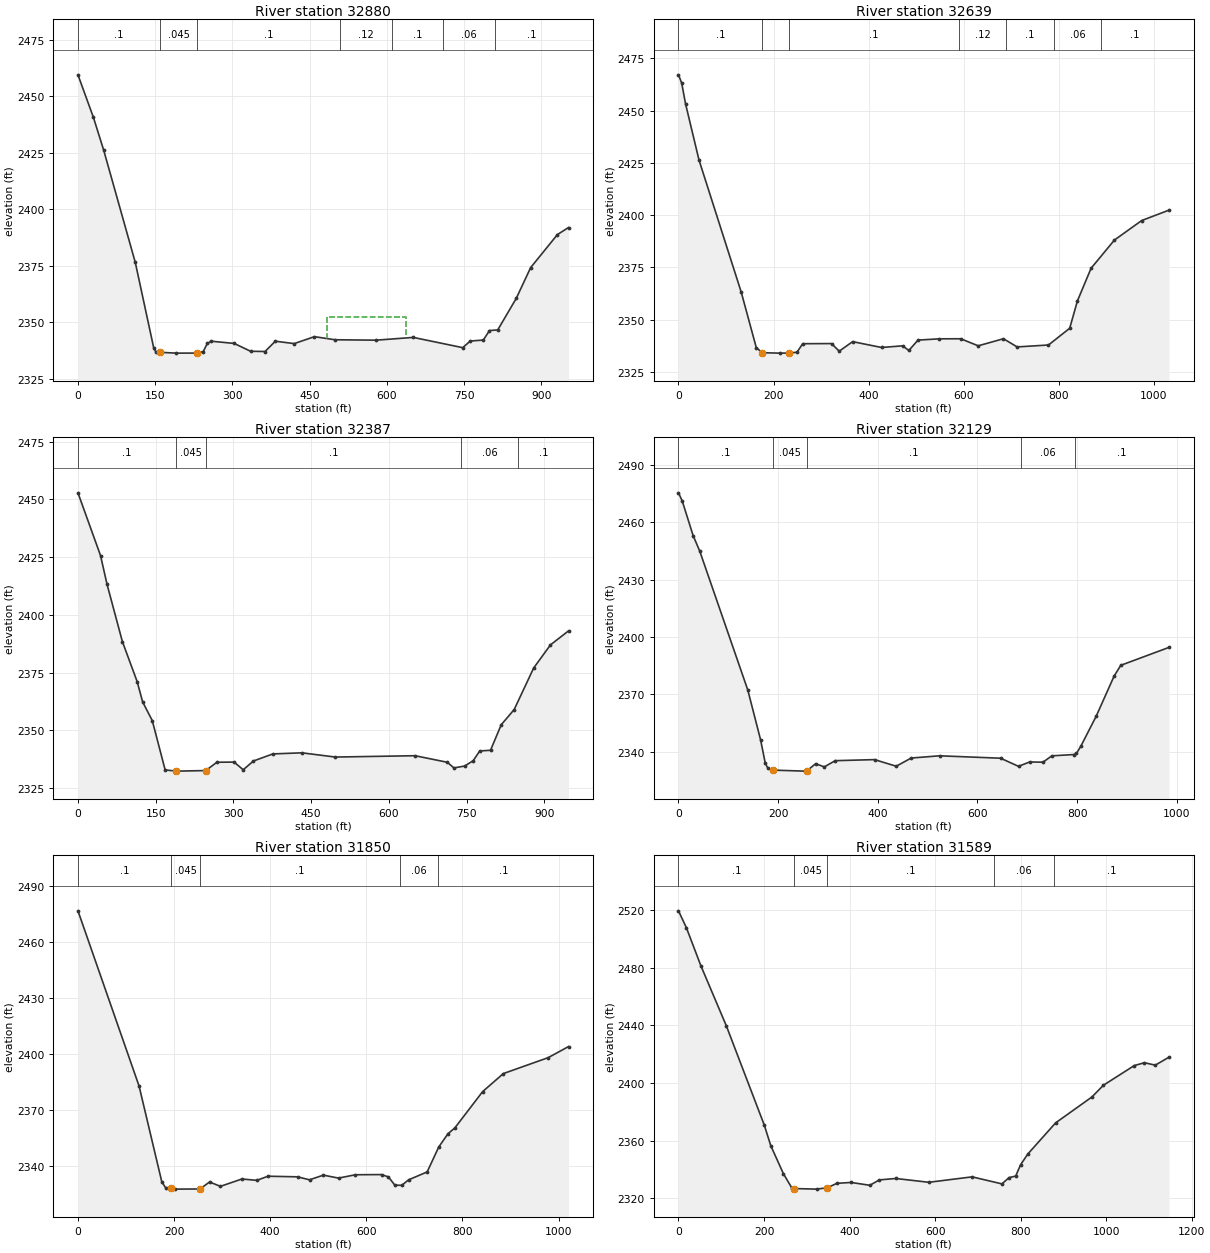
Type RM Length L Ch R = 1 ,32880   ,248.5,241.6,238.9
XS GIS Cut Line= 2
2363912.75198815713806.8073931812364865.62172806 713801.54291948
#Sta/Elev= 30
       0 2459.51      30 2440.69    50.1 2426.07   111.4 2376.41   147.4 2338.36
   151.4 2336.81   159.4 2336.61   191.4 2336.26   231.4 2336.28   243.4 2336.98
   251.4 2340.59   259.4 2341.53   303.4 2340.56   335.4 2337.08   363.4 2336.98
   383.4 2341.54   420.1 2340.48   459.4 2343.55   499.4 2342.18   579.4    2342
   651.4 2343.22   747.4 2338.68     762 2341.61   787.4 2342.05   799.4 2346.26
   815.4 2346.53   851.4 2360.51   879.4 2374.15   931.4 2388.77   952.9 2391.89
#Mann= 7 ,-1,0
       0      .1       0   159.4    .045       0   231.4      .1       0
     510     .12       0     610      .1       0     710     .06       0
     810      .1       0
#XS Ineff= 1 ,-1
  483.16  636.99 2352.08
Permanent Ineff=
       F
Bank Sta=159.4,231.4
XS Rating Curve= 0 ,0
Exp/Cntr(USF)=0,0
Exp/Cntr=0.3,0.1

Type RM Length L Ch R = 1 ,32639   ,257.1,252.1,249.8
XS GIS Cut Line= 3
 2363937.5153353714076.2097456562364451.88473801714001.015745656
2364952.43905594713891.280533703
#Sta/Elev= 30
       0 2467.11     6.7 2463.19    14.8 2453.28    43.1 2426.39     132 2363.16
   163.7 2336.59   176.5 2334.16   212.6 2333.97   233.1    2334   249.3  2334.4
   261.4 2338.48     322 2338.54   338.2  2334.9   366.5 2339.47   427.2 2336.67
   471.6 2337.46   484.7 2335.24     504  2340.2   548.8 2340.81   593.9 2340.84
   630.7 2337.47   683.9 2340.86   712.6 2336.94   778.6 2337.86   823.2 2345.86
   839.5 2358.97   868.2 2374.57   917.3 2388.06   974.7  2397.4  1032.3 2402.39
#Mann= 7 ,-1,0
       0      .1       0   176.5    .045       0   233.1      .1       0
  589.84     .12       0  689.84      .1       0  789.84     .06       0
  889.84      .1       0
Bank Sta=176.5,233.1
XS Rating Curve= 0 ,0
Exp/Cntr=0.3,0.1

Type RM Length L Ch R = 1 ,32387   ,263.4,258.1,254.2
XS GIS Cut Line= 2
2364002.24804107714349.0481843972364913.00199137714091.088973042
#Sta/Elev= 30
       0 2452.89    43.6 2425.69      56 2413.35    85.7 2388.45   114.3 2371.05
   124.8 2362.29   143.4 2354.18   168.3 2332.78   189.1  2332.3   190.3 2332.27
   246.6 2332.51   268.1 2336.12   301.3 2336.19   318.9 2332.86   338.7 2336.67
   376.2 2339.73   432.2  2340.2   496.7 2338.37   650.5 2338.95   712.9  2336.1
   725.4 2333.66   746.2 2334.47   762.8 2336.81   775.3 2341.01   796.1 2341.31
   816.8 2352.38   841.8 2358.97   879.4 2376.98   911.8 2386.99   946.6 2393.05
#Mann= 5 ,-1,0
       0      .1       0   189.1    .045       0   246.6      .1       0
     740     .06       0     850      .1       0
Bank Sta=189.1,246.6
XS Rating Curve= 0 ,0
Exp/Cntr(USF)=0,0
Exp/Cntr=0.3,0.1

Type RM Length L Ch R = 1 ,32129   ,284.8,278.8,273.5
XS GIS Cut Line= 3
2364097.35223992714624.1033323482364513.66571623714436.749665878
2364987.09685959714203.307760666
#Sta/Elev= 30
       0  2475.4     7.5 2471.14    29.4 2452.98    42.6 2444.92   139.1 2372.17
   164.7 2346.16   174.2 2333.83   178.6 2331.64   188.9 2330.29   253.1 2329.76
   257.5 2329.85   275.1 2333.64   292.6 2331.98   314.5 2335.23   393.5 2335.78
   436.9 2332.32     467 2336.61   523.8 2337.78   646.3 2336.52   682.3 2332.27
   704.6 2334.55   731.4 2334.44   749.2 2337.76   793.8 2338.45   798.6 2339.04
   807.2 2342.71   838.4 2358.62   874.1 2379.47   887.5 2385.13   984.4 2394.53
#Mann= 5 ,-1,0
       0      .1       0   188.9    .045       0   257.5      .1       0
  686.53     .06       0  796.53      .1       0
Bank Sta=188.9,257.5
XS Rating Curve= 0 ,0
Exp/Cntr=0.3,0.1

Type RM Length L Ch R = 1 ,31850   ,266.7,260.3,255.9
XS GIS Cut Line= 2
2364260.82734478714894.3877260642365108.37990132714325.575716197
#Sta/Elev= 30
       0 2476.88   127.2 2383.01   174.4 2331.83   182.3 2328.56   193.5 2328.57
   201.5 2327.82   254.1 2327.91   273.8 2331.64   296.5 2329.31   341.2 2333.25
   372.3 2332.52   395.3 2334.73   456.9 2334.41   481.8 2332.81   510.6 2335.31
   542.3 2333.73   577.3 2335.52   631.7 2335.61   646.1 2334.35   659.2 2329.99
   673.6 2329.84   688.1 2332.82   726.6 2337.03   750.7 2350.38     770  2357.5
   784.2  2360.6   842.1 2380.07   885.1 2389.71   978.4 2398.24  1020.7 2404.17
#Mann= 5 ,-1,0
       0      .1       0   193.5    .045       0   254.1      .1       0
     670     .06       0     750      .1       0
Bank Sta=193.5,254.1
XS Rating Curve= 0 ,0
Exp/Cntr(USF)=0,0
Exp/Cntr=0.3,0.1

Type RM Length L Ch R = 1 ,31589   ,200,201.1,201.9
XS GIS Cut Line= 3
2364386.01133412  715173.05257052364527.78261848715050.198763031
2365223.52147926714389.544236379
#Sta/Elev= 30
       0 2519.57    18.5  2507.8    52.5 2481.29     112 2439.58   200.7 2370.65
   215.7 2356.49   245.2 2337.05   264.6 2327.26   270.4 2326.67   322.7 2326.27
   348.1 2327.21   370.2 2330.29   403.6 2330.91   447.4 2328.93   469.5 2332.67
   508.1 2333.66   585.3 2331.02   686.6 2334.79   756.3 2329.91   772.8 2334.26
   788.4 2335.33   799.7 2343.11   816.7 2350.65   881.8  2372.3   966.7 2390.29
   993.5 2398.42  1065.7  2412.1  1089.5 2414.07  1114.8 2412.37    1147 2417.95
#Mann= 5 ,-1,0
       0      .1       0   270.4    .045       0   348.1      .1       0
   737.6     .06       0   877.6      .1       0
Bank Sta=270.4,348.1
XS Rating Curve= 0 ,0
Exp/Cntr=0.3,0.1

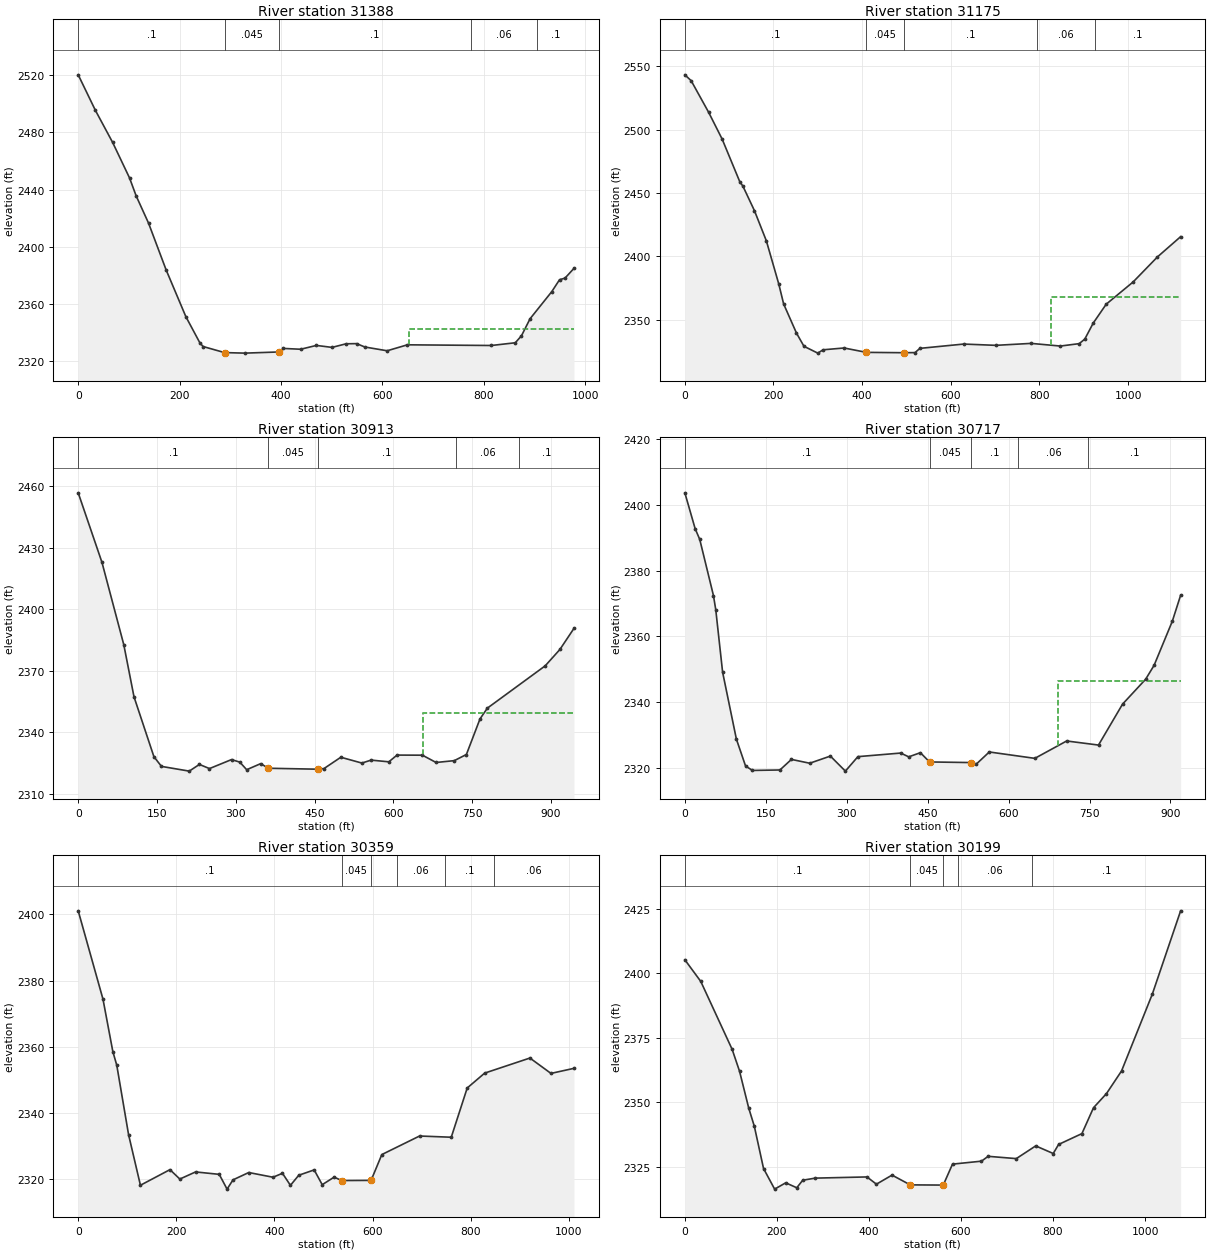
Type RM Length L Ch R = 1 ,31388   ,221.9,213.6,216.5
XS GIS Cut Line= 4
2364519.17224169 715336.293470782364912.58913349714958.464889864
2365031.83318287714956.2566667282365265.38411131 714748.14056759
#Sta/Elev= 30
       0 2520.42      34 2495.44    67.9 2473.02   101.2 2448.14   114.2 2435.61
   138.7 2416.43   173.3  2383.7   212.3 2350.85   239.9 2332.51   246.2 2329.93
   288.6 2325.66   328.6 2325.29   396.1 2326.11   404.6 2328.58   438.6 2328.01
   469.7 2330.69   500.5 2329.31   528.3 2331.84   549.1 2331.95   565.1 2329.59
   609.2 2326.94   649.1 2331.12   814.5 2330.64   861.8 2332.55     874 2337.41
     891  2349.4   933.9 2368.45   949.1 2376.75   959.9 2377.88   977.6 2384.73
#Mann= 5 ,-1,0
       0      .1       0   288.6    .045       0   396.1      .1       0
  774.73     .06       0  904.73      .1       0
#XS Ineff= 2 , 0
                          652.48         2342.07
Permanent Ineff=
       F       F
Bank Sta=288.6,396.1
XS Rating Curve= 0 ,0
Exp/Cntr(USF)=0,0
Exp/Cntr=0.3,0.1

Type RM Length L Ch R = 1 ,31175   ,252,262,267.9
XS GIS Cut Line= 3
2364625.80319017715518.8249520152365161.47028732715015.135664696
2365457.98571564714772.096522515
#Sta/Elev= 30
       0 2543.42    14.2  2538.8    53.8 2513.74    84.2 2492.62     124 2458.94
   130.9 2455.57     157 2436.14   183.9 2412.31   211.9 2378.24   222.9 2362.44
   251.9  2339.4   268.8 2328.97     300 2323.58   311.9 2326.21   359.4 2327.64
   409.6 2324.18   495.2  2323.9   519.4    2324   530.4 2327.34   629.2 2330.74
   701.8 2329.73   781.2 2331.27   847.4 2329.17   889.8 2331.07   902.4 2334.63
   921.4 2347.26   950.8 2362.24  1011.5 2379.79  1066.5 2399.61  1118.7 2415.57
#Mann= 5 ,-1,0
       0      .1       0   409.6    .045       0   495.2      .1       0
  795.28     .06       0  925.28      .1       0
#XS Ineff= 2 , 0
                          826.91         2367.53
Permanent Ineff=
       F       F
Bank Sta=409.6,495.2
XS Rating Curve= 0 ,0
Exp/Cntr=0.3,0.1

Type RM Length L Ch R = 1 ,30913   ,208,195.8,193.1
XS GIS Cut Line= 3
2364783.21573502715555.5517813542364912.01291918715542.117885117
2365589.32501129 715090.31914063
#Sta/Elev= 30
       0 2456.65    45.2 2422.81    86.8 2382.68   106.2 2357.35   144.1 2328.19
   158.5 2323.46   211.4 2321.16   230.7 2324.42   249.9  2322.4   291.8 2326.78
   307.6 2325.55   320.7 2321.85   347.4 2324.81   361.9 2322.56   455.6  2322.1
   467.8  2322.4   499.9 2327.92   539.9 2325.09   557.6 2326.52   591.3 2325.69
   606.9 2328.97   655.2 2328.92   681.2 2325.37   715.8 2326.26   738.9 2329.25
   764.8 2346.58   778.8 2351.82   888.9 2372.42   916.9 2380.39   943.7 2390.67
#Mann= 5 ,-1,0
       0      .1       0   361.9    .045       0   455.6      .1       0
   719.5     .06       0   839.5      .1       0
#XS Ineff= 2 , 0
                          655.74         2349.55
Permanent Ineff=
       F       F
Bank Sta=361.9,455.6
XS Rating Curve= 0 ,0
Exp/Cntr(USF)=0,0
Exp/Cntr=0.3,0.1

Type RM Length L Ch R = 1 ,30717   ,330.9,358.2,386.8
XS GIS Cut Line= 3
2364866.22305848715695.5106460462365231.46836622715564.990347822
     2365637.826      715223.219
#Sta/Elev= 30
       0 2403.64    19.1 2392.74    27.6 2389.49      53 2372.44    57.3 2368.11
      70 2349.13    95.5 2328.82   112.5 2320.65   125.3  2319.3   176.2 2319.44
   197.5 2322.65   231.4 2321.49   269.7 2323.66   297.5 2319.09   320.7 2323.49
     400 2324.58   414.9 2323.43   436.5 2324.69   453.5 2321.88   529.9 2321.69
   540.4 2321.26   564.2 2324.91   648.6 2322.97   707.6 2328.25   766.6 2327.01
   811.2 2339.45     854 2347.02   869.6 2351.22   903.4 2364.63   918.8 2372.51
#Mann= 5 ,-1,0
       0      .1       0   453.5    .045       0   529.9      .1       0
  617.87     .06       0  747.87      .1       0
#XS Ineff= 2 , 0
                          691.92         2346.43
Permanent Ineff=
       F       F
Bank Sta=453.5,529.9
XS Rating Curve= 0 ,0
Exp/Cntr=0.3,0.1

Type RM Length L Ch R = 1 ,30359   ,149.6,160.1,171.9
XS GIS Cut Line= 4
2364857.86145058715739.8850430092365216.82488629715770.478517644
2365590.06527682715829.6259019362365861.90655431715844.903210384
#Sta/Elev= 30
       0 2401.04    50.5 2374.38    70.6 2358.56    78.6 2354.45   102.7 2333.46
   126.8 2318.23     187 2322.94   207.1  2320.1   239.2 2322.25   287.4 2321.52
   303.4 2317.06   315.5 2319.86   347.6 2322.07     397 2320.65   416.3 2321.84
   432.5  2318.2   449.5 2321.25   480.9 2322.86   497.3  2318.4   521.6 2320.68
   536.9 2319.65   596.9  2319.7   618.8 2327.49   695.7 2333.09   760.3 2332.72
   792.8 2347.58   828.4 2352.07   920.6 2356.62   963.5 2351.98  1010.4 2353.51
#Mann= 6 ,-1,0
       0      .1       0   536.9    .045       0   596.9      .1       0
  650.26     .06       0  748.16      .1       0  848.16     .06       0
Bank Sta=536.9,596.9
XS Rating Curve= 0 ,0
Exp/Cntr(USF)=0,0
Exp/Cntr=0.3,0.1

Type RM Length L Ch R = 1 ,30199   ,214.7,224.5,225.3
XS GIS Cut Line= 3
2364813.69362922715823.9872185932365216.50098008715855.887364141
2365779.56846375716224.921384063
#Sta/Elev= 30
       0 2405.32    34.6 2396.92   102.8 2370.55   118.9 2362.04   138.9  2347.7
     151  2340.7     171 2324.33   195.1 2316.33   219.2 2318.78   243.2 2316.86
   256.2 2319.79   283.4  2320.6   395.7 2321.06   416.3 2318.25   450.2 2321.77
   489.8 2317.98   561.5  2317.9   581.6 2326.03   644.6 2327.18     659 2329.06
   720.2 2328.17   762.4  2333.1   800.5 2330.15   812.1 2333.66   862.8 2337.87
     888 2347.91   916.1 2353.38   948.9 2362.17  1015.8 2391.99  1077.3 2424.31
#Mann= 5 ,-1,0
       0      .1       0   489.8    .045       0   561.5      .1       0
  594.07     .06       0  754.07      .1       0
Bank Sta=489.8,561.5
XS Rating Curve= 0 ,0
Exp/Cntr=0.3,0.1

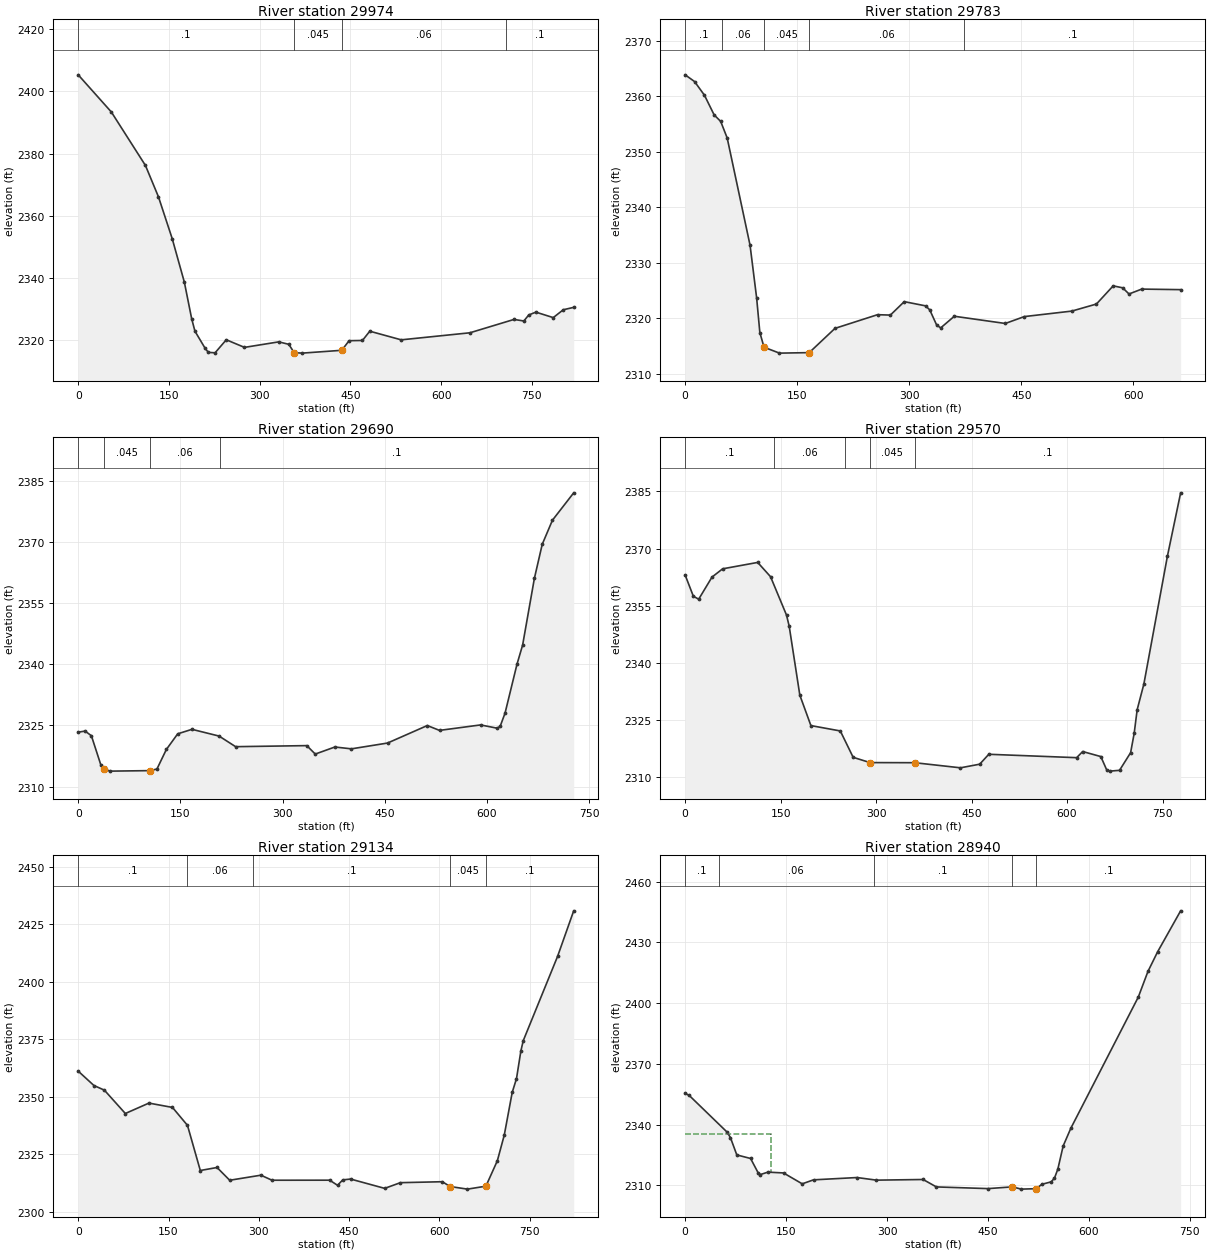
Type RM Length L Ch R = 1 ,29974   ,228.1,190.7,169
XS GIS Cut Line= 4
2364793.68421182715873.3589975212364980.42900793715893.805508045
2365203.97752299716107.8123181932365521.57998646716159.610144852
#Sta/Elev= 30
       0 2405.34    54.8 2393.37   111.2 2376.14   132.7 2366.04   155.4 2352.59
   175.5 2338.56   187.6 2326.78     193 2322.78   209.9 2317.24   215.2 2315.95
   226.3 2315.82   244.8 2320.01   274.9 2317.56   331.6 2319.34   348.1 2318.55
     357 2315.87   370.2 2315.71   435.7 2316.62   447.8 2319.71   469.9 2319.79
     482 2322.77     534 2319.99   647.5 2322.26   720.4 2326.56   736.7 2326.06
   744.8    2328   756.6 2328.91   785.3 2327.15   801.9 2329.68   819.1 2330.45
#Mann= 4 ,-1,0
       0      .1       0     357    .045       0   435.7     .06       0
  707.33      .1       0
Bank Sta=357,435.7
XS Rating Curve= 0 ,0
Exp/Cntr(USF)=0,0
Exp/Cntr=0.3,0.1

Type RM Length L Ch R = 1 ,29783   ,100,93.8,91.7
XS GIS Cut Line= 4
2364872.65515941716223.849379799 2365113.8728936716117.327988107
2365233.69983898716162.8665481292365489.25685783716253.916449785
#Sta/Elev= 30
       0 2363.86    12.6 2362.65    25.9 2360.18    38.8 2356.65    47.6 2355.47
    56.3 2352.48    86.9 2333.17    95.7 2323.69     100 2317.46   105.6 2314.81
   126.3 2313.75   166.1 2313.84   200.6 2318.21   257.5 2320.67   274.7  2320.6
   293.3 2323.02   321.8 2322.26   327.4 2321.54   336.7 2318.79   342.1  2318.3
   360.3 2320.39   428.5 2319.09     454 2320.33   517.6 2321.32   550.5 2322.59
   572.9 2325.86   585.6 2325.51   594.1  2324.4   611.1 2325.28   663.2 2325.18
#Mann= 5 ,-1,0
       0      .1       0      50     .06       0   105.6    .045       0
   166.1     .06       0  373.69      .1       0
Bank Sta=105.6,166.1
XS Rating Curve= 0 ,0
Exp/Cntr(USF)=0,0
Exp/Cntr=0.3,0.1

Type RM Length L Ch R = 1 ,29690   ,80.7,119.1,142
XS GIS Cut Line= 4
2364927.28593454 716299.163421142365047.22687192 716232.05784232
2365141.27489072716177.3304539732365609.06765048716289.834504294
#Sta/Elev= 30
       0 2323.35    10.2 2323.61    19.4 2322.46    33.1  2315.4    37.7 2314.28
    46.9  2313.8     105 2313.92   115.6 2314.31   129.4  2319.1   146.1 2322.94
     167 2324.04   206.8 2322.39   231.1 2319.79   335.6 2320.05     348 2317.98
   376.8 2319.71   401.1 2319.26   454.1 2320.68   512.5 2324.97   530.4 2323.78
   590.7 2325.12   615.4 2324.31   619.5  2324.8   626.6    2328   644.2 2340.02
   652.4 2344.67   669.7 2361.04   681.2 2369.37   696.2 2375.28   727.4 2381.99
#Mann= 4 ,-1,0
       0      .1       0    37.7    .045       0     105     .06       0
  207.44      .1       0
Bank Sta=37.7,105
XS Rating Curve= 0 ,0
Exp/Cntr(USF)=0,0
Exp/Cntr=0.3,0.1

Type RM Length L Ch R = 1 ,29570   ,433.5,436,423.6
XS GIS Cut Line= 5
2364683.79039567716255.3508348692364866.09125878716310.878379013
2364950.04304769716359.4491395632365029.10924007716393.175461362
2365369.56120051716612.511205416
#Sta/Elev= 30
       0 2363.08    12.9  2357.5    21.3 2356.72    42.2 2362.52    58.9 2364.69
     114 2366.37   134.2 2362.62   159.3 2352.54   163.5 2349.62   180.2 2331.54
   197.6 2323.56   243.8 2322.15     264 2315.23   290.5 2313.85   360.6 2313.82
   432.6 2312.48   462.8 2313.43   477.1 2316.03   615.1 2315.14   624.6 2316.75
   653.1 2315.43   662.2 2311.98   667.4 2311.61   682.5 2311.82   699.9 2316.45
   705.5 2321.51   710.2 2327.72   720.7 2334.44   757.7    2368   778.5 2384.63
#Mann= 5 ,-1,0
       0      .1       0     140     .06       0  250.57      .1       0
   290.5    .045       0   360.6      .1       0
Bank Sta=290.5,360.6
XS Rating Curve= 0 ,0
Exp/Cntr(USF)=0,0
Exp/Cntr=0.3,0.1

Type RM Length L Ch R = 1 ,29134   ,185.8,194.7,204.8
XS GIS Cut Line= 2
2364548.17930018716458.9394991132365304.77640142716782.524929205
#Sta/Elev= 30
       0 2361.11    26.1 2354.85    43.5 2352.83    78.3 2342.67   117.5  2347.2
   156.6 2345.31   181.5 2337.51   202.8 2317.88   230.6 2319.19   251.6 2313.64
   303.4 2315.84   321.9 2313.65   417.6 2313.67   430.7 2311.45   439.4  2313.8
   452.4 2314.16     509 2310.11   535.1 2312.59   604.7    2313   617.8  2310.9
   646.5 2309.78   677.1 2311.06   696.1 2322.12   707.6 2333.28   720.8 2351.87
   727.9 2357.84   735.2 2369.91   739.1 2374.33   796.1 2410.99   822.9 2430.82
#Mann= 5 ,-1,0
       0      .1       0     180     .06       0     290      .1       0
   617.8    .045       0   677.1      .1       0
Bank Sta=617.8,677.1
XS Rating Curve= 0 ,0
Exp/Cntr=0.3,0.1

Type RM Length L Ch R = 1 ,28940   ,513.4,509.8,496.8
XS GIS Cut Line= 3
 2364574.1094754716582.1412089582364927.18719759716789.382480676
2365191.99548923716981.272547082
#Sta/Elev= 30
       0 2355.42       6 2354.39    62.2 2336.29    67.3 2333.55    76.8 2324.96
    97.3  2323.2   108.9 2315.86   111.9 2315.26     123 2316.45   146.2 2316.05
     174 2310.67   190.8 2312.64   255.5 2313.78   284.3 2312.49   353.7 2312.81
   373.4 2309.14   450.1 2308.31   486.5 2309.17   499.5 2308.05   521.7 2308.27
   530.3 2310.46     544 2311.64   548.9  2313.5   553.9 2317.94   561.8 2329.37
   573.2 2338.14   673.5 2403.01   687.8 2415.66   702.1 2425.33   736.4 2445.64
#Mann= 5 ,-1,0
       0      .1       0      50     .06       0     280      .1       0
   486.5    .045       0   521.7      .1       0
#XS Ineff= 2 , 0
          127.08 2335.38
Permanent Ineff=
       F       F
Bank Sta=486.5,521.7
XS Rating Curve= 0 ,0
Exp/Cntr(USF)=0,0
Exp/Cntr=0.3,0.1

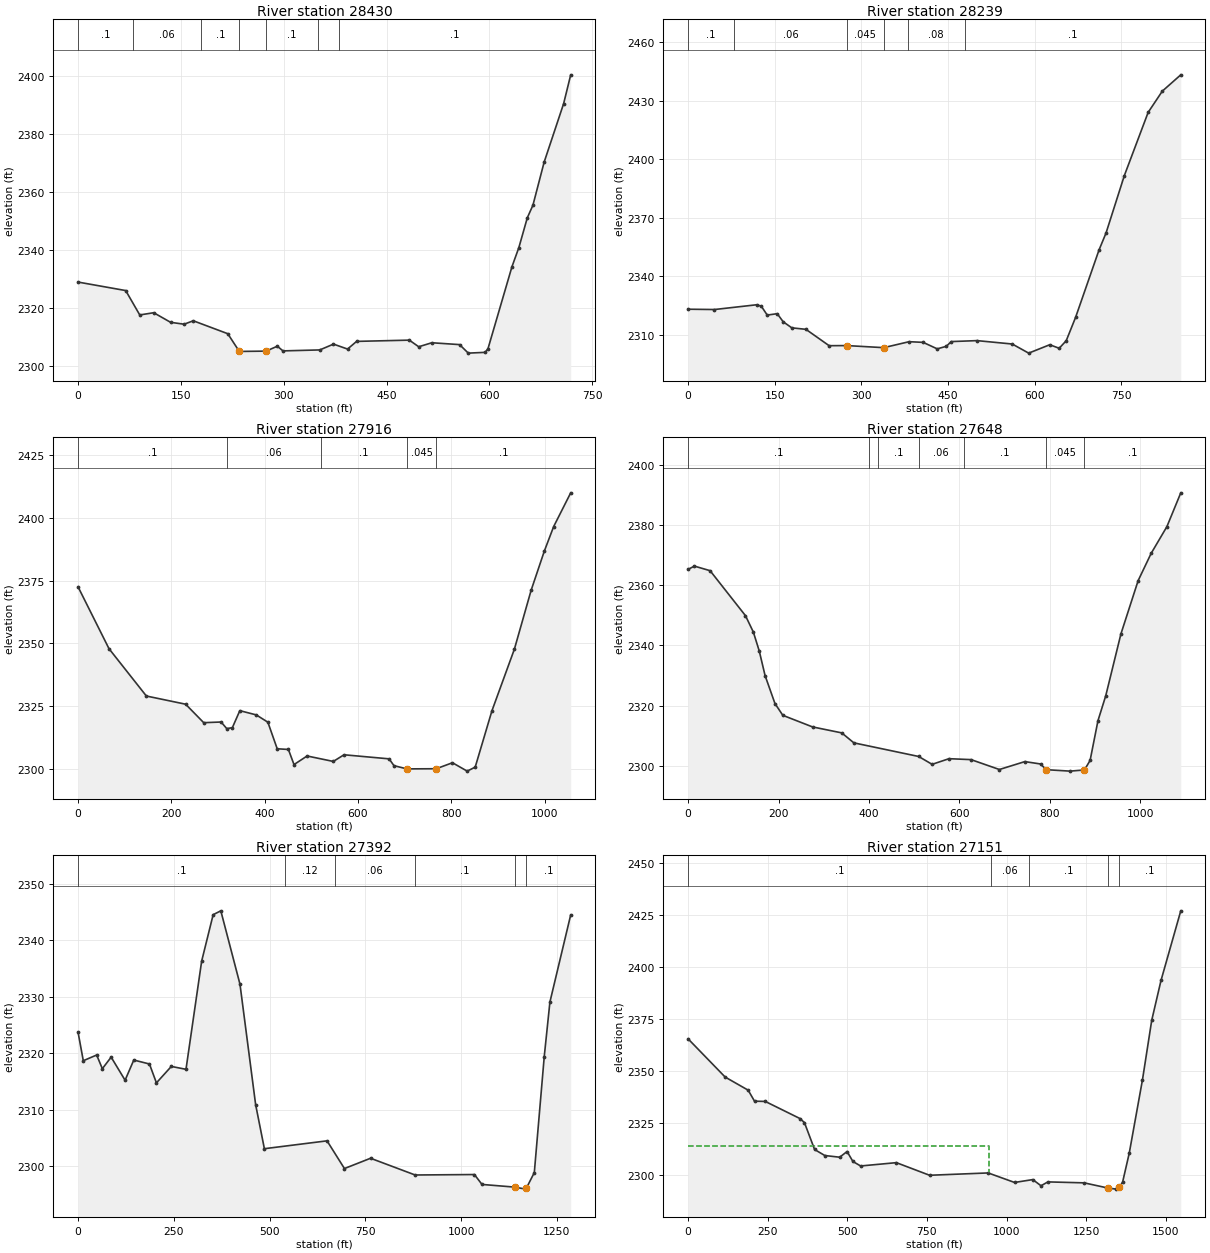
Type RM Length L Ch R = 1 ,28430   ,192.6,191,190.1
XS GIS Cut Line= 2
 2364344.3327577717064.6464424272365046.01365155717219.666522951
#Sta/Elev= 30
       0 2328.93    69.5 2326.01      90 2317.62   110.4 2318.38     135 2315.08
   154.7 2314.43   168.1 2315.61   218.4 2311.16   235.2 2305.06   274.3 2305.17
   290.7 2306.86   298.9 2305.25   352.6 2305.58   372.6 2307.58   393.1 2305.88
   406.3 2308.52   483.2 2308.95   496.9 2306.67     516 2308.05   556.5 2307.41
   569.2 2304.48   593.8 2304.75   597.9 2305.98   632.9 2334.21     643 2340.82
   655.3 2351.05   663.5 2355.38   679.8 2370.16   708.3 2390.35   718.6 2400.24
#Mann= 7 ,-1,0
       0      .1       0      80     .06       0     180      .1       0
   235.2    .045       0   274.3      .1       0     350     .08       0
     380      .1       0
Bank Sta=235.2,274.3
XS Rating Curve= 0 ,0
Exp/Cntr(USF)=0,0
Exp/Cntr=0.3,0.1

Type RM Length L Ch R = 1 ,28239   ,345.1,323.2,296.9
XS GIS Cut Line= 3
2364247.26279239717251.4275748262364699.88621036717330.816741409
2365087.67480865 717398.76133353
#Sta/Elev= 30
       0 2323.13    45.6 2322.97   118.7 2325.41   126.8 2324.65     137 2320.12
   154.3 2320.84   164.7 2316.67   179.6 2313.58     204 2312.82   244.2 2304.43
   274.8 2304.49   338.8 2303.42   382.7 2306.48     407 2306.14   431.4 2302.81
   447.1 2304.11   455.8 2306.54   500.4 2307.03   561.3 2305.29   589.8 2300.62
   626.3 2304.92   642.6 2303.11   654.8 2306.97     671 2318.93   711.6 2353.49
   723.8 2362.24   755.5 2391.66   796.7 2424.04   821.2 2434.91   853.2 2443.28
#Mann= 6 ,-1,0
       0      .1       0      80     .06       0   274.8    .045       0
   338.8      .1       0     380     .08       0  479.53      .1       0
Bank Sta=274.8,338.8
XS Rating Curve= 0 ,0
Exp/Cntr=0.3,0.1

Type RM Length L Ch R = 1 ,27916   ,257.3,267.7,272.5
XS GIS Cut Line= 4
2364001.95967136717621.9529119712364667.64302614717587.137291701
2364793.04497295717499.2213582122365028.62160368717515.014779315
#Sta/Elev= 30
       0 2372.48    66.3 2347.86   146.4 2329.01   230.5 2325.75   269.3 2318.39
   306.6 2318.66   318.7 2316.03   330.7 2316.41   346.7 2323.18   381.9 2321.49
   406.8 2318.58   426.8    2308   450.8 2307.73   462.8 2301.71   490.9 2305.13
     547 2302.96     570 2305.61   666.6 2303.99     677 2301.28   704.8 2299.99
   767.6 2300.05   802.4 2302.44   833.9  2299.1   851.1 2300.69     887 2323.14
   935.1 2347.67     971 2371.13   999.3 2386.74  1019.3  2396.5  1055.8 2409.92
#Mann= 5 ,-1,0
       0      .1       0     320     .06       0     520      .1       0
   704.8    .045       0   767.6      .1       0
Bank Sta=704.8,767.6
XS Rating Curve= 0 ,0
Exp/Cntr(USF)=0,0
Exp/Cntr=0.3,0.1

Type RM Length L Ch R = 1 ,27648   ,269,256.3,251.2
XS GIS Cut Line= 3
2364055.42892725718089.3820938012364640.81976008 717840.31476244
2365069.20852192 717690.66476244
#Sta/Elev= 30
       0 2365.33    13.9 2366.41    48.6 2364.89   126.9 2349.91   144.3 2344.46
   157.3 2338.19   170.3 2329.95   192.1 2320.67   209.5 2316.74   275.2 2312.88
   339.9 2310.89   366.7 2307.57     510 2303.04   539.8 2300.42   577.1  2302.3
   625.9 2301.99   688.6  2298.7   744.9 2301.33   779.6 2300.54   792.3 2298.64
   844.9 2298.16   876.8 2298.55   889.3 2301.73   906.7 2314.96   923.9 2323.25
   957.5 2343.85   995.6 2361.59  1024.4 2370.67  1059.2 2379.56  1089.9 2390.81
#Mann= 7 ,-1,0
       0      .1       0     400     .12       0     420      .1       0
     510     .06       0     610      .1       0   792.3    .045       0
   876.8      .1       0
Bank Sta=792.3,876.8
XS Rating Curve= 0 ,0
Exp/Cntr=0.3,0.1

Type RM Length L Ch R = 1 ,27392   ,236,240.5,243.6
XS GIS Cut Line= 2
2363944.14002125718539.0273399852365076.00186699717928.348390655
#Sta/Elev= 30
       0 2323.72    13.7 2318.67    48.6 2319.68    63.4 2317.26    86.4  2319.3
   122.8 2315.22   145.5 2318.79   186.4 2318.09   204.6 2314.75   243.5 2317.66
   281.8 2317.15   322.7 2336.29   352.7  2344.5   372.7 2345.18   422.7 2332.21
   463.6  2310.9   486.4 2303.11     650  2304.5   695.4  2299.6   763.6 2301.42
     880 2298.46  1034.7 2298.54  1054.5 2296.79    1141 2296.31  1168.1 2295.96
  1170.5 2296.15  1191.1 2298.89    1217 2319.39  1231.8 2329.05  1286.1 2344.47
#Mann= 6 ,-1,0
       0      .1       0     540     .12       0     670     .06       0
     880      .1       0    1141    .045       0  1170.5      .1       0
Bank Sta=1141,1170.5
XS Rating Curve= 0 ,0
Exp/Cntr(USF)=0,0
Exp/Cntr=0.3,0.1

Type RM Length L Ch R = 1 ,27151   ,296.5,288.2,282
XS GIS Cut Line= 3
2363891.43865997718823.2250521222364872.73776008718258.846667061
2365271.76609301718143.858809833
#Sta/Elev= 30
       0 2365.47   116.3  2347.1   188.6 2340.78   208.5 2335.49   242.3 2335.37
   351.5 2327.12   365.4 2325.16   397.2 2312.24   429.3 2309.34   476.1 2308.53
   499.2 2311.27   517.6 2306.47   541.7 2304.31     654 2305.91   758.3 2299.84
   942.4 2300.96  1025.2 2296.38  1082.5 2297.76  1108.3 2294.79  1129.9 2296.65
  1243.8 2296.19  1318.8 2293.69  1345.1 2293.17  1354.7 2294.08  1364.6 2296.55
  1385.4 2310.44    1427 2345.79  1456.1 2374.45  1485.3 2393.64  1547.3 2427.09
#Mann= 5 ,-1,0
       0      .1       0     950     .06       0    1070      .1       0
  1318.8    .045       0  1354.7      .1       0
#XS Ineff= 2 , 0
           943.4 2313.81
Permanent Ineff=
       F       F
Bank Sta=1318.8,1354.7
XS Rating Curve= 0 ,0
Exp/Cntr=0.3,0.1

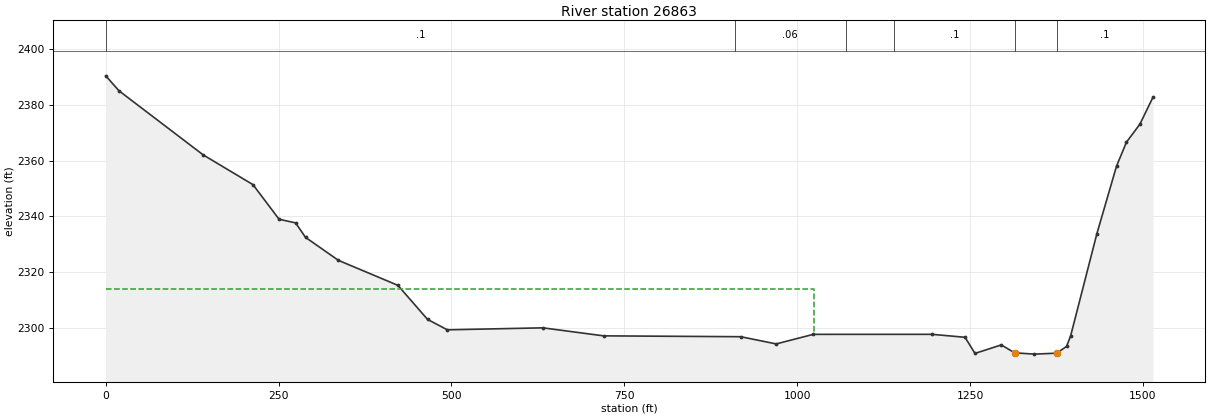
Type RM Length L Ch R = 1 ,26863   ,213.1,209.5,206.9
XS GIS Cut Line= 2
 2364053.8959972719193.3709607452365324.20823681718368.243675201
#Sta/Elev= 30
       0 2390.51    19.1 2385.13     141 2362.07   212.9 2351.39   250.7 2338.94
   274.6 2337.64   288.9 2332.44   336.6 2324.16   422.5 2315.19   465.4 2302.95
     494  2299.2   632.3 2299.91     720 2297.03   918.4 2296.72   969.7 2294.13
  1023.4 2297.57  1195.2 2297.58  1242.9 2296.51  1257.2 2290.71  1295.3 2293.77
  1314.6 2290.93    1343 2290.46  1375.3  2290.8  1389.7 2293.22  1395.6 2297.02
  1433.6  2333.8    1462 2358.06  1476.3 2366.65  1495.7  2373.1  1514.8 2382.87
#Mann= 6 ,-1,0
       0      .1       0     910     .06       0    1070     .08       0
    1140      .1       0  1314.6    .045       0  1375.3      .1       0
#XS Ineff= 2 , 0
         1024.06 2313.92
Permanent Ineff=
       F       F
Bank Sta=1314.6,1375.3
XS Rating Curve= 0 ,0
Exp/Cntr(USF)=0,0
Exp/Cntr=0.3,0.1