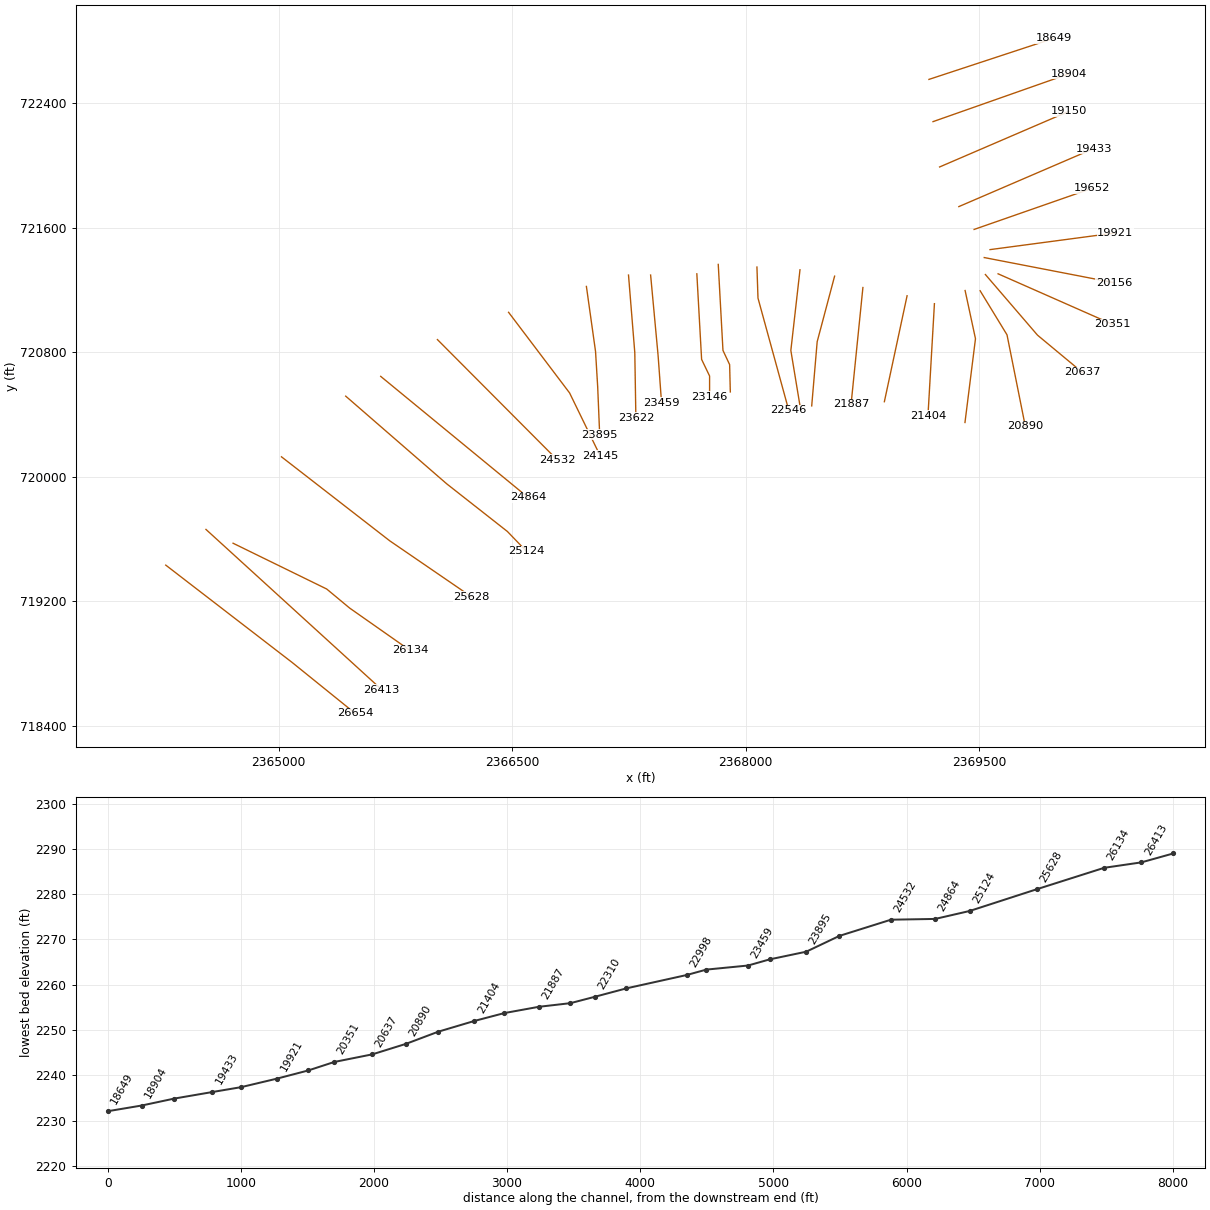
HEC-RAS study GLADYFK.prj: GLADYFK

--- GLADYFK.g01 (geometry) --- (continued)

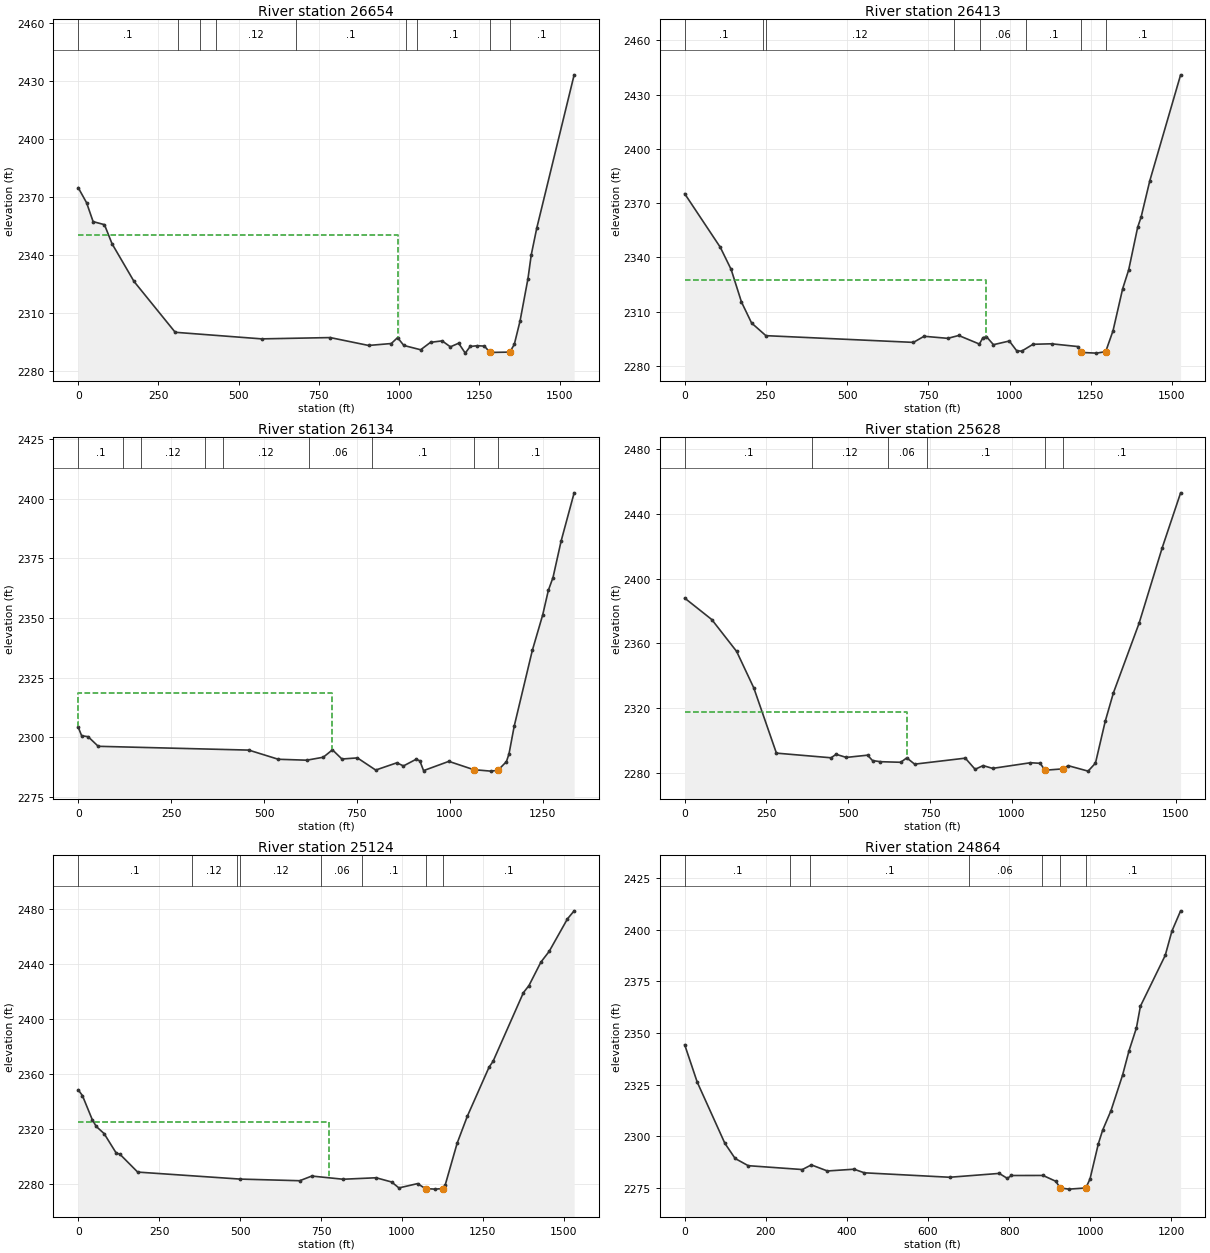
Type RM Length L Ch R = 1 ,26654   ,244.1,240.8,239.6
XS GIS Cut Line= 3
2364275.38023165719432.2639093492365087.37609301718806.920287319
2365492.14185545718480.005096561
#Sta/Elev= 30
       0 2374.65    26.2  2366.8    46.4 2357.08    81.8 2355.49   105.4 2345.62
   173.9  2326.1   302.2 2299.79   571.5 2296.38   785.2 2297.05   904.7 2292.97
   975.4 2293.97     995 2297.01  1014.6 2292.97    1067 2290.74  1097.7 2294.59
  1133.9 2295.34  1159.6 2292.25  1185.3 2294.14  1205.9    2289  1221.3 2292.45
  1242.9 2292.83  1265.6 2292.65    1283 2289.35  1344.7 2289.53  1358.7 2293.51
  1376.6 2305.61  1401.3 2327.55  1411.5 2339.85  1428.7 2353.71  1545.2 2433.06
#Mann= 9 ,-1,0
       0      .1       0     310     .08       0     380      .1       0
     430     .12       0     680      .1       0    1020     .06       0
 1054.89      .1       0    1283    .045       0  1344.7      .1       0
#XS Ineff= 2 , 0
          994.91 2350.35
Permanent Ineff=
       F       F
Bank Sta=1283,1344.7
XS Rating Curve= 0 ,0
Exp/Cntr=0.3,0.1

Type RM Length L Ch R = 1 ,26413   ,274.7,279.3,283
XS GIS Cut Line= 2
2364533.62116321719661.5827227762365661.93475368718633.051966841
#Sta/Elev= 30
       0 2375.17   109.7 2345.53   143.1 2333.27   174.8  2315.3     206 2303.67
     250 2296.68   704.3 2292.96   736.9 2296.33   809.9  2295.2   843.7 2296.77
   907.3 2292.04   918.2 2295.56     929 2296.12   950.6 2291.69   999.4 2293.72
  1021.9 2288.39  1037.2 2288.09  1072.4 2291.91  1129.3 2292.18  1210.4 2290.66
  1221.3  2287.4  1267.8 2287.02  1296.1 2287.83  1318.7 2299.39  1348.4 2322.65
  1366.9 2333.04  1394.5 2356.55  1405.3 2362.34    1432 2382.38  1526.8  2440.9
#Mann= 8 ,-1,0
       0      .1       0     240     .08       0     250     .12       0
     830      .1       0     910     .06       0    1050      .1       0
  1221.3    .045       0  1296.1      .1       0
#XS Ineff= 2 , 0
          926.17 2327.26
Permanent Ineff=
       F       F
Bank Sta=1221.3,1296.1
XS Rating Curve= 0 ,0
Exp/Cntr(USF)=0,0
Exp/Cntr=0.3,0.1

Type RM Length L Ch R = 1 ,26134   ,504.5,505.1,505.7
XS GIS Cut Line= 4
2364707.78458423719572.8423524982365309.19915984719278.793406461
2365456.50594676719156.4587635992365844.17499942718884.534658275
#Sta/Elev= 30
       0 2304.22     9.3 2300.63    26.6 2300.25    53.9 2296.22     459 2294.63
   538.3 2290.79   614.9  2290.4   659.4 2291.64   684.1 2294.74   709.6  2290.9
   751.3 2291.36   800.5 2286.27   857.3  2289.3   875.2    2288     909 2290.76
   919.2 2290.15   929.3 2286.03   997.3 2289.91  1064.1 2286.44    1110 2285.82
  1129.3 2286.16  1152.2 2289.78  1159.2 2293.05  1173.1  2304.6    1222 2336.43
  1249.8 2351.22  1265.1 2361.57  1277.6 2366.93  1299.5 2382.25  1334.5 2402.41
#Mann= 9 ,-1,0
       0      .1       0     120     .08       0     170     .12       0
     340      .1       0     390     .12       0     620     .06       0
  789.45      .1       0  1064.1    .045       0  1129.3      .1       0
#XS Ineff= 2 , 0
          683.78 2318.52
Permanent Ineff=
       F       F
Bank Sta=1064.1,1129.3
XS Rating Curve= 0 ,0
Exp/Cntr=0.3,0.1

Type RM Length L Ch R = 1 ,25628   ,506.9,504.7,503.2
XS GIS Cut Line= 3
2365018.70320892720127.975527775 2365713.7328941719588.657816261
2366238.19363137719229.385105324
#Sta/Elev= 30
       0    2388    82.9 2374.72   158.8 2355.04   211.2  2332.5   280.3 2292.22
   447.4 2289.34   462.6 2291.49   493.9 2289.57   558.8 2290.96     574 2287.62
   598.3 2286.92   660.1 2286.57   678.7 2289.29   702.7 2285.41   857.5 2289.12
   887.5 2282.22   911.8 2284.52   940.9  2282.8  1056.6 2286.28  1086.3 2285.94
  1100.9 2281.66  1154.8 2282.48  1171.7 2284.48  1232.7  2281.1  1255.2 2286.04
  1285.1 2311.93  1309.8 2329.31  1388.4  2372.4  1459.2 2419.11  1515.4 2453.02
#Mann= 6 ,-1,0
       0      .1       0     390     .12       0     620     .06       0
     740      .1       0  1100.9    .045       0  1154.8      .1       0
#XS Ineff= 2 , 0
          679.25 2317.76
Permanent Ineff=
       F       F
Bank Sta=1100.9,1154.8
XS Rating Curve= 0 ,0
Exp/Cntr=0.3,0.1

Type RM Length L Ch R = 1 ,25124   ,265.1,259.8,262.1
XS GIS Cut Line= 4
2365431.32275771720517.6193370762366078.89318898719955.409477485
2366470.00935423 719648.18220049     2366592.794      719520.653
#Sta/Elev= 30
       0 2348.46    12.9 2344.34    43.4  2326.8    55.6 2321.87      80 2316.67
   117.7 2302.38   128.3 2301.79   183.7 2288.68     500 2283.59   684.3  2282.4
   721.5  2285.8   818.3 2283.48   920.2 2284.55   968.3 2281.47   990.7 2277.16
  1048.1  2280.3  1072.8 2276.65  1103.4 2276.29  1126.7 2276.73  1133.9 2279.48
  1170.6 2309.71  1201.9 2329.22  1269.1 2364.93  1281.4 2369.16  1375.3 2419.13
  1392.4 2424.27  1429.3 2441.32  1454.8  2449.1  1511.3 2472.74    1532 2478.59
#Mann= 8 ,-1,0
       0      .1       0     350     .12       0     490      .1       0
     500     .12       0     750     .06       0  877.57      .1       0
  1072.8    .045       0  1126.7      .1       0
#XS Ineff= 2 , 0
          775.13 2325.38
Permanent Ineff=
       F       F
Bank Sta=1072.8,1126.7
XS Rating Curve= 0 ,0
Exp/Cntr=0.3,0.1

Type RM Length L Ch R = 1 ,24864   ,334,331.7,329.4
XS GIS Cut Line= 2
2365656.06645423 720644.59891142 2366600.8052145719868.339629453
#Sta/Elev= 30
       0 2344.35    30.9 2326.28    99.1 2296.68   124.4 2289.35   156.6 2285.87
   290.1    2284   312.3 2286.25   351.9 2283.31   417.4 2284.16     443 2282.42
   653.3 2280.27   775.5 2282.13   795.4 2279.73   805.6 2281.12   883.5 2281.14
   914.8 2278.34   926.1 2275.08   947.5 2274.53     989 2275.09   999.3 2279.44
  1019.9 2296.48  1030.4    2303  1051.1 2312.52  1079.6 2329.67  1095.4 2341.37
  1113.7 2352.47  1123.6 2362.99  1184.8 2387.58  1201.2 2399.28  1222.7  2409.1
#Mann= 7 ,-1,0
       0      .1       0     260     .08       0     310      .1       0
     700     .06       0     880      .1       0   926.1    .045       0
     989      .1       0
Bank Sta=926.1,989
XS Rating Curve= 0 ,0
Exp/Cntr(USF)=0,0
Exp/Cntr=0.3,0.1

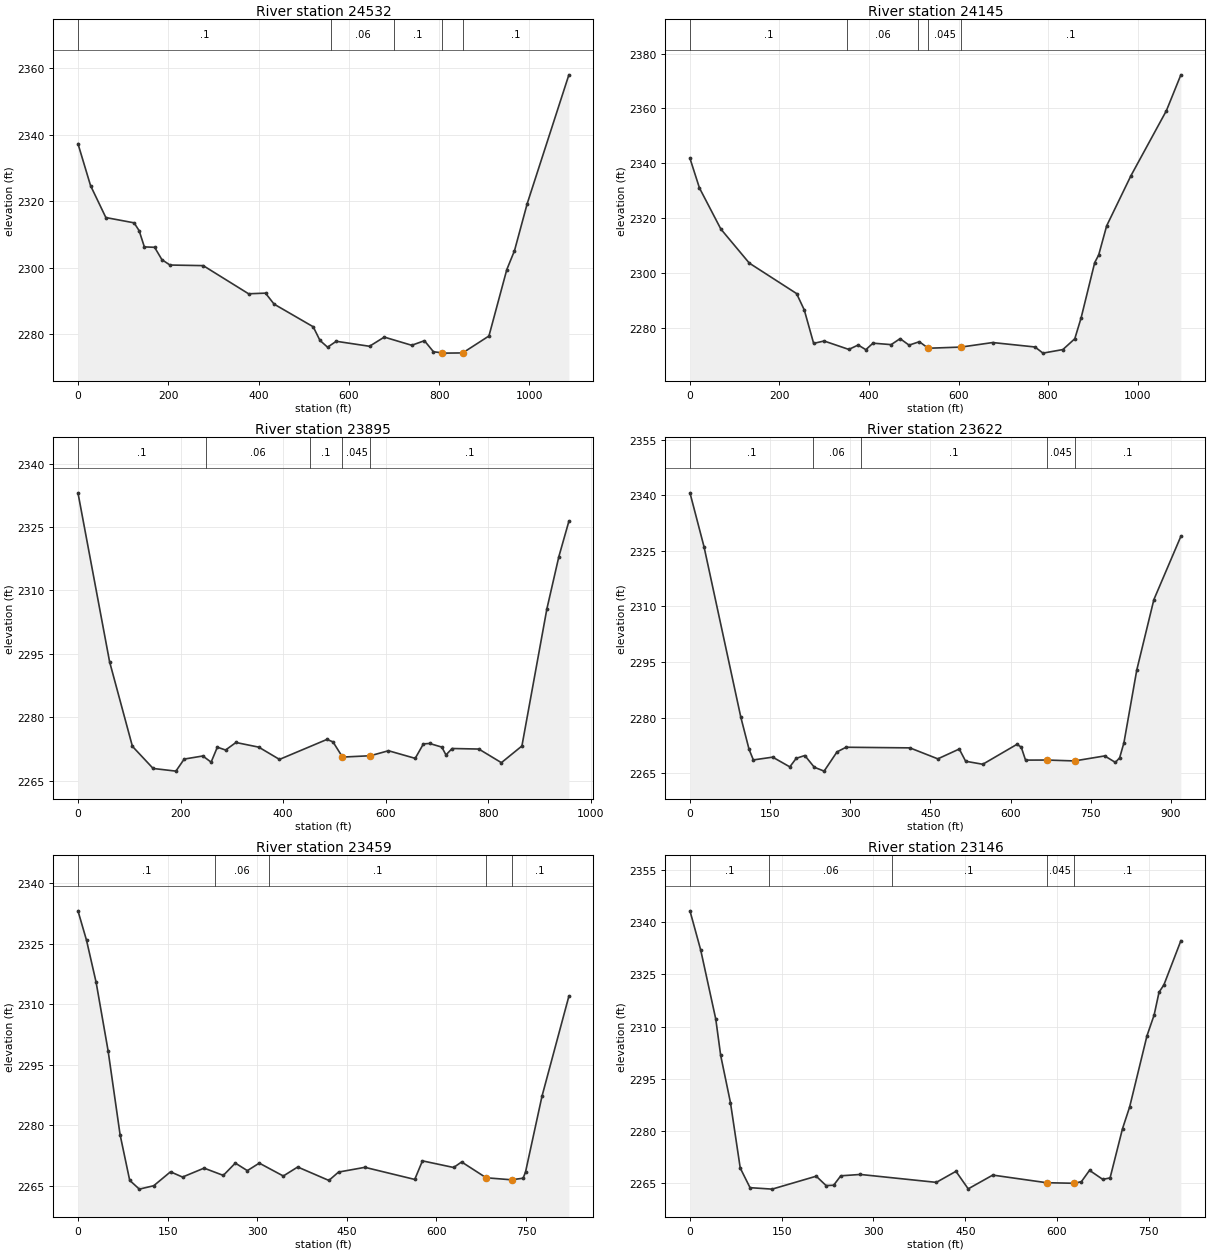
Type RM Length L Ch R = 1 ,24532   ,387.7,387.5,371.6
XS GIS Cut Line= 2
2366020.34534212720880.9800289512366787.92013948720110.459801755
#Sta/Elev= 30
       0 2337.31    27.9 2324.71    61.8 2315.11   124.4 2313.52   135.5 2311.17
   147.1 2306.29   169.8 2306.17     186 2302.45   203.8 2300.84   277.5 2300.66
     378  2292.2   415.5 2292.39   434.5 2289.09   521.2 2282.28   536.1 2278.19
     553 2276.14   572.2 2277.92   645.9 2276.42   678.6 2279.18   739.4 2276.72
   767.6 2278.09   787.6 2274.77   807.1 2274.45   811.5 2274.36   852.3 2274.42
   910.5 2279.51   950.1 2299.48   967.1 2305.15   995.3  2319.3  1087.6 2358.01
#Mann= 5 ,-1,0
       0      .1       0     560     .06       0     700      .1       0
   807.1    .045       0   852.3      .1       0
Bank Sta=807.1,852.3
XS Rating Curve= 0 ,0
Exp/Cntr(USF)=0,0
Exp/Cntr=0.3,0.1

Type RM Length L Ch R = 1 ,24145   ,260.9,249.2,222.8
XS GIS Cut Line= 3
2366477.43519714721056.1814739582366869.31868437720538.244526042
     2367065.014      720136.074
#Sta/Elev= 30
       0 2341.81    21.2 2331.01      69 2316.03   132.6  2303.6   238.2  2292.5
   255.4 2286.53   276.3 2274.34   299.7  2275.2   354.9 2272.13   375.8 2273.74
   392.9 2272.04   408.9 2274.41   449.5 2273.88   469.5 2276.06   489.5 2273.69
   512.4 2274.94   532.4 2272.56   605.7 2272.99   676.4 2274.64   770.8 2273.02
   788.6 2270.78   833.1 2272.08   859.7 2276.02   873.9 2283.67   904.2 2303.79
   913.1 2306.57   930.9 2317.19   985.1 2335.46  1064.4  2359.2  1096.7 2372.26
#Mann= 5 ,-1,0
       0      .1       0     350     .06       0     510      .1       0
   532.4    .045       0   605.7      .1       0
Bank Sta=532.4,605.7
XS Rating Curve= 0 ,0
Exp/Cntr=0.3,0.1

Type RM Length L Ch R = 1 ,23895   ,265.3,273.8,262.3
XS GIS Cut Line= 4
2366977.29352479721222.3159380122367036.01188511720804.379373381
2367049.82796989 720576.413974492367062.60699515720269.681388379
#Sta/Elev= 30
       0 2333.09    61.7 2293.14   106.2 2273.15   146.6 2267.92     191 2267.29
   207.2 2270.14   243.5 2270.87   259.7 2269.41   271.8 2272.95   287.9 2272.28
   308.1 2274.06   352.6 2272.96     393 2270.06   485.7 2274.79   497.4  2274.2
   515.9 2270.61   570.3 2270.93   605.6 2272.11   657.7 2270.31   673.7 2273.73
   685.7 2273.83   709.6 2272.97   717.7 2271.12   729.7 2272.64   781.8 2272.51
   825.8 2269.29   865.8 2273.23   914.5 2305.65   937.9 2318.03   957.4 2326.37
#Mann= 5 ,-1,0
       0      .1       0     250     .06       0  452.04      .1       0
   515.9    .045       0   570.3      .1       0
Bank Sta=515.9,570.3
XS Rating Curve= 0 ,0
Exp/Cntr(USF)=0,0
Exp/Cntr=0.3,0.1

Type RM Length L Ch R = 1 ,23622   ,161.7,163,163.8
XS GIS Cut Line= 3
2367247.74773646721295.375303384 2367288.1714474720796.357961197
2367295.09114505720378.663303384
#Sta/Elev= 30
       0 2340.64    26.3 2326.12    95.2 2280.12   110.6 2271.47   118.6 2268.62
   154.8 2269.37   186.8 2266.75   198.8 2269.05   214.9 2269.81   232.6 2266.65
     251  2265.6   275.1 2270.78     292 2272.04   411.5 2271.87   463.7 2268.91
   503.8 2271.56   515.8 2268.26   547.8 2267.45   611.8 2272.83   619.8 2272.06
   627.8 2268.57   667.9 2268.59   719.5 2268.35   775.9  2269.7   795.9 2267.95
   803.9 2269.21   811.9 2273.27   835.9 2292.86   867.9 2311.85   918.4 2328.91
#Mann= 5 ,-1,0
       0      .1       0     230     .06       0     320      .1       0
   667.9    .045       0   719.5      .1       0
Bank Sta=667.9,719.5
XS Rating Curve= 0 ,0
Exp/Cntr=0.3,0.1

Type RM Length L Ch R = 1 ,23459   ,303.2,312.9,319.3
XS GIS Cut Line= 3
2367389.78209897721295.4182151582367437.95751608720776.613895645
2367459.85136416720476.789351924
#Sta/Elev= 30
       0 2333.17    14.3 2325.89    30.4 2315.46    50.5 2298.46    70.5 2277.73
    86.6 2266.42   102.7 2264.24   126.8 2265.08   154.9 2268.53     175 2267.23
   211.1 2269.44   243.3 2267.64   263.4 2270.69   283.5 2268.82   303.5 2270.68
   343.7 2267.49   367.8 2269.72     420 2266.39   436.1 2268.46   480.3 2269.64
   563.7 2266.64   576.6 2271.24   628.8  2269.6   642.2 2270.97   683.3 2267.05
   725.7 2266.55   745.1 2266.95   749.1 2268.46   776.7 2287.25   821.7 2312.02
#Mann= 5 ,-1,0
       0      .1       0     230     .06       0     320      .1       0
   683.3    .045       0   725.7      .1       0
Bank Sta=683.3,725.7
XS Rating Curve= 0 ,0
Exp/Cntr(USF)=0,0
Exp/Cntr=0.3,0.1

Type RM Length L Ch R = 1 ,23146   ,148.5,148.2,148
XS GIS Cut Line= 4
2367686.67304457 721303.29500296 2367717.2989091 720753.61807318
2367768.57110554720646.9719427362367768.57091664720513.444586601
#Sta/Elev= 30
       0  2343.2    17.6 2331.93    42.2 2312.13    50.2 2301.73    66.2 2288.17
    82.2 2269.39    98.2 2263.76   134.3 2263.34   206.4 2267.05   222.5 2264.36
   234.9 2264.46   246.5 2267.16   278.5 2267.55   402.7 2265.28   434.8 2268.45
   454.8 2263.42   494.9 2267.37     583 2265.18   627.9 2265.02   639.8 2265.48
   653.1 2268.73   674.7 2266.14   686.7 2266.56     707 2280.68   718.7 2286.94
     747 2307.34   758.7 2313.31   766.7 2319.84   774.7 2321.97   802.4 2334.62
#Mann= 5 ,-1,0
       0      .1       0     130     .06       0     330      .1       0
     583    .045       0   627.9      .1       0
Bank Sta=583,627.9
XS Rating Curve= 0 ,0
Exp/Cntr=0.3,0.1

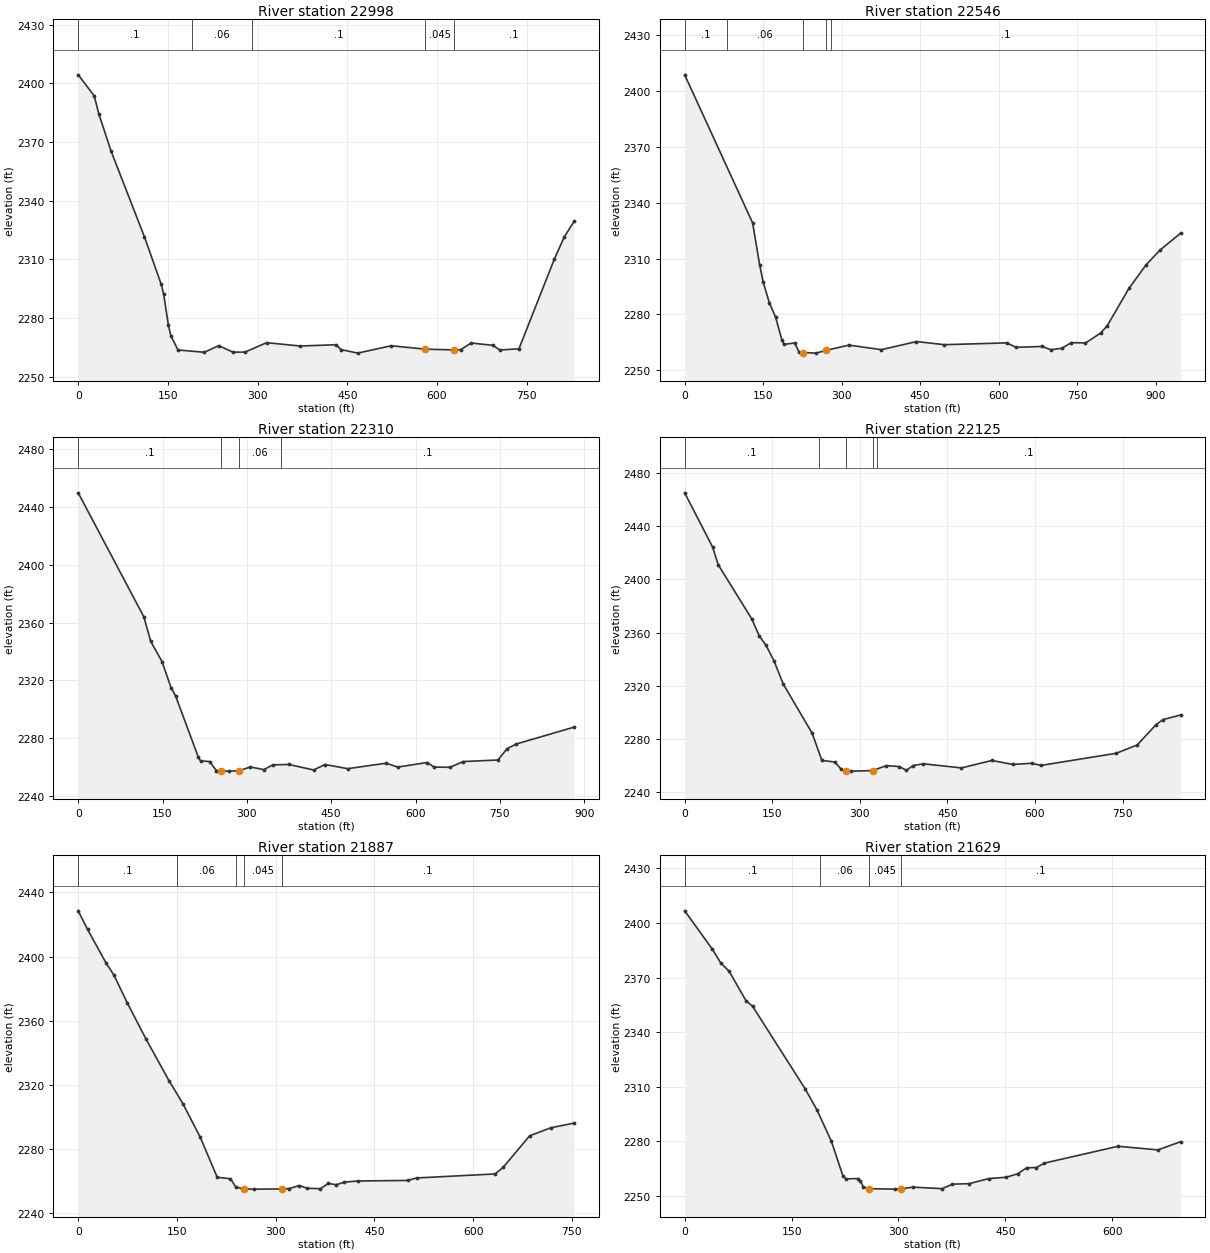
Type RM Length L Ch R = 1 ,22998   ,447.8,451.7,441.9
XS GIS Cut Line= 4
2367824.21010952721363.7974988472367854.46596032720811.622688294
2367897.26481521720719.998955978 2367901.6763828720544.868096242
#Sta/Elev= 30
       0 2404.37    26.7 2393.65    34.7 2384.21    54.7 2365.57   110.8 2321.52
   138.8 2297.31   142.8 2292.51   150.8  2276.5   154.9 2270.99   166.9 2263.75
   210.9 2262.57     235 2265.94     259 2262.62     279 2262.68   315.1 2267.49
   371.2 2265.77   431.3 2266.43   439.3 2263.99   467.3 2262.14   523.4 2265.91
   580.2 2264.17   628.3 2263.78   639.6 2263.89     657 2267.29     693 2266.16
     705 2263.74     737 2264.34   796.3 2310.28     813 2321.65   829.3 2329.54
#Mann= 5 ,-1,0
       0      .1       0     190     .06       0     290      .1       0
   580.2    .045       0   628.3      .1       0
Bank Sta=580.2,628.3
XS Rating Curve= 0 ,0
Exp/Cntr(USF)=0,0
Exp/Cntr=0.3,0.1

Type RM Length L Ch R = 1 ,22546   ,240.6,235.8,223.1
XS GIS Cut Line= 3
2368072.70329463721346.9024648242368079.44684943721147.224882168
2368277.36488379720425.902834688
#Sta/Elev= 30
       0 2408.83   129.8 2329.27   143.2 2306.83   149.8 2297.68   161.8 2286.28
   173.8  2278.5   185.8 2266.23   189.8 2263.88   210.2 2264.67   218.5 2259.77
   226.8 2259.52   250.9  2259.2   270.4 2260.68   313.9 2263.51   376.1 2261.05
   442.9 2265.42   496.4 2263.74   615.4 2264.71   633.3 2262.31   683.1 2262.78
   699.7 2261.06   720.4 2261.75     739 2264.84     766 2264.66   795.1 2270.01
   807.5 2273.92     849 2293.98   881.9  2306.7   908.3 2314.57   947.8 2323.71
#Mann= 5 ,-1,0
       0      .1       0      80     .06       0   226.8    .045       0
   270.4     .06       0  279.79      .1       0
Bank Sta=226.8,270.4
XS Rating Curve= 0 ,0
Exp/Cntr=0.3,0.1

Type RM Length L Ch R = 1 ,22310   ,188.5,184.8,184.9
XS GIS Cut Line= 3
2368349.22133121721329.2572868942368290.50297089720811.154107598
2368349.22133121720455.389924482
#Sta/Elev= 30
       0  2449.7   116.8 2363.91   128.9 2347.07     149 2333.09   165.1 2315.02
   173.2 2309.31   213.4 2267.21   217.5 2264.45   233.6 2263.98   245.6 2257.78
   253.1 2257.51   268.6 2257.35   285.9 2257.59     306 2260.21   330.2 2258.41
   346.3  2261.7   374.5 2261.95   418.7 2258.15   438.9 2261.93   479.1 2259.05
   547.7 2262.83     568 2260.15   620.7 2263.31   632.9 2260.16   661.3    2260
   684.7 2263.97   746.4 2265.04   762.6 2272.81   778.8 2276.06     882 2287.79
#Mann= 4 ,-1,0
       0      .1       0   253.1    .045       0   285.9     .06       0
     360      .1       0
Bank Sta=253.1,285.9
XS Rating Curve= 0 ,0
Exp/Cntr(USF)=0,0
Exp/Cntr=0.3,0.1

Type RM Length L Ch R = 1 ,22125   ,234.3,238.4,243.6
XS GIS Cut Line= 3
2368571.51639965 721288.317355752368459.60049097720867.289241538
2368424.48545699720454.906770618
#Sta/Elev= 30
       0 2464.92    47.8 2424.22    57.6  2410.8     115 2370.16   127.4 2357.73
   139.4 2350.35   153.1 2338.62   168.8 2321.39   218.5 2284.23     235 2263.95
   257.1 2262.81   268.1 2257.29   275.9 2256.05   284.7 2255.93   321.9 2256.31
   345.4 2260.07   367.5 2259.35   379.9 2256.58   391.1  2260.1   408.9 2261.43
   473.9 2258.34   526.1 2263.93   562.2 2260.95   594.3 2261.83   610.4 2260.22
   738.9 2269.31     775 2275.52   807.1  2290.7   819.1  2294.6   849.5  2298.1
#Mann= 5 ,-1,0
       0      .1       0     230     .06       0   275.9    .045       0
   321.9     .06       0     330      .1       0
Bank Sta=275.9,321.9
XS Rating Curve= 0 ,0
Exp/Cntr=0.3,0.1

Type RM Length L Ch R = 1 ,21887   ,260.9,258,254.7
XS GIS Cut Line= 2
2368753.34181106721215.2745874492368677.35334476720465.751988068
#Sta/Elev= 30
       0 2428.54    14.2 2416.97    42.3 2396.03    54.4  2388.4    74.5 2371.21
   102.6 2348.93     138 2322.65   158.9 2308.46   185.5 2287.38   211.2  2262.5
   231.3 2261.58   239.3  2256.5   251.4 2255.18   267.5 2255.12   309.6 2255.24
   320.6 2255.47   335.8 2257.37   347.9 2255.62     368  2255.4     380 2258.68
   392.1 2257.86   404.2 2259.48   424.3 2260.19   500.6 2260.54     514 2262.08
   633.3 2264.58   645.5 2268.66   685.7 2288.31   717.8 2293.33   753.4 2296.29
#Mann= 5 ,-1,0
       0      .1       0     150     .06       0     240      .1       0
   251.4    .045       0   309.6      .1       0
Bank Sta=251.4,309.6
XS Rating Curve= 0 ,0
Exp/Cntr(USF)=0,0
Exp/Cntr=0.3,0.1

Type RM Length L Ch R = 1 ,21629   ,220.2,225.1,233.7
XS GIS Cut Line= 2
2369037.10535547721162.413316665 2368891.1484474720481.976013281
#Sta/Elev= 30
       0 2406.73    38.9 2385.62    50.4 2378.17    62.5 2373.45      86 2357.37
    95.4 2354.19     169  2308.9   185.4 2297.44   205.8  2280.1   222.2 2260.86
   226.3  2259.4   242.6 2259.53   246.7 2258.18   250.8 2254.93     259 2253.97
   295.8 2253.74     304 2253.91   320.4 2254.84   361.3 2253.99   375.7 2256.46
   399.3 2256.76   426.7 2259.53   451.3 2260.28   467.6 2262.23   479.9 2265.49
   493.6  2265.6   504.5 2268.02   608.1  2277.3     664  2275.3   695.9 2279.81
#Mann= 4 ,-1,0
       0      .1       0     190     .06       0     259    .045       0
     304      .1       0
Bank Sta=259,304
XS Rating Curve= 0 ,0
Exp/Cntr=0.3,0.1

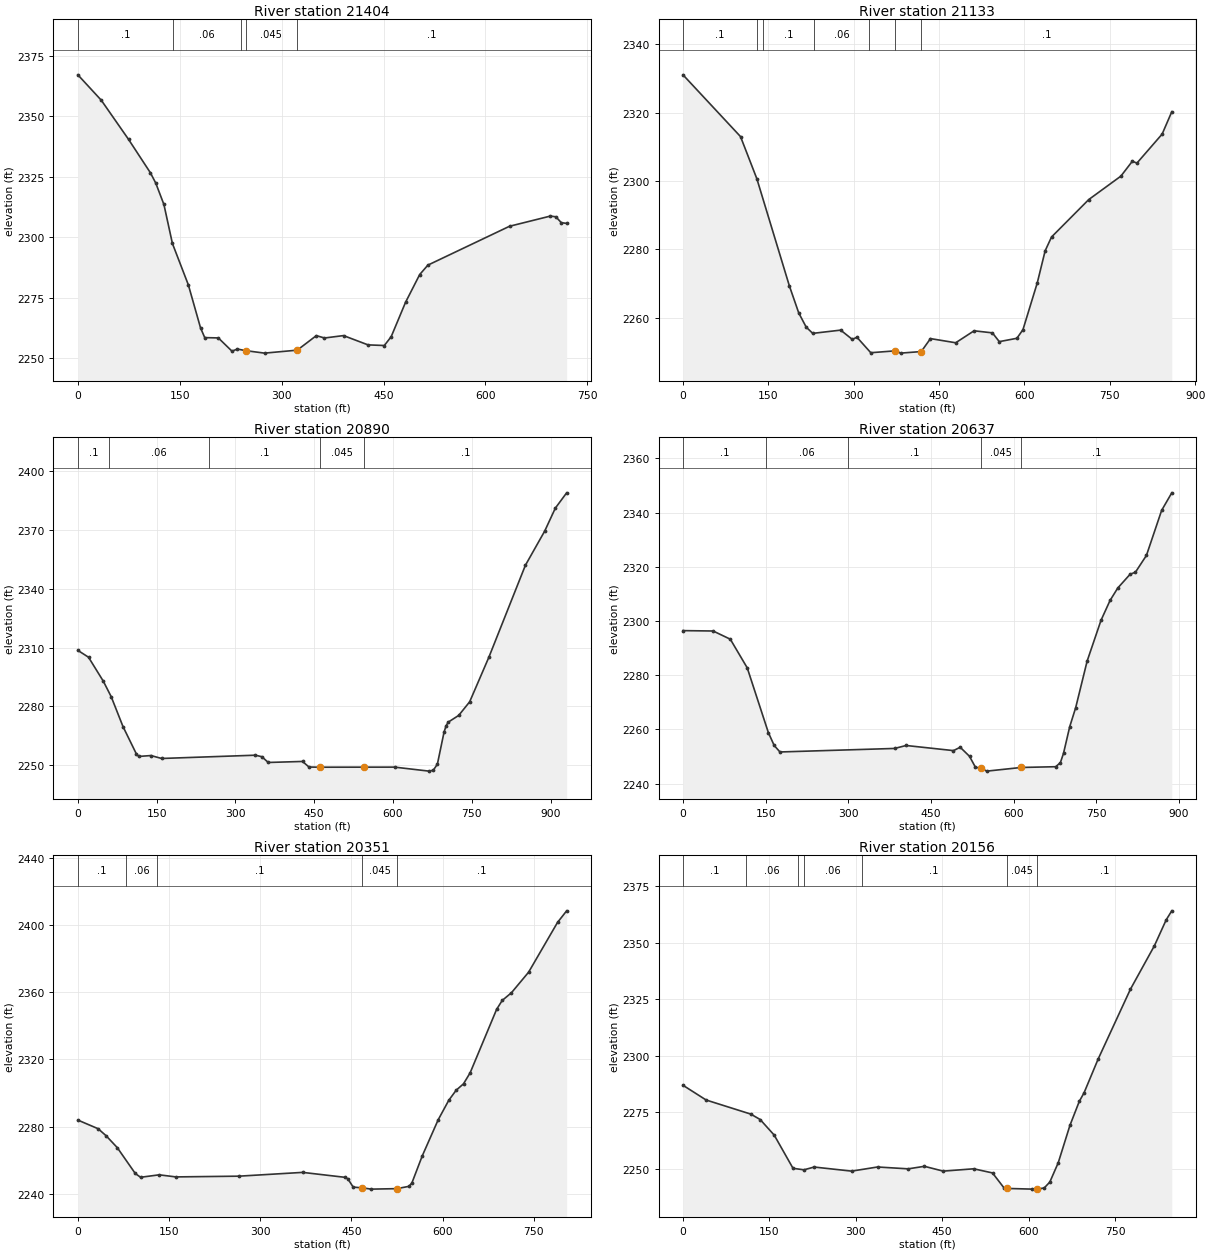
Type RM Length L Ch R = 1 ,21404   ,273.2,271.1,270
XS GIS Cut Line= 2
2369212.72663003721111.6539515892369171.27837569720393.217542967
#Sta/Elev= 30
       0 2367.08    34.5 2356.57    74.6  2340.4   106.7 2326.62   114.7  2322.3
   126.7 2313.46   139.2 2297.35   162.7  2280.2   180.6 2262.45   186.8 2258.41
   206.8 2258.29   226.9 2252.81   234.9 2253.69   246.9 2253.03   274.9    2252
     323 2253.23   351.1 2259.23   363.1 2258.26   391.1 2259.25   427.2 2255.41
   451.2 2255.15   461.3 2258.81   482.5 2273.06   503.3 2284.51   515.3 2288.39
   635.5 2304.46   695.6 2308.67   703.7 2308.38   711.7 2305.96   719.6 2305.64
#Mann= 5 ,-1,0
       0      .1       0     140     .06       0     240      .1       0
   246.9    .045       0     323      .1       0
Bank Sta=246.9,323
XS Rating Curve= 0 ,0
Exp/Cntr(USF)=0,0
Exp/Cntr=0.3,0.1

Type RM Length L Ch R = 1 ,21133   ,239.5,242.9,271.9
XS GIS Cut Line= 3
2369409.80485664721196.043618485 2369476.3914763720886.426334121
      2369408.93      720348.406
#Sta/Elev= 30
       0 2331.04   101.1 2312.97   129.8 2300.64     187 2269.27   203.4 2261.39
   216.5 2257.24     228 2255.41   277.1 2256.36   297.5 2253.65   305.7 2254.27
     330 2249.75   373.2  2250.3   382.4 2249.63   418.7 2250.09   434.9 2253.88
   479.2 2252.66   511.5 2256.16   543.7 2255.56   555.8 2252.99   586.7 2253.97
   597.4 2256.49   622.5 2270.15   636.4 2279.56   647.6  2283.6     713 2294.55
   769.5 2301.41   789.6 2305.76   797.7 2305.22     842 2313.71   858.9 2320.24
#Mann= 7 ,-1,0
       0      .1       0     130     .06       0     140      .1       0
     230     .06       0   326.7      .1       0   373.2    .045       0
   418.7      .1       0
Bank Sta=373.2,418.7
XS Rating Curve= 0 ,0
Exp/Cntr=0.3,0.1

Type RM Length L Ch R = 1 ,20890   ,227.9,253.1,281.6
XS GIS Cut Line= 3
2369506.31843163721194.550460277 2369679.0194914720911.320722262
2369796.45621204720324.137119061
#Sta/Elev= 30
       0 2308.58    20.3 2305.08    48.5 2292.83    63.5 2284.93    85.9  2269.7
   111.1 2255.88   115.9 2254.44   139.1 2254.89   159.5  2253.4     338 2255.07
   350.2  2254.3   362.5 2251.36   427.7 2251.88     440 2249.03   460.3 2248.94
   545.3 2248.97   603.1 2248.98   668.4 2246.94   676.6 2247.39   684.4 2250.46
     697 2266.71     701 2270.08   705.1 2271.95   725.1  2275.4   745.9 2282.34
   782.6 2305.18     852 2352.03   888.8 2369.51     909  2381.2   930.5    2389
#Mann= 5 ,-1,0
       0      .1       0      60     .06       0     250      .1       0
   460.3    .045       0   545.3      .1       0
Bank Sta=460.3,545.3
XS Rating Curve= 0 ,0
Exp/Cntr(USF)=0,0
Exp/Cntr=0.3,0.1

Type RM Length L Ch R = 1 ,20637   ,274.7,285.3,292.5
XS GIS Cut Line= 3
2369540.18523756721298.6750953792369874.81452311 720909.41709597
2370162.31199941720670.619287318
#Sta/Elev= 30
       0 2296.47    54.7 2296.33    85.9  2293.3   116.6 2282.73   154.9 2258.87
   165.5 2254.09     176 2251.69     384 2252.99     405 2254.08   490.9 2252.19
   503.1 2253.43     520 2250.09   530.7 2246.07     540 2245.71   551.4 2244.62
   613.9 2245.97   676.4 2246.25   684.9 2247.73   690.6 2251.17   701.9 2261.03
   712.7 2268.03   733.5 2285.24   758.7 2300.29   775.1 2307.61   789.1  2312.2
   811.5 2317.27   821.2 2318.04   841.1 2324.22   868.7 2340.84   887.1 2347.32
#Mann= 5 ,-1,0
       0      .1       0     150     .06       0     300      .1       0
     540    .045       0   613.9      .1       0
Bank Sta=540,613.9
XS Rating Curve= 0 ,0
Exp/Cntr=0.3,0.1

Type RM Length L Ch R = 1 ,20351   ,189.7,194.8,202.5
XS GIS Cut Line= 2
2369621.72314342721303.3736895232370357.42965802720978.695697164
#Sta/Elev= 30
       0 2283.98    33.3 2278.85    46.4  2274.7    64.9 2267.58    94.5 2252.23
   103.2 2249.98   133.8 2251.44   161.3  2250.2     265 2250.64   369.9 2252.89
   439.9 2249.94   444.3 2249.02     453 2244.13   467.6 2243.71   482.8 2242.94
   524.8 2243.22   544.8  2244.6   549.6 2246.61   566.7 2262.76   592.9  2284.2
   610.2  2295.7   622.4 2301.71   634.5 2305.53   645.4 2312.06     689  2349.8
   698.2 2355.08   713.4 2359.67   741.6 2371.87   789.2 2401.46   804.2 2408.35
#Mann= 5 ,-1,0
       0      .1       0      80     .06       0     130      .1       0
   467.6    .045       0   524.8      .1       0
Bank Sta=467.6,524.8
XS Rating Curve= 0 ,0
Exp/Cntr(USF)=0,0
Exp/Cntr=0.3,0.1

Type RM Length L Ch R = 1 ,20156   ,227.5,235.6,244.7
XS GIS Cut Line= 2
2369532.65923697      721407.7882370365.73200236721246.600475712
#Sta/Elev= 30
       0    2287    40.2 2280.48   117.7 2274.25     134 2271.85   158.4 2264.95
     191 2250.28     210 2249.61   227.7 2250.84   292.8 2249.03   337.7 2250.86
     391 2250.04   419.1 2251.16   451.7 2249.03   504.7 2250.06   537.3 2248.23
   557.7 2241.47   561.7 2241.38   606.6 2241.07   614.7 2241.16   626.9 2241.55
   636.8  2244.2   651.4 2252.73   671.7 2269.25     688 2279.91   696.2 2283.65
   720.6 2298.55   776.7 2329.47   818.4 2348.73   838.8 2360.16   848.5 2364.15
#Mann= 7 ,-1,0
       0      .1       0     110     .06       0     200      .1       0
     210     .06       0     310      .1       0   561.7    .045       0
   614.7      .1       0
Bank Sta=561.7,614.7
XS Rating Curve= 0 ,0
Exp/Cntr=0.3,0.1

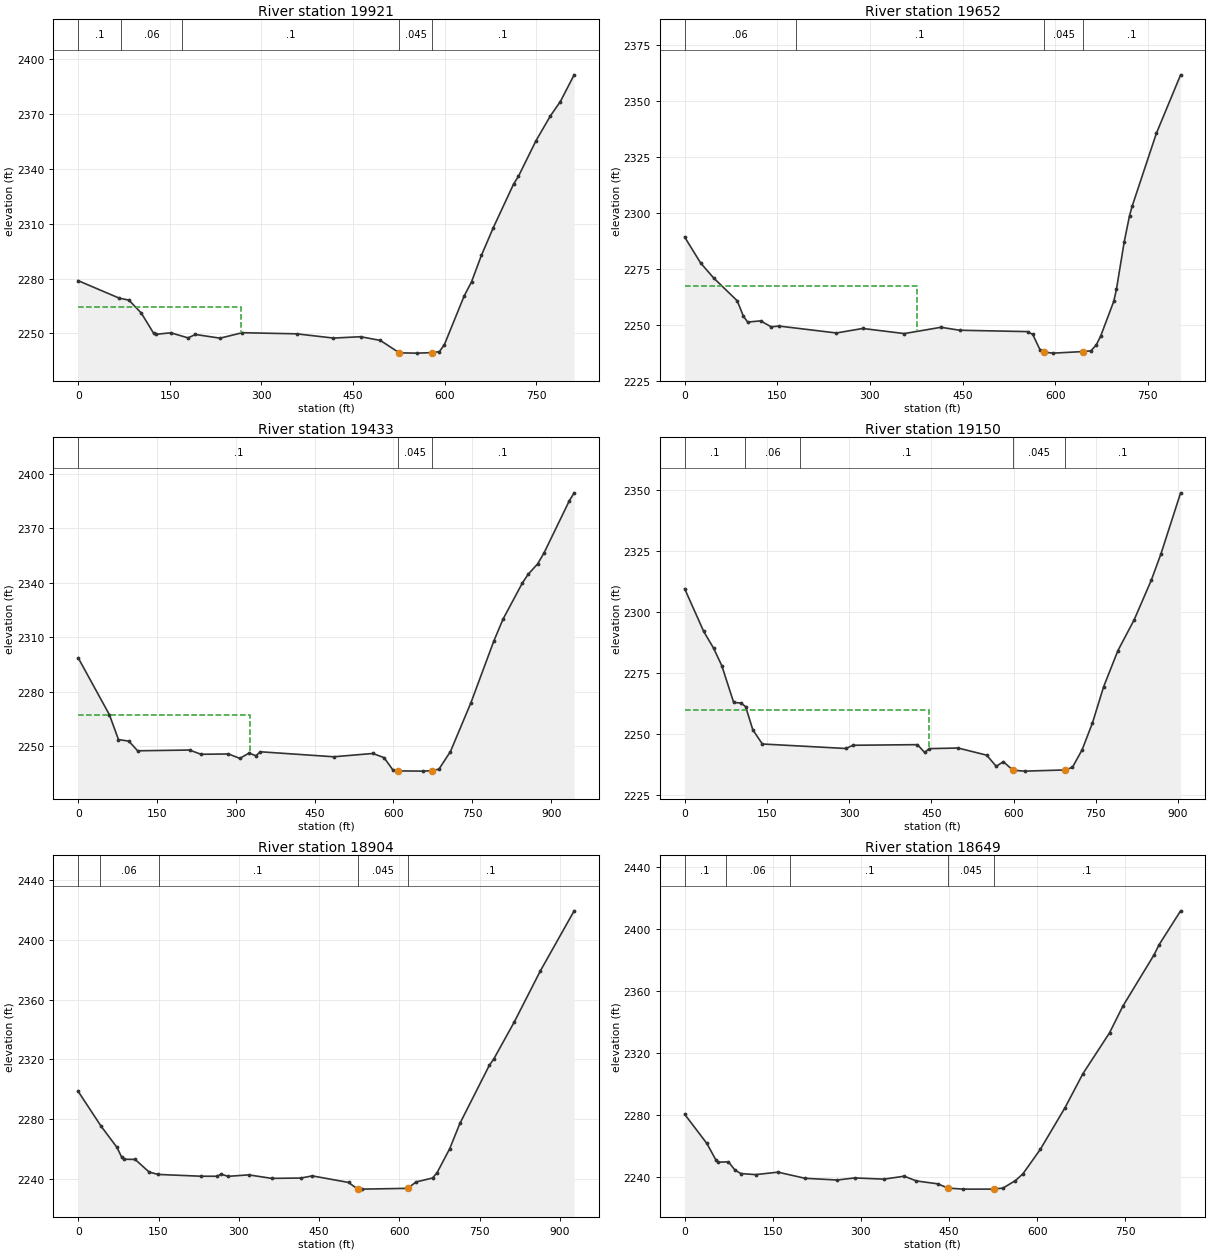
Type RM Length L Ch R = 1 ,19921   ,262.6,269.1,274.2
XS GIS Cut Line= 2
2369569.91282549721458.8046433112370374.69976399721565.879300366
#Sta/Elev= 30
       0 2278.85    66.8 2269.36      83 2268.23   103.2 2261.19   123.3 2250.21
   127.4 2249.54   151.6 2250.38   179.8 2247.59   191.9 2249.45   232.3 2247.44
   268.6 2250.42   357.4 2249.81   417.9 2247.49   462.3 2248.23   494.6  2246.2
   525.8  2239.4   555.1 2239.26   579.3 2239.53   591.4 2240.12   599.5 2243.93
   631.8 2270.47   643.9 2278.24     660 2292.64   679.4 2307.73   712.8  2331.7
   720.6 2335.83   749.2 2355.22     773 2368.93   789.2  2376.7   811.9 2391.37
#Mann= 5 ,-1,0
       0      .1       0      70     .06       0     170      .1       0
   525.8    .045       0   579.3      .1       0
#XS Ineff= 2 , 0
          266.82 2264.32
Permanent Ineff=
       F       F
Bank Sta=525.8,579.3
XS Rating Curve= 0 ,0
Exp/Cntr(USF)=0,0
Exp/Cntr=0.3,0.1

Type RM Length L Ch R = 1 ,19652   ,214.9,218.2,219.5
XS GIS Cut Line= 2
2369467.85204621721588.4958566362370226.38304917721853.040381515
#Sta/Elev= 30
       0 2289.18    25.9  2277.6    46.9 2270.95    85.1 2260.75      95 2253.95
     102 2251.24     123 2251.79   140.1 2249.12   152.8 2249.46   245.8 2246.38
   288.4 2248.39   355.7 2246.11   415.1 2248.92   445.2  2247.6   555.3 2246.99
   563.8 2245.72   575.6 2238.84   581.9 2237.82   597.3 2237.38   645.9 2238.09
     658  2238.4   666.7 2241.04   673.9 2245.07   695.1 2260.58   699.3 2265.79
     712 2287.14   720.5 2298.69   724.7 2302.89     764 2335.49   803.3 2361.63
#Mann= 4 ,-1,0
       0     .06       0     180      .1       0   581.9    .045       0
   645.9      .1       0
#XS Ineff= 2 , 0
          377.05 2267.24
Permanent Ineff=
       F       F
Bank Sta=581.9,645.9
XS Rating Curve= 0 ,0
Exp/Cntr=0.3,0.1

Type RM Length L Ch R = 1 ,19433   ,283.8,283.1,283
XS GIS Cut Line= 2
2369369.57959616721735.1263389362370236.53891618722108.160628028
#Sta/Elev= 30
       0 2298.63    59.4 2267.31    76.6 2253.66    96.3  2252.8   113.1 2247.48
   211.8  2247.9   233.6 2245.57   285.9 2245.73   307.6 2243.31   325.1 2246.22
   338.1 2244.77   346.8 2246.94   486.2 2244.19   560.7 2246.01     582 2243.72
   599.4 2236.73   609.4 2236.42     656 2236.29   673.3 2236.53   686.5  2237.4
   708.3 2247.03   747.5 2274.05     791 2307.94   808.4 2319.93   845.2 2339.82
   856.3 2344.65   874.3 2350.34   886.8 2356.58   934.7 2385.16   943.8 2389.47
#Mann= 3 ,-1,0
       0      .1       0   609.4    .045       0   673.3      .1       0
#XS Ineff= 2 , 0
          326.17 2267.26
Permanent Ineff=
       F       F
Bank Sta=609.4,673.3
XS Rating Curve= 0 ,0
Exp/Cntr(USF)=0,0
Exp/Cntr=0.3,0.1

Type RM Length L Ch R = 1 ,19150   ,248.6,245.9,242.3
XS GIS Cut Line= 2
 2369246.0222984721989.709482264 2370077.2652984722347.436575008
#Sta/Elev= 30
       0  2309.6    34.7 2292.12      53 2285.14    67.7 2278.08    89.4 2263.01
   102.5 2262.78   111.2  2261.3   124.3 2251.82   141.7 2245.98   294.1 2244.14
   307.2 2245.46   424.7 2245.71   437.8 2242.53   446.5 2244.08   498.8 2244.33
     551 2241.41   568.5 2236.82   581.5 2238.74   598.9 2235.22   620.7 2234.86
   694.7 2235.35   707.6 2236.45   725.2 2243.63   744.1 2254.64   764.4 2269.43
   790.5 2284.27   820.2 2296.91   851.5 2313.19   868.9 2323.82   904.9 2348.92
#Mann= 5 ,-1,0
       0      .1       0     110     .06       0     210      .1       0
   598.9    .045       0   694.7      .1       0
#XS Ineff= 2 , 0
          446.58 2259.75
Permanent Ineff=
       F       F
Bank Sta=598.9,694.7
XS Rating Curve= 0 ,0
Exp/Cntr=0.3,0.1

Type RM Length L Ch R = 1 ,18904   ,256.1,255.3,255.6
XS GIS Cut Line= 2
2369203.78657879722280.861687794 2370077.6539412722588.269574175
#Sta/Elev= 30
       0 2298.62    42.8 2275.34    72.1 2261.36      81 2254.85    85.2 2253.31
   106.4 2253.15   132.3 2244.78   148.8 2243.15   229.4 2241.94   259.1 2241.94
   267.5 2243.31   279.7 2241.86   318.4 2242.85   361.3 2240.51     416 2240.73
   437.2 2242.17     505 2237.78     522 2233.34   530.4 2233.32   615.3 2233.84
   631.1  2238.1   661.9 2240.75   670.4 2244.35   693.8 2260.24   713.1 2277.32
   767.9 2316.01   776.4 2320.39   814.5 2344.99   863.2 2379.11   926.4 2419.29
#Mann= 5 ,-1,0
       0      .1       0      40     .06       0     150      .1       0
     522    .045       0   615.3      .1       0
Bank Sta=522,615.3
XS Rating Curve= 0 ,0
Exp/Cntr(USF)=0,0
Exp/Cntr=0.3,0.1

Type RM Length L Ch R = 1 ,18649   ,276.7,275.7,275.1
XS GIS Cut Line= 2
2369177.51024113722552.1421112922369979.11271554722815.923039843
#Sta/Elev= 30
       0 2280.36    37.8 2261.51    53.3 2250.75    57.5 2249.43    74.4 2249.68
    85.3 2244.48    95.4 2242.12   120.7 2241.42   158.6 2243.01   204.9 2239.05
   259.6 2237.94   289.2 2239.28   338.8  2238.5   373.6  2240.4   394.4 2237.34
   430.7 2235.47   448.2 2232.74   474.4 2232.06   525.7 2232.07   541.8 2232.75
   562.9 2237.62   575.5 2241.91     605 2257.64   647.1 2284.55   677.8 2306.66
   722.9 2332.88   745.5 2350.06   798.7 2383.25   807.1 2389.67   843.9 2411.64
#Mann= 5 ,-1,0
       0      .1       0      70     .06       0     180      .1       0
   448.2    .045       0   525.7      .1       0
Bank Sta=448.2,525.7
XS Rating Curve= 0 ,0
Exp/Cntr=0.3,0.1