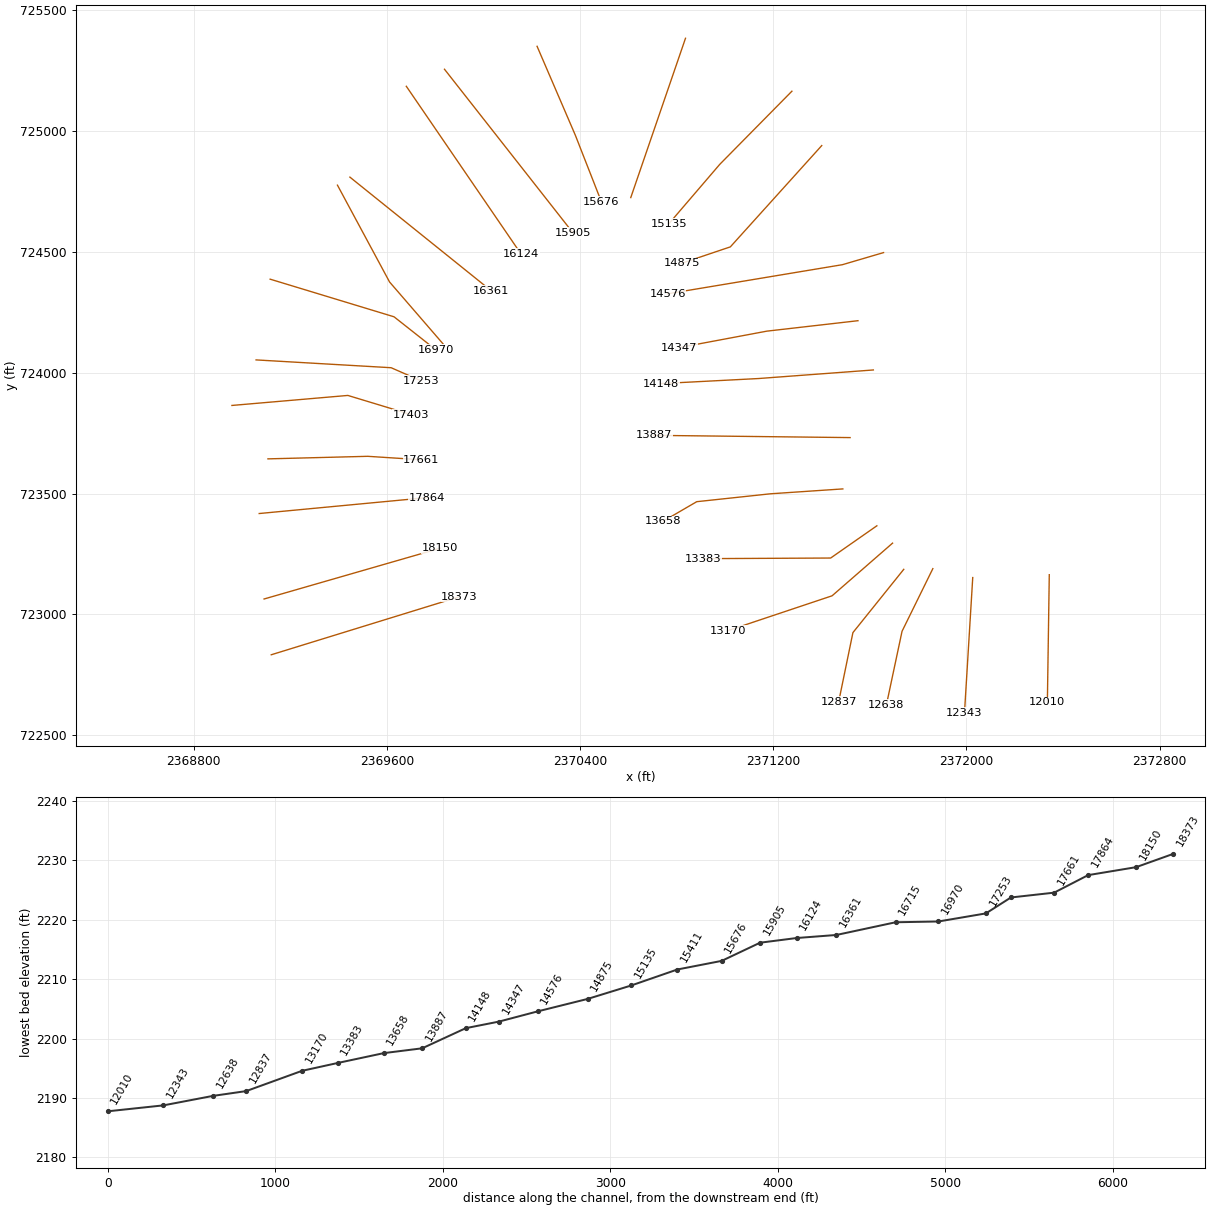
HEC-RAS study GLADYFK.prj: GLADYFK

--- GLADYFK.g01 (geometry) --- (continued)

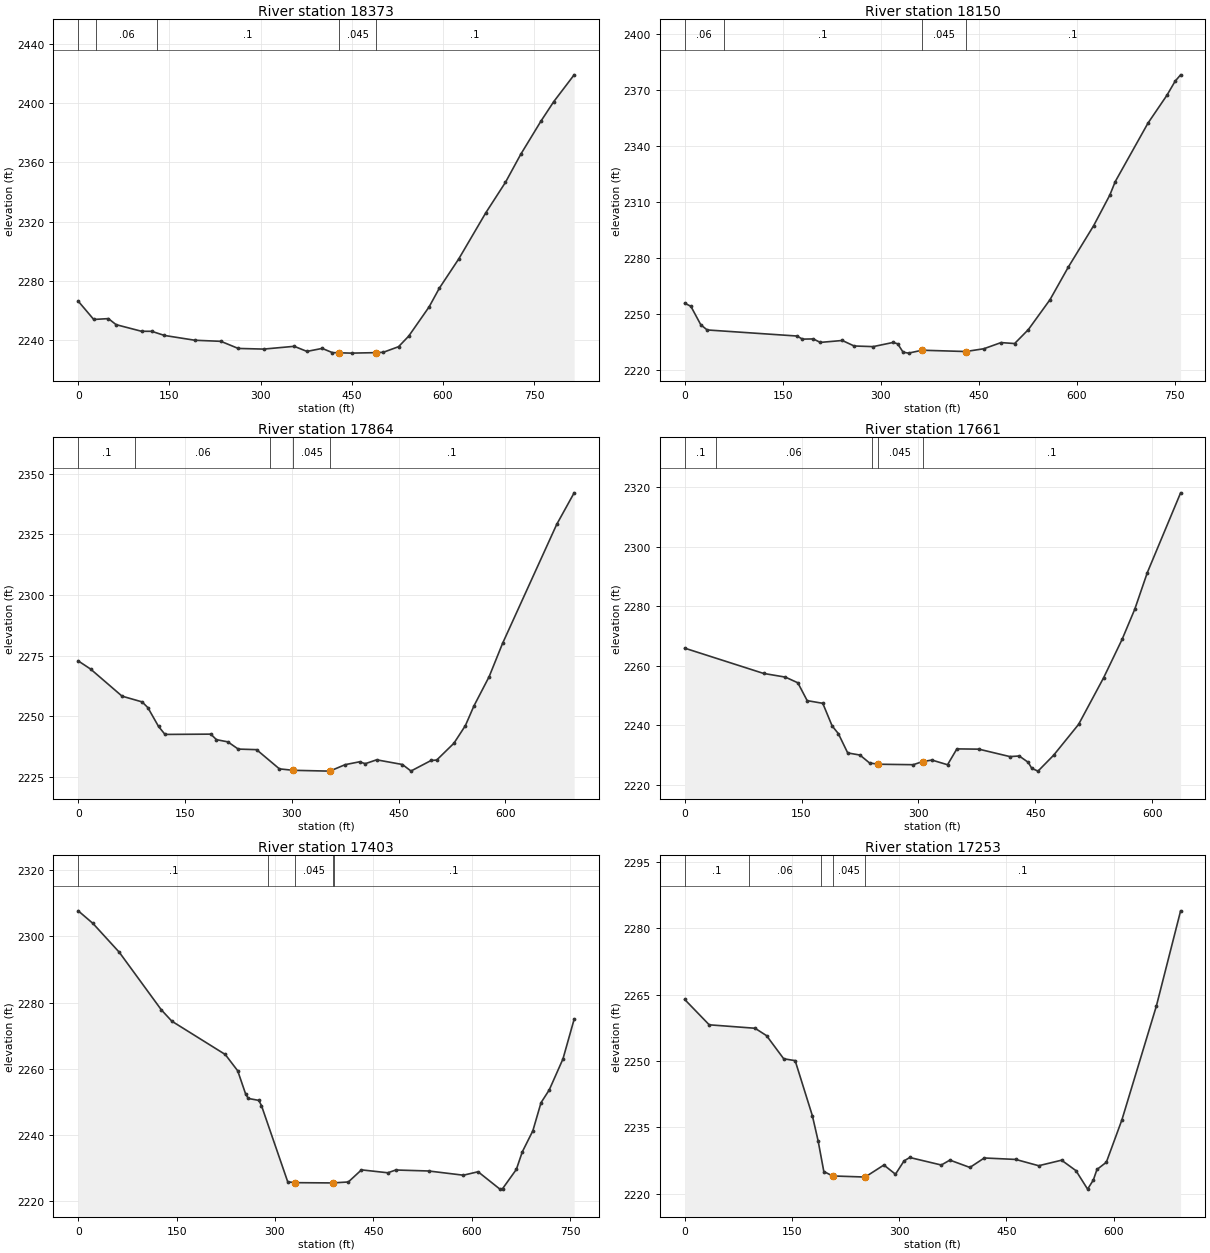
Type RM Length L Ch R = 1 ,18373   ,224.2,223,222.5
XS GIS Cut Line= 2
2369120.66755448722832.8215781552369900.23461183723073.037008616
#Sta/Elev= 30
       0 2266.21    25.5 2253.84    49.7  2254.4    62.3 2250.33   104.1 2245.85
   120.9 2245.83   141.8 2243.03     192 2239.78   234.7 2239.05   263.2 2234.25
     305 2233.81   355.3 2235.68   376.2 2232.24   401.3 2234.27     418 2231.43
   428.6 2231.32   449.5 2231.08   490.2 2231.42   501.8 2231.65   526.9 2235.43
   543.6 2242.58   577.1 2262.31   593.8 2274.86   626.1  2294.9   670.2 2325.81
   702.7 2346.51   727.8 2365.43   761.4 2388.09   782.2 2401.09   815.7 2419.18
#Mann= 5 ,-1,0
       0      .1       0      30     .06       0     130      .1       0
   428.6    .045       0   490.2      .1       0
Bank Sta=428.6,490.2
XS Rating Curve= 0 ,0
Exp/Cntr(USF)=0,0
Exp/Cntr=0.3,0.1

Type RM Length L Ch R = 1 ,18150   ,291.1,286.5,281.4
XS GIS Cut Line= 2
2369091.03578584723063.7271720362369820.23907434723273.867743718
#Sta/Elev= 30
       0 2255.64     9.5 2253.92    24.7 2244.02    34.4 2241.26   171.9    2238
   180.2 2236.34   196.8 2236.45   207.5 2234.58   241.2 2235.61   259.3 2232.66
   288.4 2232.32   318.8 2234.55   325.9 2233.84   334.2 2229.35   342.5 2228.83
   363.3 2230.39     430 2229.69   457.7 2231.17   484.1 2234.48   504.9 2233.97
   525.9 2241.45     559 2257.48     587 2274.94   625.8 2297.17   650.6 2313.61
   658.9 2320.84   708.9 2352.14     738 2367.14   750.5 2374.66   758.9 2378.07
#Mann= 4 ,-1,0
       0     .06       0      60      .1       0   363.3    .045       0
     430      .1       0
Bank Sta=363.3,430
XS Rating Curve= 0 ,0
Exp/Cntr=0.3,0.1

Type RM Length L Ch R = 1 ,17864   ,204.9,203,201.2
XS GIS Cut Line= 2
2369070.81152174723417.4968711642369764.26361345723483.216187045
#Sta/Elev= 30
       0  2272.9    17.4 2269.53    61.6 2258.37    89.8    2256    97.8 2253.66
   112.8 2245.91   121.9 2242.61   186.2 2242.73   194.2 2240.45   210.2 2239.54
   224.8 2236.57   250.5 2236.34   282.6 2228.42   301.9 2227.83   353.3 2227.49
     375 2230.16   395.1 2231.33   403.2 2230.56   419.2 2232.15   455.4 2230.22
   467.4 2227.53   495.6 2231.87   503.6 2232.07   527.7 2238.97   543.8 2246.23
   555.8 2254.33   577.2 2266.41     596 2280.08   672.1 2329.13   696.6 2342.13
#Mann= 5 ,-1,0
       0      .1       0      80     .06       0     270      .1       0
   301.9    .045       0   353.3      .1       0
Bank Sta=301.9,353.3
XS Rating Curve= 0 ,0
Exp/Cntr(USF)=0,0
Exp/Cntr=0.3,0.1

Type RM Length L Ch R = 1 ,17661   ,255.2,258,259
XS GIS Cut Line= 3
 2369107.0107016723643.7778431862369520.54334407      723654.331
2369742.77749911723640.035728495
#Sta/Elev= 30
       0  2265.9   101.2  2257.4   129.2 2256.16   145.2 2254.25   157.2 2248.25
   177.2 2247.35   189.2 2239.75   197.2 2237.15   209.2 2230.66   224.9 2229.95
   237.2 2227.29   248.3 2226.86   293.3  2226.7   305.3 2227.75   317.3 2228.26
   337.3 2226.69   349.3 2232.02   377.5 2231.93   417.3 2229.43   429.3 2229.63
   440.8 2227.51   445.4 2225.48   453.4 2224.54   473.4 2229.88   505.5 2240.27
   537.6 2255.95   561.3 2268.85   577.6 2279.02   593.7 2291.33   636.4 2318.14
#Mann= 5 ,-1,0
       0      .1       0      40     .06       0     240      .1       0
   248.3    .045       0   305.3      .1       0
Bank Sta=248.3,305.3
XS Rating Curve= 0 ,0
Exp/Cntr=0.3,0.1

Type RM Length L Ch R = 1 ,17403   ,151.2,149.5,146
XS GIS Cut Line= 3
2368957.84896999723864.9008850172369437.95791614 723906.34913936
2369700.46352698723826.906651868
#Sta/Elev= 30
       0 2307.67    22.4 2303.88    62.6 2295.18   126.8 2277.79   142.8 2274.38
   224.2 2264.34   243.2 2259.42   255.3 2252.41   259.3 2251.08   275.3  2250.5
   279.4 2248.94   319.5 2225.92   331.3 2225.68   387.8  2225.6   411.9 2225.89
   431.9 2229.54   472.1 2228.66   484.2  2229.5   534.4  2229.2   587.3 2227.93
   609.7 2228.97     643 2223.73   647.2 2223.91   668.1 2229.69   677.1 2234.96
   693.2 2241.32   705.7 2249.81   718.2 2253.65   739.1 2262.98   756.2 2274.98
#Mann= 5 ,-1,0
       0      .1       0     290     .06       0   331.3    .045       0
   387.8     .06       0     390      .1       0
Bank Sta=331.3,387.8
XS Rating Curve= 0 ,0
Exp/Cntr(USF)=0,0
Exp/Cntr=0.3,0.1

Type RM Length L Ch R = 1 ,17253   ,288.5,283.4,278.5
XS GIS Cut Line= 3
2369057.90942614724053.4125620362369617.20166679724021.096920946
2369739.36351172723967.563889089
#Sta/Elev= 30
       0 2263.92    34.3 2258.19    98.4 2257.41   114.5 2255.74   138.5 2250.51
   154.5 2250.09   178.6 2237.63   186.6 2231.98   194.6 2225.03   206.9 2224.03
   252.4 2223.78   278.6  2226.5   294.8 2224.42   306.8 2227.43   314.8  2228.2
   358.9  2226.5   370.9 2227.61   398.9 2225.95     419 2228.09     463 2227.76
   495.1 2226.34   527.1 2227.59   547.2 2225.23   563.5 2221.05   571.5 2223.09
   576.6 2225.49   589.7 2227.12   611.5 2236.71   659.7 2262.44   693.6 2283.95
#Mann= 5 ,-1,0
       0      .1       0      90     .06       0     190      .1       0
   206.9    .045       0   252.4      .1       0
Bank Sta=206.9,252.4
XS Rating Curve= 0 ,0
Exp/Cntr=0.3,0.1

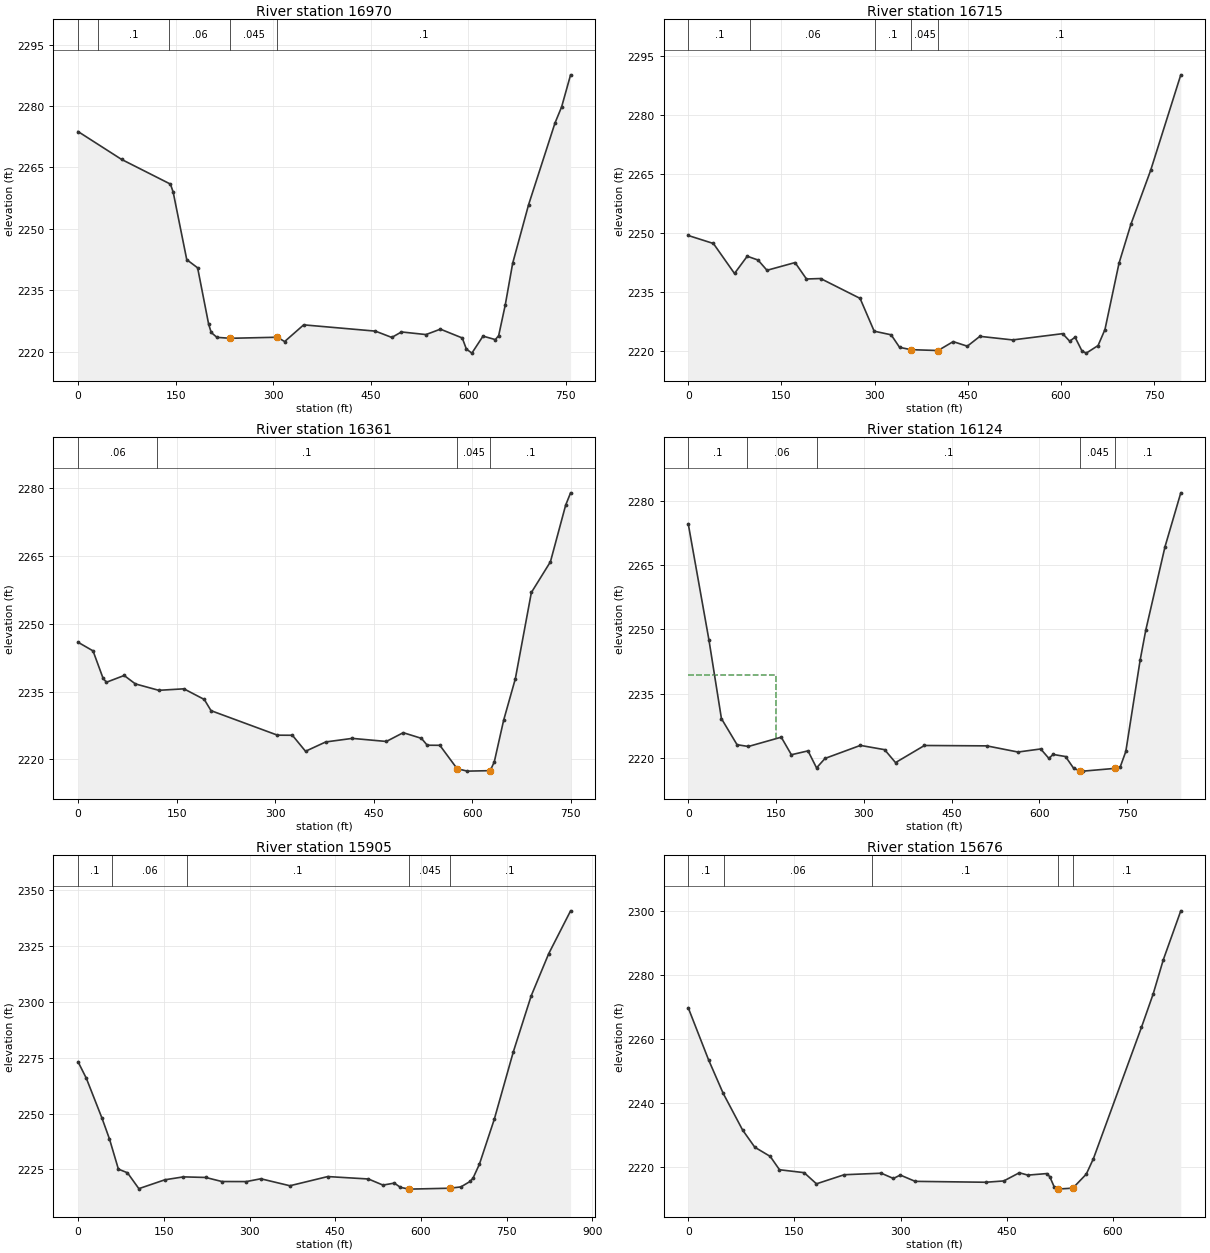
Type RM Length L Ch R = 1 ,16970   ,272.1,255.3,217.2
XS GIS Cut Line= 3
2369116.16930092724387.626982841 2369629.2676035724231.895529209
2369803.00832365724094.837988533
#Sta/Elev= 30
       0 2273.77    66.9 2266.97   142.1 2260.94   146.3 2258.99   167.2  2242.5
   183.9 2240.51   200.8  2226.8   204.8 2224.73   213.6 2223.54   234.1 2223.31
   306.6 2223.57   317.7 2222.51     347 2226.59   457.3 2225.06   482.5 2223.52
   497.4 2224.86   535.1 2224.22   557.3 2225.54   590.9 2223.39   597.2 2220.69
   605.7 2219.69   622.8 2223.84   641.8 2222.99   646.9 2223.97     657 2231.43
   668.4 2241.61   692.8 2255.86   733.5 2275.85   743.7 2279.78   757.5 2287.61
#Mann= 5 ,-1,0
       0     .06       0      30      .1       0     140     .06       0
   234.1    .045       0   306.6      .1       0
Bank Sta=234.1,306.6
XS Rating Curve= 0 ,0
Exp/Cntr(USF)=0,0
Exp/Cntr=0.3,0.1

Type RM Length L Ch R = 1 ,16715   ,343.7,354,369.3
XS GIS Cut Line= 3
2369394.90881306724776.840406532 2369610.6589759724376.096021919
 2369831.7163324724120.498453468
#Sta/Elev= 30
       0 2249.41    40.5 2247.38    74.5 2239.77      95 2244.15   112.4 2243.18
   126.8 2240.58     172 2242.54   190.4 2238.37   213.1 2238.49   276.7 2233.45
   299.4 2225.13   326.7 2224.21   340.3 2221.03   358.5 2220.44   402.3 2220.22
   426.6 2222.48   449.4 2221.32   469.6 2223.82   522.4 2222.91   602.9  2224.5
   614.2 2222.59   622.9  2223.6   634.1 2220.07   640.9 2219.56   659.9 2221.48
     671 2225.55   693.6 2242.35   712.8 2252.27   744.6 2265.95   793.1 2290.18
#Mann= 5 ,-1,0
       0      .1       0     100     .06       0     300      .1       0
   358.5    .045       0   402.3      .1       0
Bank Sta=358.5,402.3
XS Rating Curve= 0 ,0
Exp/Cntr=0.3,0.1

Type RM Length L Ch R = 1 ,16361   ,246.1,236.5,229.3
XS GIS Cut Line= 2
2369446.42035175724810.087701217 2370030.7354599724340.468337486
#Sta/Elev= 30
       0 2245.92    22.8 2244.01    38.2 2237.91    43.3 2237.08    70.2 2238.57
    87.2 2236.71   122.8 2235.29   161.1 2235.62   192.1 2233.27   202.4 2230.79
   303.5 2225.37   326.2 2225.35   346.2 2221.81   376.9 2223.87   417.3 2224.66
   469.2 2223.98   494.9 2225.92   522.6 2224.67   531.4 2223.15   550.6 2223.13
   576.92217.958   592.4 2217.42   627.32217.525   633.5 2219.48   647.7 2228.67
   665.5 2237.84   689.9 2256.92   718.9 2263.71   742.1 2276.24   749.6 2278.96
#Mann= 4 ,-1,0
       0     .06       0     120      .1       0   576.9    .045       0
   627.3      .1       0
Bank Sta=576.9,627.3
XS Rating Curve= 0 ,0
Exp/Cntr(USF)=0,0
Exp/Cntr=0.3,0.1

Type RM Length L Ch R = 1 ,16124   ,218.2,219.1,219.6
XS GIS Cut Line= 2
2369680.15947012725186.0405048662370155.40659347724491.711448922
#Sta/Elev= 30
       0 2274.69    35.4 2247.53    56.7 2229.18    83.4 2223.08   102.8 2222.67
   158.9 2224.84   176.2 2220.74   204.6 2221.64   219.2 2217.67   233.7 2219.88
   294.1 2222.92   335.5 2221.92   354.1  2218.9   403.5  2222.9     510 2222.81
   563.3 2221.37   602.1 2222.09   616.1 2219.88   623.2 2220.81   644.5 2220.32
   658.6 2217.53     670 2216.96   674.8 2216.91   729.5 2217.56   737.8 2217.84
   747.5 2221.51   771.9 2242.79   781.5 2249.79   814.4 2269.31   841.4 2281.92
#Mann= 5 ,-1,0
       0      .1       0     100     .06       0     220      .1       0
     670    .045       0   729.5      .1       0
#XS Ineff= 2 , 0
          150.37 2239.45
Permanent Ineff=
       F       F
Bank Sta=670,729.5
XS Rating Curve= 0 ,0
Exp/Cntr=0.3,0.1

Type RM Length L Ch R = 1 ,15905   ,243,229.4,220.7
XS GIS Cut Line= 2
2369838.21127386725256.6520963722370370.76435082 724579.06328781
#Sta/Elev= 30
       0 2273.18    14.6 2265.73      42 2247.85      55 2238.59    70.6 2225.08
    86.5 2223.44   106.4 2216.33     152 2220.31   184.4 2221.61   223.3 2221.35
   251.7 2219.53   294.4  2219.5   319.8 2220.76   370.7 2217.63   436.9 2221.75
   508.1 2220.66   533.5 2217.93   553.4 2218.82   564.1 2216.91   579.3 2216.12
   650.5 2216.53   669.9 2217.12   686.2  2219.6   691.2  2221.1   702.3 2227.32
   728.2 2247.35   761.6 2277.64   792.9 2302.75   823.5 2321.61   861.8 2340.81
#Mann= 5 ,-1,0
       0      .1       0      60     .06       0     190      .1       0
   579.3    .045       0   650.5      .1       0
Bank Sta=579.3,650.5
XS Rating Curve= 0 ,0
Exp/Cntr(USF)=0,0
Exp/Cntr=0.3,0.1

Type RM Length L Ch R = 1 ,15676   ,283.1,264.7,256.6
XS GIS Cut Line= 3
2370221.72483044725351.547466296 2370379.8635337724984.292635859
2370487.83263968724708.802013552
#Sta/Elev= 30
       0 2269.75    28.7 2253.49    49.3 2243.03    76.7 2231.57      94 2226.16
   115.8 2223.29   128.9 2219.12   163.7 2218.21   181.1 2214.72   220.3 2217.56
   272.6 2218.04   289.8 2216.39   299.5 2217.46   320.5 2215.49   420.4 2215.21
   445.7 2215.62   467.6 2218.17   479.7 2217.44   506.3 2217.92   510.6 2216.97
   516.7 2213.86   521.3 2213.06   522.9 2213.09   543.2 2213.37   562.2 2217.74
   572.3 2222.59   640.2 2263.67   656.7 2274.08     671 2284.76   695.7 2300.06
#Mann= 5 ,-1,0
       0      .1       0      50     .06       0     260      .1       0
   522.9    .045       0   543.2      .1       0
Bank Sta=522.9,543.2
XS Rating Curve= 0 ,0
Exp/Cntr=0.3,0.1

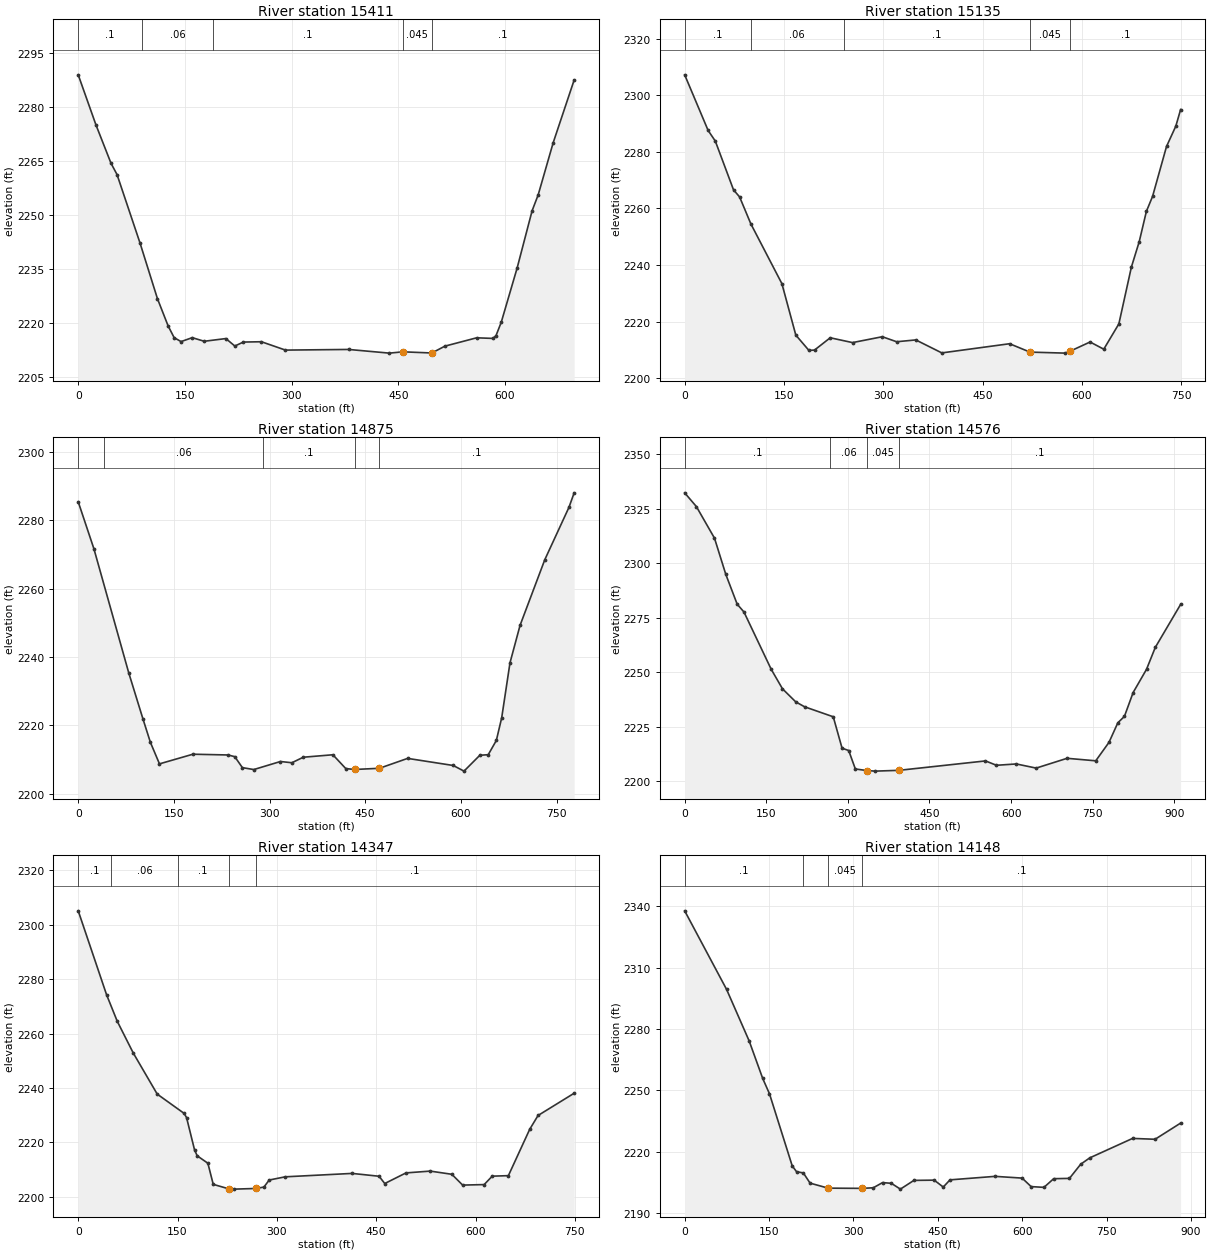
Type RM Length L Ch R = 1 ,15411   ,286.1,275.5,271.5
XS GIS Cut Line= 2
2370836.37741959725384.7766142222370609.75908897 724725.31727211
#Sta/Elev= 30
       0 2288.82      25  2274.9    46.1 2264.29    54.6 2261.14    86.8 2242.22
   111.4 2226.72   126.5 2219.12   134.9  2215.9   144.6 2214.81   160.3  2215.9
   177.2  2214.9   207.6 2215.65   220.2 2213.58   232.2 2214.68   257.6 2214.77
   291.4 2212.45   380.2 2212.63   437.4 2211.61   456.6 2211.97   497.2 2211.65
   515.6 2213.55   560.2 2215.86   583.3 2215.69   587.5  2216.5   594.8 2220.18
   617.1  2235.2   638.2 2251.12   646.7  2255.5   667.8 2269.97   697.3 2287.38
#Mann= 5 ,-1,0
       0      .1       0      90     .06       0     190      .1       0
   456.6    .045       0   497.2      .1       0
Bank Sta=456.6,497.2
XS Rating Curve= 0 ,0
Exp/Cntr(USF)=0,0
Exp/Cntr=0.3,0.1

Type RM Length L Ch R = 1 ,15135   ,259.4,260.1,259
XS GIS Cut Line= 3
2371277.06948749 725165.719402712370978.45136924724863.113010455
2370767.45725817724617.000067407
#Sta/Elev= 30
       0 2307.19    35.4 2287.56    46.3 2283.78    73.8 2266.57      83 2264.07
     100 2254.55   146.9 2233.44   167.9 2215.29   187.7 2209.88   196.2    2210
   219.9 2214.34   253.6 2212.64   298.6 2214.71   320.2 2212.94   349.2 2213.58
   388.5    2209   490.9 2212.24   521.7 2209.28   575.2 2208.92   582.3  2209.6
   612.5 2212.85   633.2 2210.31     656 2219.25   674.9 2239.28   686.8 2248.31
   697.6 2258.99   706.9 2264.25     728 2281.89   742.1  2289.1   749.3 2294.94
#Mann= 5 ,-1,0
       0      .1       0     100     .06       0     240      .1       0
   521.7    .045       0   582.3      .1       0
Bank Sta=521.7,582.3
XS Rating Curve= 0 ,0
Exp/Cntr=0.3,0.1

Type RM Length L Ch R = 1 ,14875   ,312.6,299,270.6
XS GIS Cut Line= 3
2371400.65706285724940.6046862022371022.20445071724521.360774549
2370820.51413645724453.375275362
#Sta/Elev= 30
       0 2285.33    24.6 2271.61    79.2 2235.38   101.6 2221.85   113.2 2215.06
   127.4 2208.78   179.8  2211.6     235 2211.38   245.5 2210.88   257.4 2207.68
   275.3 2207.12   317.1 2209.47     335 2209.11   352.9 2210.72   399.3 2211.44
   419.5 2207.41   433.2 2207.14   472.3 2207.49   516.5 2210.38     588 2208.31
   604.9 2206.66   629.7 2211.29   642.9 2211.46   655.6 2215.62     664 2222.25
     677  2238.3   692.8 2249.25   731.6 2268.43   769.5 2283.73   777.6 2287.95
#Mann= 5 ,-1,0
       0      .1       0      40     .06       0     290      .1       0
   433.2    .045       0   472.3      .1       0
Bank Sta=433.2,472.3
XS Rating Curve= 0 ,0
Exp/Cntr(USF)=0,0
Exp/Cntr=0.3,0.1

Type RM Length L Ch R = 1 ,14576   ,232.2,229.6,227.3
XS GIS Cut Line= 3
2371656.75510598724497.6763679632371486.51216574724447.648788047
2370762.30147012724327.092646456
#Sta/Elev= 30
       0 2332.19    21.5 2325.89    54.8  2311.4    75.6 2294.78    96.5 2281.12
     109 2277.53     159 2251.28   179.8  2242.3   204.1 2236.33   220.4 2234.07
   273.1 2229.48   289.3 2215.08   301.5 2214.01   313.7 2205.55   334.6 2204.84
   350.1 2204.56   393.7 2204.92   552.9 2209.24   573.1 2207.24   609.6 2207.85
   646.1 2205.95   702.9 2210.44   755.6 2209.29     780 2217.78   796.2 2226.73
   808.3 2229.66   824.3  2240.6   848.9 2251.24   865.1 2261.33   911.6 2281.02
#Mann= 4 ,-1,0
       0      .1       0  267.44     .06       0   334.6    .045       0
   393.7      .1       0
Bank Sta=334.6,393.7
XS Rating Curve= 0 ,0
Exp/Cntr=0.3,0.1

Type RM Length L Ch R = 1 ,14347   ,200.4,198.9,197.6
XS GIS Cut Line= 3
2371550.72974191724215.7061227952371173.21904135724172.465231451
2370810.62971235724104.479732264
#Sta/Elev= 30
       0 2305.06    42.8 2274.26    58.9 2264.52    83.1 2252.85   119.3 2237.75
   159.9 2230.67   163.6 2229.13   175.7 2217.24   179.7 2215.08   195.8 2212.36
   203.9  2204.6   227.4 2202.95   235.8 2202.85   268.3 2203.09   280.4  2203.6
   288.4 2206.19   312.6 2207.37   413.6 2208.62   454.3 2207.58   462.9 2204.91
     495 2208.81   531.6 2209.47   564.2  2208.3   580.5 2204.33     613 2204.52
   625.2 2207.61   649.6  2207.8   681.8 2224.83   694.4  2229.9   748.9 2238.07
#Mann= 5 ,-1,0
       0      .1       0      50     .06       0     150      .1       0
   227.4    .045       0   268.3      .1       0
Bank Sta=227.4,268.3
XS Rating Curve= 0 ,0
Exp/Cntr(USF)=0,0
Exp/Cntr=0.3,0.1

Type RM Length L Ch R = 1 ,14148   ,263.5,260.5,256.6
XS GIS Cut Line= 3
2371614.48395083724011.7994283182371137.87099823723976.257142773
2370734.81790344723955.373095379
#Sta/Elev= 30
       0 2337.78    74.5 2299.36   114.6 2274.19   138.7 2255.83   150.7 2248.37
   191.2 2213.06   198.9 2210.25   210.9 2209.66   222.9 2204.67     255 2202.22
   315.2 2202.11   335.2  2202.4   351.7 2204.93   367.3 2204.59   383.4 2201.74
   407.4 2206.01   443.5 2206.13   459.6 2202.76   471.6 2206.27   551.7 2207.98
   599.8 2207.13   615.8 2202.97   638.6 2202.61   655.9 2206.84   683.9 2206.99
   703.9 2213.91     720 2217.02   796.1 2226.53   836.1 2226.11   881.5 2234.02
#Mann= 4 ,-1,0
       0      .1       0     210     .06       0     255    .045       0
   315.2      .1       0
Bank Sta=255,315.2
XS Rating Curve= 0 ,0
Exp/Cntr=0.3,0.1

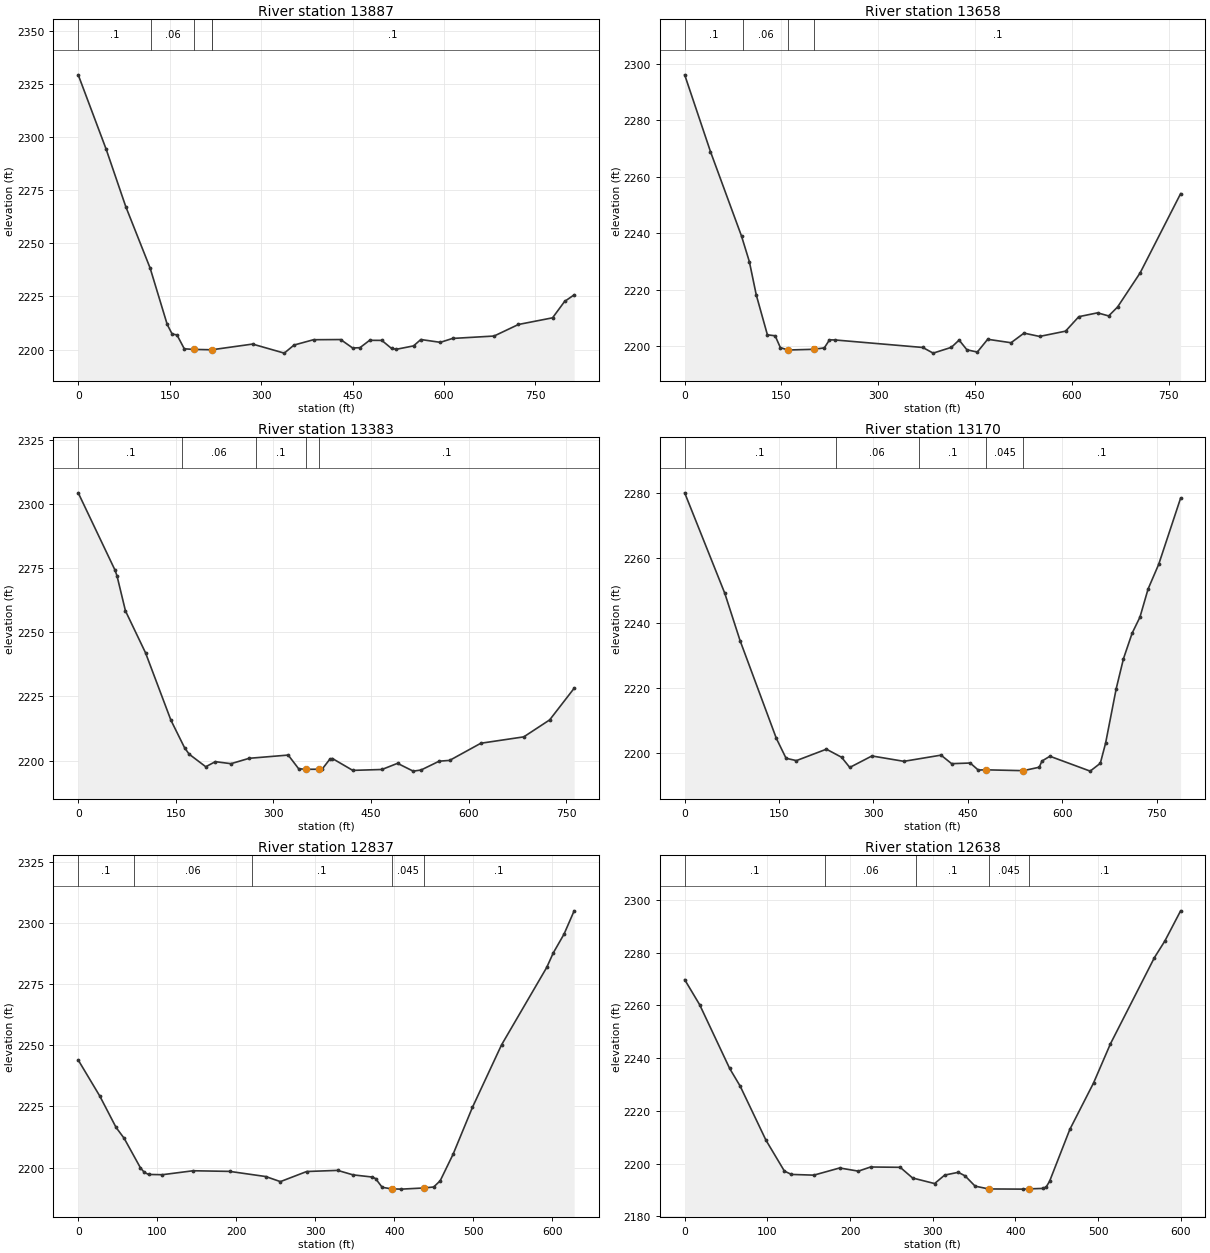
Type RM Length L Ch R = 1 ,13887   ,227.1,229.2,230.2
XS GIS Cut Line= 2
2371518.18250019723731.8184774622370704.78123282723741.144334689
#Sta/Elev= 30
       0 2329.32      46 2294.18      78 2267.31     118 2238.34     146 2211.83
     154 2207.38     162  2206.9     174 2200.39   189.2  2200.1   219.2 2199.93
     286 2202.61     338 2198.35     354 2202.15     386 2204.66   430.5 2204.74
   450.2 2200.76   462.1 2200.91     478 2204.38     498 2204.34     514 2200.55
     522 2200.17     550 2201.75     562 2204.75     594 2203.43     614 2205.26
   682.1 2206.39   722.1 2211.83   778.1 2214.97   797.8 2222.66   813.5 2225.78
#Mann= 5 ,-1,0
       0      .1       0     120     .06       0   189.2    .045       0
   219.2     .06       0     220      .1       0
Bank Sta=189.2,219.2
XS Rating Curve= 0 ,0
Exp/Cntr(USF)=0,0
Exp/Cntr=0.3,0.1

Type RM Length L Ch R = 1 ,13658   ,277.3,275.6,274.8
XS GIS Cut Line= 4
2371488.10552547723519.4245716822371188.91834193723499.242018291
2370883.00408735723466.5297096222370743.68020663723385.600652194
#Sta/Elev= 30
       0 2296.05      40 2268.86    88.1 2238.96   100.2 2229.96     111 2218.09
   128.2 2204.02   140.2 2203.68   148.3 2199.49   160.3 2198.64   200.4  2198.9
   216.4  2199.4   224.4 2202.23   232.5 2202.21     369 2199.54   385.1 2197.54
   413.3 2199.59   425.3 2202.16   437.4 2198.72   453.5 2197.92   469.6 2202.44
   505.8 2201.22   525.9 2204.62     550 2203.45   590.3 2205.32   610.8 2210.44
   639.8  2211.8   657.1 2210.71   670.9 2213.87   705.8 2225.92   768.6 2253.99
#Mann= 4 ,-1,0
       0      .1       0      90     .06       0   160.3    .045       0
   200.4      .1       0
Bank Sta=160.3,200.4
XS Rating Curve= 0 ,0
Exp/Cntr=0.3,0.1

Type RM Length L Ch R = 1 ,13383   ,204.8,212.7,230
XS GIS Cut Line= 3
2371628.97368405723366.7111670142371437.60709374723233.258150092
2370908.83098896 723230.74016864
#Sta/Elev= 30
       0 2304.38    56.3 2274.37    59.5 2272.11    72.6 2258.36   103.4 2242.03
   142.5 2215.71   163.5 2204.96   170.5 2202.49     196 2197.59   210.7 2199.57
   234.8 2198.78   262.7 2200.88   322.7 2202.14   338.7 2196.82   350.3 2196.59
   370.2 2196.62   375.3 2196.81   386.7 2200.55   390.7 2200.78   421.9 2196.17
   466.7 2196.52   490.7 2198.92   514.7 2195.88   526.7  2196.3   554.7 2199.76
   570.7 2200.06   618.7 2206.75   684.7 2209.24   724.5 2215.86   762.1 2228.19
#Mann= 5 ,-1,0
       0      .1       0     160     .06       0   273.3      .1       0
   350.3    .045       0   370.2      .1       0
Bank Sta=350.3,370.2
XS Rating Curve= 0 ,0
Exp/Cntr(USF)=0,0
Exp/Cntr=0.3,0.1

Type RM Length L Ch R = 1 ,13170   ,308.6,333.4,361
XS GIS Cut Line= 3
2371694.04366588723294.9680947882371443.57957286 723076.96409597
2371011.19333471 722932.40566647
#Sta/Elev= 30
       0 2280.04    63.7  2249.2      88 2234.66   145.7  2204.6   161.1 2198.51
   177.5 2197.79   225.2  2201.3   249.3 2198.82   262.3 2195.69   297.5 2199.22
   348.3 2197.57   407.3 2199.47   424.2 2196.85   453.7 2197.05   466.4  2194.9
     479 2194.96   538.1  2194.7   563.4 2195.76   567.6 2197.65   580.3 2199.13
   644.3 2194.56   660.4 2196.97   668.8 2203.16   685.7 2219.92   697.2  2229.1
     711 2236.95   723.4 2241.87   736.3  2250.5   753.2  2258.1     788 2278.42
#Mann= 5 ,-1,0
       0      .1       0     240     .06       0  372.05      .1       0
     479    .045       0   538.1      .1       0
Bank Sta=479,538.1
XS Rating Curve= 0 ,0
Exp/Cntr=0.3,0.1

Type RM Length L Ch R = 1 ,12837   ,199.7,198.9,198.4
XS GIS Cut Line= 3
 2371740.3901026723186.5351126282371529.80056243722924.504536306
 2371471.0476619722639.133305151
#Sta/Elev= 30
       0 2243.99    27.4 2229.19    47.9  2216.4    58.2 2211.91    78.7 2199.89
    83.6 2198.01      89 2197.16   106.4 2197.05   145.4 2198.67   191.6 2198.41
   237.3  2196.3   255.8 2194.22   289.1 2198.36   328.3 2198.82   347.7 2196.99
   372.2 2196.09   376.3 2195.45   384.6 2191.89   396.7 2191.25     409 2191.15
   437.6 2191.63   449.8 2192.03     458 2194.57   474.3 2205.42   498.8 2224.62
   535.6 2250.17   592.8 2281.89   601.1 2287.84   614.7 2295.52   627.5 2305.05
#Mann= 5 ,-1,0
       0      .1       0      70     .06       0     220      .1       0
   396.7    .045       0   437.6      .1       0
Bank Sta=396.7,437.6
XS Rating Curve= 0 ,0
Exp/Cntr(USF)=0,0
Exp/Cntr=0.3,0.1

Type RM Length L Ch R = 1 ,12638   ,290.6,295,298.3
XS GIS Cut Line= 3
2371860.85980033723189.3783011382371733.25519968722929.951432087
     2371668.679722626.098980379
#Sta/Elev= 30
       0 2269.74    18.1 2260.24    54.4 2236.08    67.1 2229.38    98.3 2208.88
   120.6 2197.17   129.1 2195.91   156.2 2195.64   187.4 2198.36     210 2197.16
   224.8 2198.73   260.6 2198.61   275.6 2194.56   302.2 2192.45   314.4 2195.66
   330.8 2196.71     339 2195.38   351.2 2191.47   367.6 2190.41   408.7 2190.34
   416.7 2190.44     433 2190.61   437.1 2191.15   441.2 2193.27   465.7 2212.95
   494.4 2230.57   514.8 2245.39     568 2278.08   580.7 2284.42   599.7 2295.82
#Mann= 5 ,-1,0
       0      .1       0     170     .06       0     280      .1       0
   367.6    .045       0   416.7      .1       0
Bank Sta=367.6,416.7
XS Rating Curve= 0 ,0
Exp/Cntr=0.3,0.1

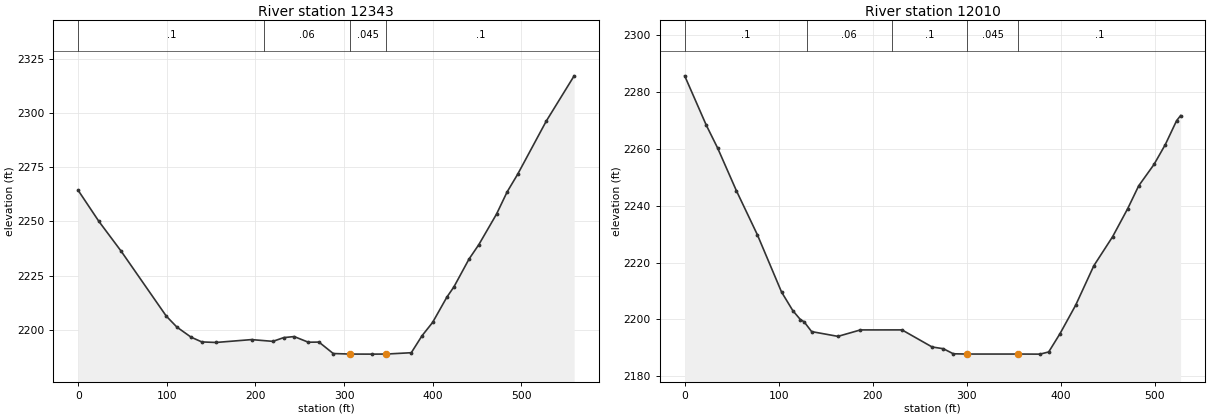
Type RM Length L Ch R = 1 ,12343   ,331.9,332.6,333
XS GIS Cut Line= 2
2372026.09309036723152.4213230452371991.97930077722593.808018622
#Sta/Elev= 30
       0 2264.26    23.3    2250    48.4 2236.26    99.4 2206.28   111.4 2201.21
   127.5 2196.54   139.5 2194.38   155.5 2194.13   195.6 2195.45   219.7 2194.64
   231.9 2196.37   243.7 2196.85   259.7 2194.24   271.7 2194.31   287.8 2189.03
     307 2188.78   331.9 2188.75   347.9 2188.79   375.9  2189.4     388 2197.22
     400  2203.4     416    2215     424 2219.76     441 2232.57   452.1 2239.24
   472.1 2253.34   484.1  2263.6   495.9 2271.67   528.2  2296.2   559.7  2317.1
#Mann= 4 ,-1,0
       0      .1       0     210     .06       0     307    .045       0
   347.9      .1       0
Bank Sta=307,347.9
XS Rating Curve= 0 ,0
Exp/Cntr(USF)=0,0
Exp/Cntr=0.3,0.1

Type RM Length L Ch R = 1 ,12010   ,127.5,127.7,127.9
XS GIS Cut Line= 2
2372343.10113488723164.2074248182372335.19663553722636.857763046
#Sta/Elev= 30
       0 2285.71      23 2268.32      35 2260.32      55 2245.27    77.3 2229.77
     103 2209.62     115 2203.06     123 2199.93     127 2199.13     135 2195.68
     163    2194   186.9 2196.27   231.1 2196.28   263.1 2190.27   275.1 2189.65
   285.7 2187.87   300.2 2187.78   354.9 2187.78   377.8 2187.75   387.1 2188.51
   399.1 2194.94   415.8 2204.99   435.1 2218.86     455 2229.04   471.2 2239.01
   482.8 2246.99   499.1 2254.52   511.1  2261.5   523.1 2269.91   527.4 2271.73
#Mann= 5 ,-1,0
       0      .1       0     130     .06       0     220      .1       0
   300.2    .045       0   354.9      .1       0
Bank Sta=300.2,354.9
XS Rating Curve= 0 ,0
Exp/Cntr=0.3,0.1