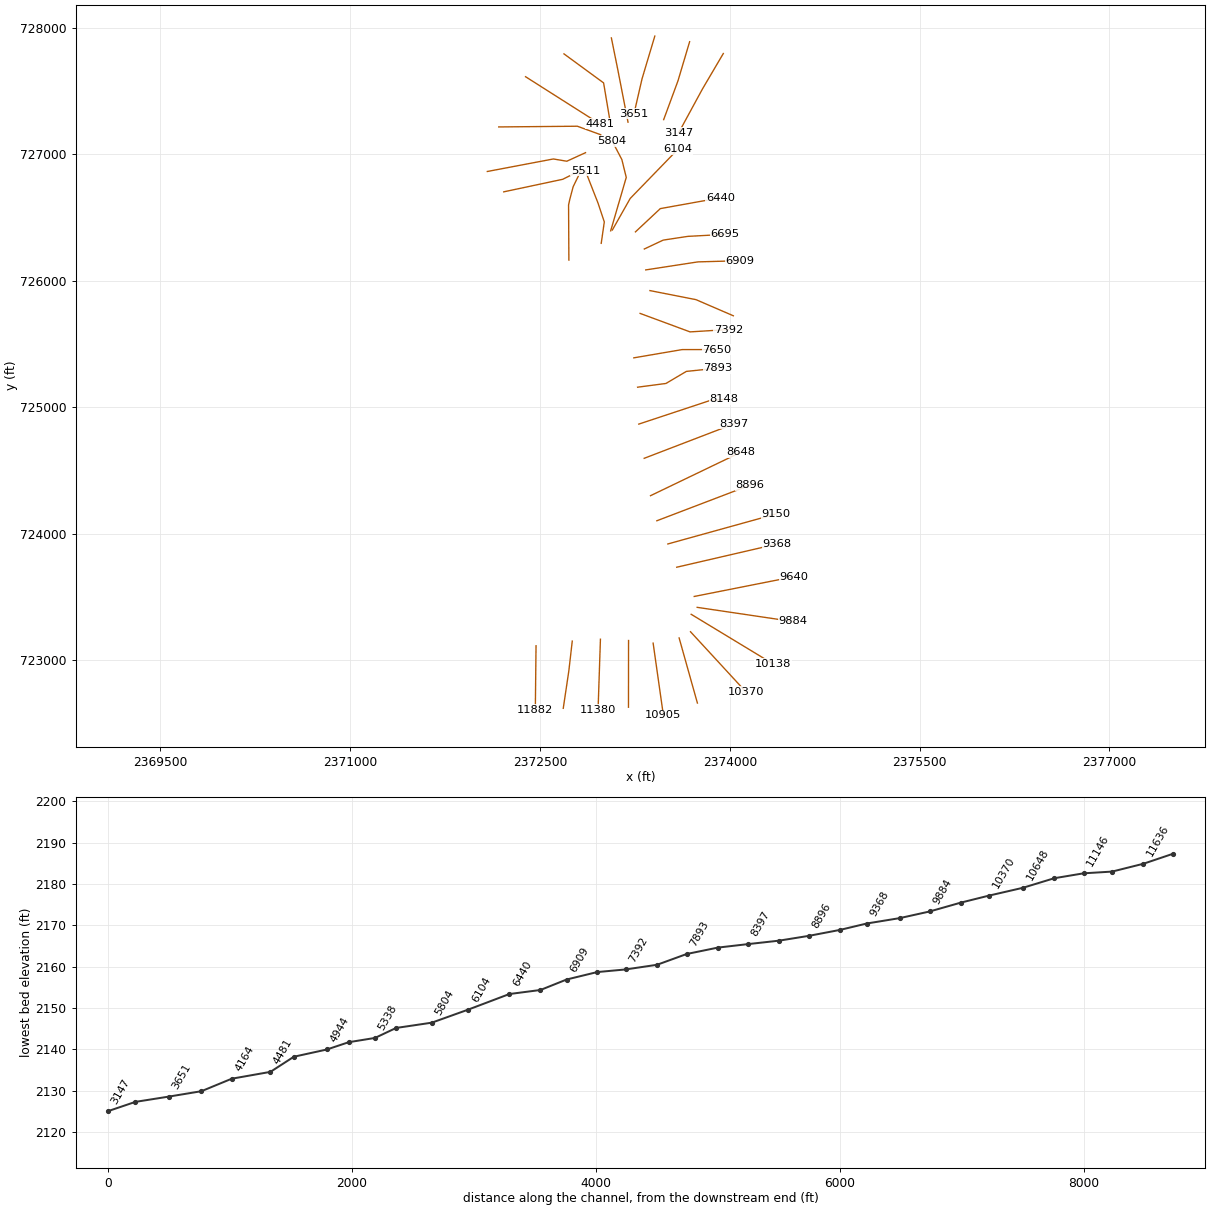
HEC-RAS study GLADYFK.prj: GLADYFK

--- GLADYFK.g01 (geometry) --- (continued)

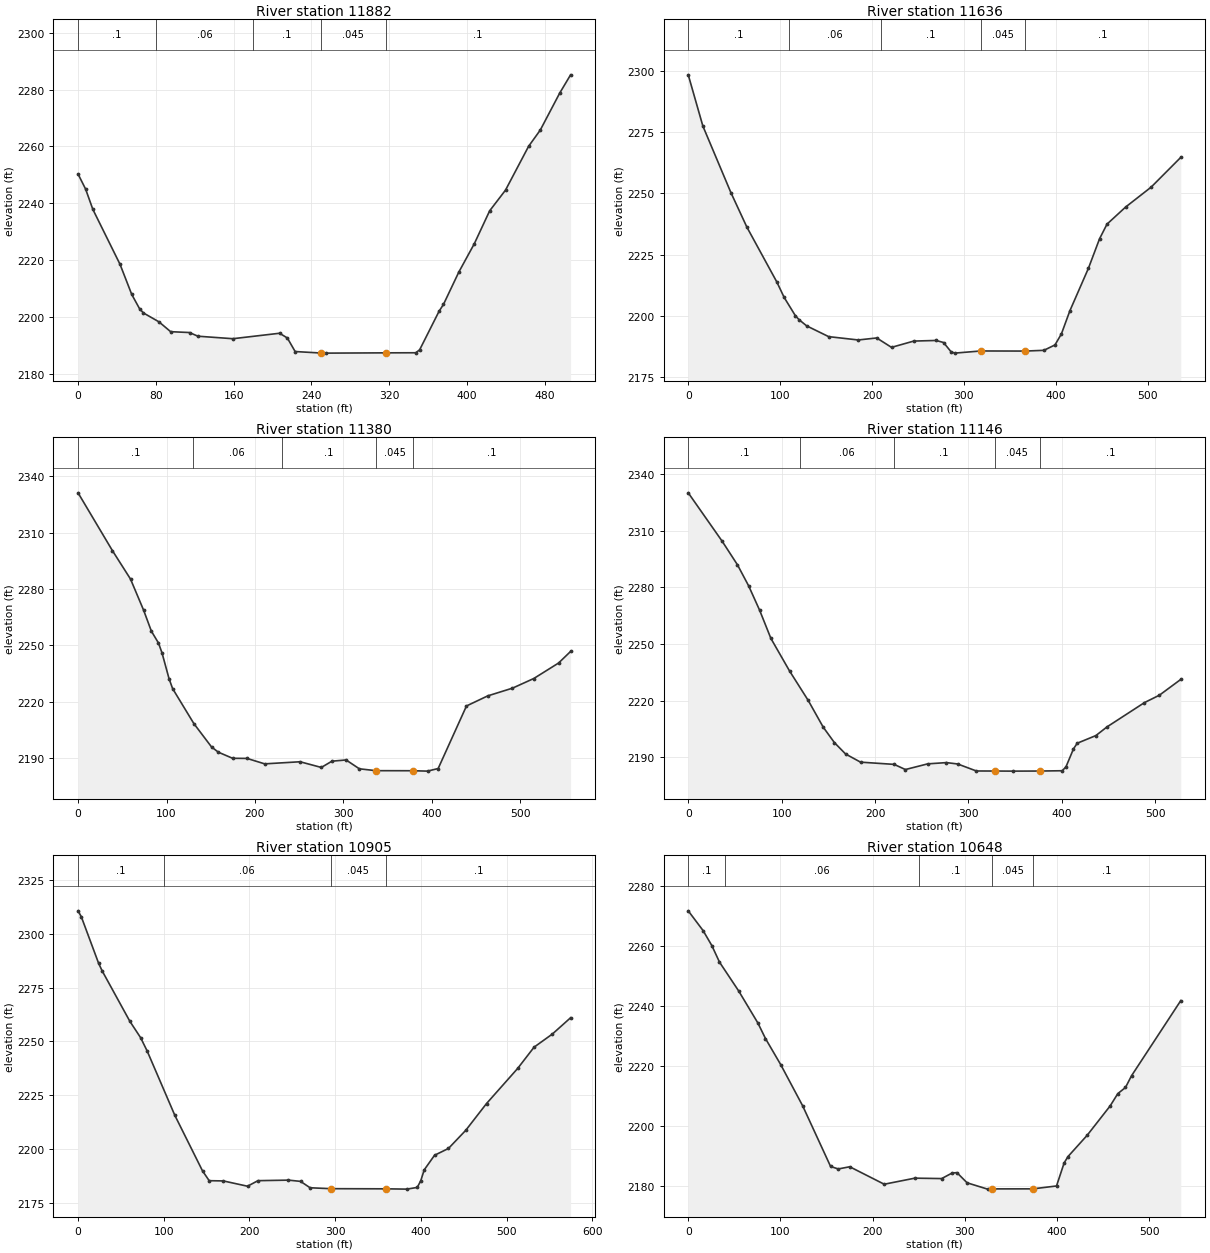
Type RM Length L Ch R = 1 ,11882   ,251.8,246.3,243.9
XS GIS Cut Line= 2
2372468.81033816723116.3946027112372463.21482383 722610.00055527
#Sta/Elev= 30
       0  2250.3     7.8 2244.99    15.2 2237.89    43.2 2218.53    55.2 2207.97
    63.2 2202.97    67.2 2201.46    83.2 2198.33    95.2 2194.87   114.6 2194.57
   123.2 2193.28   159.2  2192.4   207.2 2194.32   215.2 2192.65   223.2 2187.89
   249.4 2187.37   255.2 2187.33   316.4 2187.43   347.2 2187.46   351.2 2188.49
   371.2 2202.07   375.7 2204.46   391.5 2215.84   407.4 2225.79   423.2 2237.37
   439.5 2244.65   463.2 2260.03   475.2 2265.74   495.2 2278.75   506.4 2285.18
#Mann= 5 ,-1,0
       0      .1       0      80     .06       0     180      .1       0
   249.4    .045       0   316.4      .1       0
Bank Sta=249.4,316.4
XS Rating Curve= 0 ,0
Exp/Cntr(USF)=0,0
Exp/Cntr=0.3,0.1

Type RM Length L Ch R = 1 ,11636   ,251.2,256,257
XS GIS Cut Line= 3
     2372755.121723152.9443853372372728.16014837 722918.43072064
2372683.92919076722621.744674428
#Sta/Elev= 30
       0 2298.27    15.9 2277.42    46.4  2250.3    63.8 2236.23    96.4 2213.87
   104.4 2207.56   116.5 2200.18   120.6 2198.51   128.8    2196   152.8  2191.6
     185 2190.24   205.1 2191.06   221.2 2187.23   245.4 2189.79   269.7 2190.04
   277.8 2189.21   285.9 2185.48   289.9 2184.88   318.4 2185.76   366.7 2185.72
     387 2186.02   399.1 2188.22   406.1 2192.72   415.3 2202.13   435.5 2219.45
   447.6 2231.47   455.7 2237.43   475.9 2244.38   503.7  2252.5     536 2264.64
#Mann= 5 ,-1,0
       0      .1       0     110     .06       0     210      .1       0
   318.4    .045       0   366.7      .1       0
Bank Sta=318.4,366.7
XS Rating Curve= 0 ,0
Exp/Cntr=0.3,0.1

Type RM Length L Ch R = 1 ,11380   ,233.2,234.1,234.8
XS GIS Cut Line= 2
2372977.80636226723168.042401073 2372959.1546478722611.599586512
#Sta/Elev= 30
       0 2331.21    38.9 2300.39    59.3 2285.29    74.1 2268.73    82.9 2257.53
    90.9 2251.24    94.9    2246   102.9 2232.17   106.9 2226.95   130.9 2208.33
   150.9 2195.87   158.6 2193.08   174.7 2189.83     191 2189.76     211 2186.86
     251 2187.98     275 2184.95     287 2188.28     303 2188.94     318 2184.23
   336.7 2183.23   379.1  2183.2   395.1 2182.99   407.1 2184.38   439.1 2217.69
   463.1 2223.06   491.1 2227.18   515.2 2232.32   543.2 2240.56   556.8 2246.73
#Mann= 5 ,-1,0
       0      .1       0     130     .06       0     230      .1       0
   336.7    .045       0   379.1      .1       0
Bank Sta=336.7,379.1
XS Rating Curve= 0 ,0
Exp/Cntr(USF)=0,0
Exp/Cntr=0.3,0.1

Type RM Length L Ch R = 1 ,11146   ,236.7,241,245.3
XS GIS Cut Line= 2
2373200.07104239723157.712342946 2373199.4809788722630.282897845
#Sta/Elev= 30
       0 2330.16    36.5 2304.36    52.7 2291.99    64.7  2280.8    76.5 2267.83
    88.5 2252.95   108.5 2235.67   128.5 2220.03   144.5 2205.91   156.5  2197.7
   168.5 2191.65   184.5 2187.33   220.5 2186.15   232.5 2183.41   256.5 2186.43
   276.5 2187.09   288.5 2186.36   308.5 2182.65   328.1 2182.62     348 2182.57
   376.5 2182.62   400.5 2182.78   404.5 2184.88   412.5 2194.37   416.5 2197.36
   436.5 2201.43   448.5 2206.06   488.5 2218.91   504.5 2222.84   527.4 2231.21
#Mann= 5 ,-1,0
       0      .1       0     120     .06       0     220      .1       0
   328.1    .045       0   376.5      .1       0
Bank Sta=328.1,376.5
XS Rating Curve= 0 ,0
Exp/Cntr=0.3,0.1

Type RM Length L Ch R = 1 ,10905   ,254.2,256.5,259
XS GIS Cut Line= 2
2373394.36131841723136.9562103152373475.18541438722568.078919451
#Sta/Elev= 30
       0 2310.69     3.8 2307.95      24 2286.31    28.1 2282.81    60.4 2259.39
      73 2251.74    80.6 2245.59   112.9 2215.68   145.2 2189.86     153  2185.3
   169.5 2185.19   197.7 2182.73   209.9 2185.31   245.5 2185.56   259.6 2184.98
   270.7 2182.01   294.7 2181.59   359.4 2181.52   383.5 2181.38   395.7 2182.17
   399.8 2185.26   403.8 2190.31   415.9 2197.12   432.1 2200.27   452.3 2208.71
   476.5 2221.13   512.9 2237.48     532 2247.34   553.3 2253.43   574.6 2261.01
#Mann= 4 ,-1,0
       0      .1       0     100     .06       0   294.7    .045       0
   359.4      .1       0
Bank Sta=294.7,359.4
XS Rating Curve= 0 ,0
Exp/Cntr(USF)=0,0
Exp/Cntr=0.3,0.1

Type RM Length L Ch R = 1 ,10648   ,267.8,278.3,289.6
XS GIS Cut Line= 2
2373599.81374195723177.8215144832373744.24548226722663.405052393
#Sta/Elev= 30
       0 2271.65    16.1 2265.08    25.6 2260.09    33.9 2254.59    54.7    2245
    75.5 2234.36    83.8 2229.16   100.4 2220.44   124.1 2206.79   154.4 2186.62
   162.7 2185.78   175.2 2186.51   212.6  2180.7   245.8 2182.72   274.9 2182.58
   286.3 2184.44   291.5 2184.55   302.5 2181.17   324.7 2179.07   329.7 2179.15
   373.9 2179.16   399.5 2180.12   407.8 2187.82     412 2189.92   432.8    2197
   457.7 2206.76     466 2210.85   474.3 2212.88   480.9  2216.8   534.3 2241.79
#Mann= 5 ,-1,0
       0      .1       0      40     .06       0     250      .1       0
   329.7    .045       0   373.9      .1       0
Bank Sta=329.7,373.9
XS Rating Curve= 0 ,0
Exp/Cntr=0.3,0.1

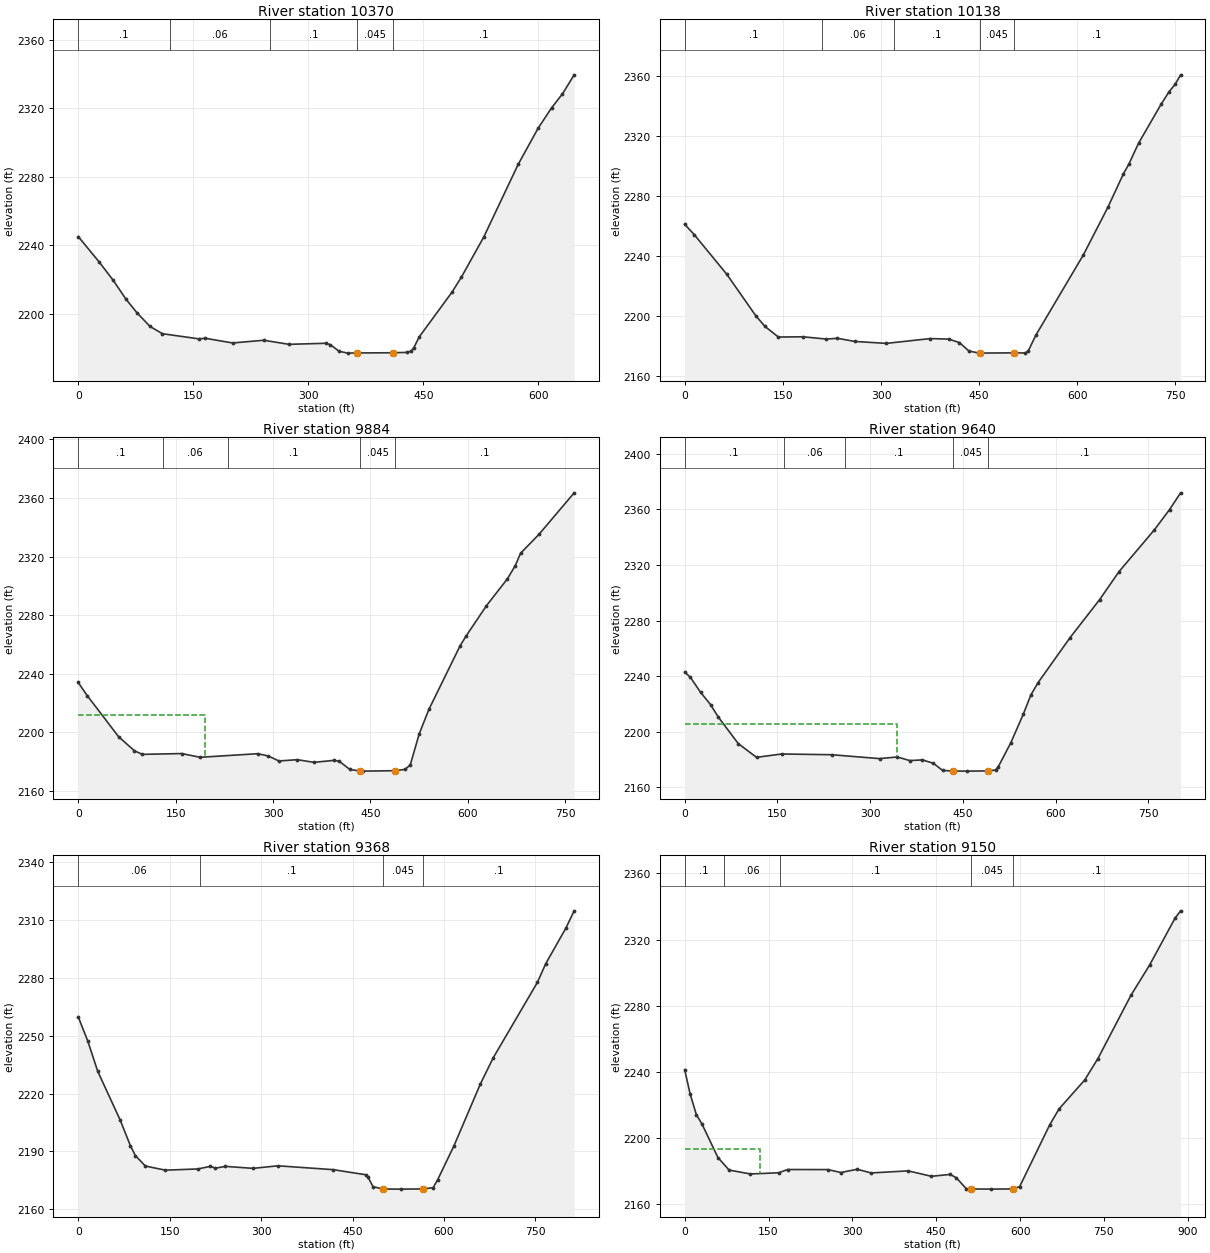
Type RM Length L Ch R = 1 ,10370   ,225.7,231.6,239.5
XS GIS Cut Line= 2
2373689.68013061723227.1061635122374127.99542029722751.487444921
#Sta/Elev= 30
       0 2245.16    27.3 2230.34    45.6 2219.67    62.5  2208.5    76.7 2200.68
    93.7 2192.72   109.9 2188.49   157.1 2185.52   165.8 2185.84   201.3 2183.11
     242 2184.68   274.9 2182.31     323 2182.92     329 2182.08   340.1 2178.31
   351.3 2177.18   363.7 2177.28   410.8  2177.4   428.7 2177.61   434.6 2178.48
   437.8 2180.43   444.7 2186.63   487.2 2212.54   499.5 2221.29     529 2244.96
   573.8 2287.24   599.8  2308.3   617.5 2320.26   631.6 2328.34   646.8 2339.43
#Mann= 5 ,-1,0
       0      .1       0     120     .06       0     250      .1       0
   363.7    .045       0   410.8      .1       0
Bank Sta=363.7,410.8
XS Rating Curve= 0 ,0
Exp/Cntr(USF)=0,0
Exp/Cntr=0.3,0.1

Type RM Length L Ch R = 1 ,10138   ,245.6,254.1,266.3
XS GIS Cut Line= 2
     2373695.118      723364.8232374343.29797448722972.068394272
#Sta/Elev= 30
       0 2261.26    14.8 2254.27    64.6 2227.83   108.8 2200.28   122.8 2193.22
   143.2 2186.19   181.1 2186.36   216.4 2184.83   233.5 2185.35   259.7 2183.27
   308.1 2181.96   375.4 2185.17   403.5 2184.81   419.9 2182.49   434.4 2176.88
   450.2 2175.48   451.9 2175.51   502.7 2175.66   520.4 2175.59   525.1 2176.94
   536.4 2187.25   609.2  2240.8   646.7 2272.53     670 2294.41   678.6 2301.14
   693.6 2315.19   728.6 2341.54   740.2 2349.44   749.6 2354.52   757.9 2360.73
#Mann= 5 ,-1,0
       0      .1       0     210     .06       0     320      .1       0
   451.9    .045       0   502.7      .1       0
Bank Sta=451.9,502.7
XS Rating Curve= 0 ,0
Exp/Cntr=0.3,0.1

Type RM Length L Ch R = 1 ,9884    ,236.3,244.2,254.8
XS GIS Cut Line= 2
 2373742.5266549723419.840546209 2374497.9210903723307.930259482
#Sta/Elev= 30
       0 2233.96    13.8 2224.99    62.3 2196.82    86.6 2187.25    98.7 2184.81
   159.4 2185.35   187.7  2182.8   276.6 2185.27   292.8 2183.66     309  2180.3
   337.3 2181.16     363 2179.36   393.9  2180.7     402 2180.06   418.2 2174.51
   434.3 2173.38   438.4 2173.35   487.7 2173.65   503.1 2174.54   511.2 2177.52
     525 2198.77   539.9  2215.5     588 2259.01   596.9 2265.47   628.4  2286.3
   660.8 2304.76     673  2313.8     681 2322.19   709.3 2335.09   763.6 2363.54
#Mann= 5 ,-1,0
       0      .1       0     130     .06       0     230      .1       0
   434.3    .045       0   487.7      .1       0
#XS Ineff= 2 , 0
          195.36 2211.87
Permanent Ineff=
       F       F
Bank Sta=434.3,487.7
XS Rating Curve= 0 ,0
Exp/Cntr(USF)=0,0
Exp/Cntr=0.3,0.1

Type RM Length L Ch R = 1 ,9640    ,270.8,271.6,272.3
XS GIS Cut Line= 2
     2373719.037       723505.812374505.80940755723661.537210417
#Sta/Elev= 30
       0 2243.03     9.3 2239.17    25.6  2228.5    41.9 2219.54    54.2 2210.75
    86.8 2191.48   116.2 2181.67     157 2184.08   237.7 2183.55   315.1 2180.75
   343.7 2181.92   364.1 2179.34   384.5 2179.82   402.1 2177.42   417.1 2172.24
   433.4 2171.81   456.5 2171.75   491.2 2171.93   502.7 2172.59   506.8 2174.62
   527.2 2191.97   547.6 2212.71   559.8 2226.51   571.6 2235.47   623.3 2267.79
     671 2295.08   702.5 2315.29   759.6 2345.29   784.1 2359.85     802 2371.88
#Mann= 5 ,-1,0
       0      .1       0     160     .06       0     260      .1       0
   433.4    .045       0   491.2      .1       0
#XS Ineff= 2 , 0
          342.57 2205.59
Permanent Ineff=
       F       F
Bank Sta=433.4,491.2
XS Rating Curve= 0 ,0
Exp/Cntr=0.3,0.1

Type RM Length L Ch R = 1 ,9368    ,217.6,218.6,220.3
XS GIS Cut Line= 2
2373580.87846296723736.9196919372374373.57632727723920.328217406
#Sta/Elev= 30
       0 2259.88    15.7 2247.26    32.1 2231.52    69.1 2206.11    85.5 2193.07
    93.7 2187.87   110.1 2182.44   142.9 2180.28   196.4 2180.91   216.9 2182.27
   225.1 2181.31   241.5 2182.24   286.7 2181.22   327.7 2182.54   418.1 2180.55
   471.4 2177.92   475.5 2176.59   483.7 2171.71   500.2 2170.49   529.8 2170.44
   564.9 2170.54   582.3  2171.2   589.8 2175.41   616.5 2192.95   659.8 2225.06
   680.8 2238.58   753.2 2277.67     767 2287.45   799.9 2305.82   813.6 2314.86
#Mann= 4 ,-1,0
       0     .06       0     200      .1       0   500.2    .045       0
   564.9      .1       0
Bank Sta=500.2,564.9
XS Rating Curve= 0 ,0
Exp/Cntr(USF)=0,0
Exp/Cntr=0.3,0.1

Type RM Length L Ch R = 1 ,9150    ,251.2,253.8,257.7
XS GIS Cut Line= 2
2373510.79152604723920.8044341152374365.71540755724157.823986719
#Sta/Elev= 30
       0  2241.2     9.7  2226.6    20.9 2213.95    30.5 2208.62    59.5 2188.03
    79.4 2180.45   117.7 2178.07     168  2178.8   184.1 2180.77   255.9 2180.73
   279.5 2178.96   308.6 2180.93   333.5  2178.7   399.9 2179.95   441.4 2176.66
   474.6  2177.8   485.7 2175.87   503.7  2169.2     512 2169.02   547.4  2168.9
   586.7 2169.03   599.2 2170.42   653.1 2207.85   669.7 2217.45   715.4 2234.87
   739.2 2247.89   798.4 2286.27   831.6 2304.47   877.3 2332.97   887.2 2337.36
#Mann= 5 ,-1,0
       0      .1       0      70     .06       0     170      .1       0
     512    .045       0   586.7      .1       0
#XS Ineff= 2 , 0
          133.97 2193.47
Permanent Ineff=
       F       F
Bank Sta=512,586.7
XS Rating Curve= 0 ,0
Exp/Cntr=0.3,0.1

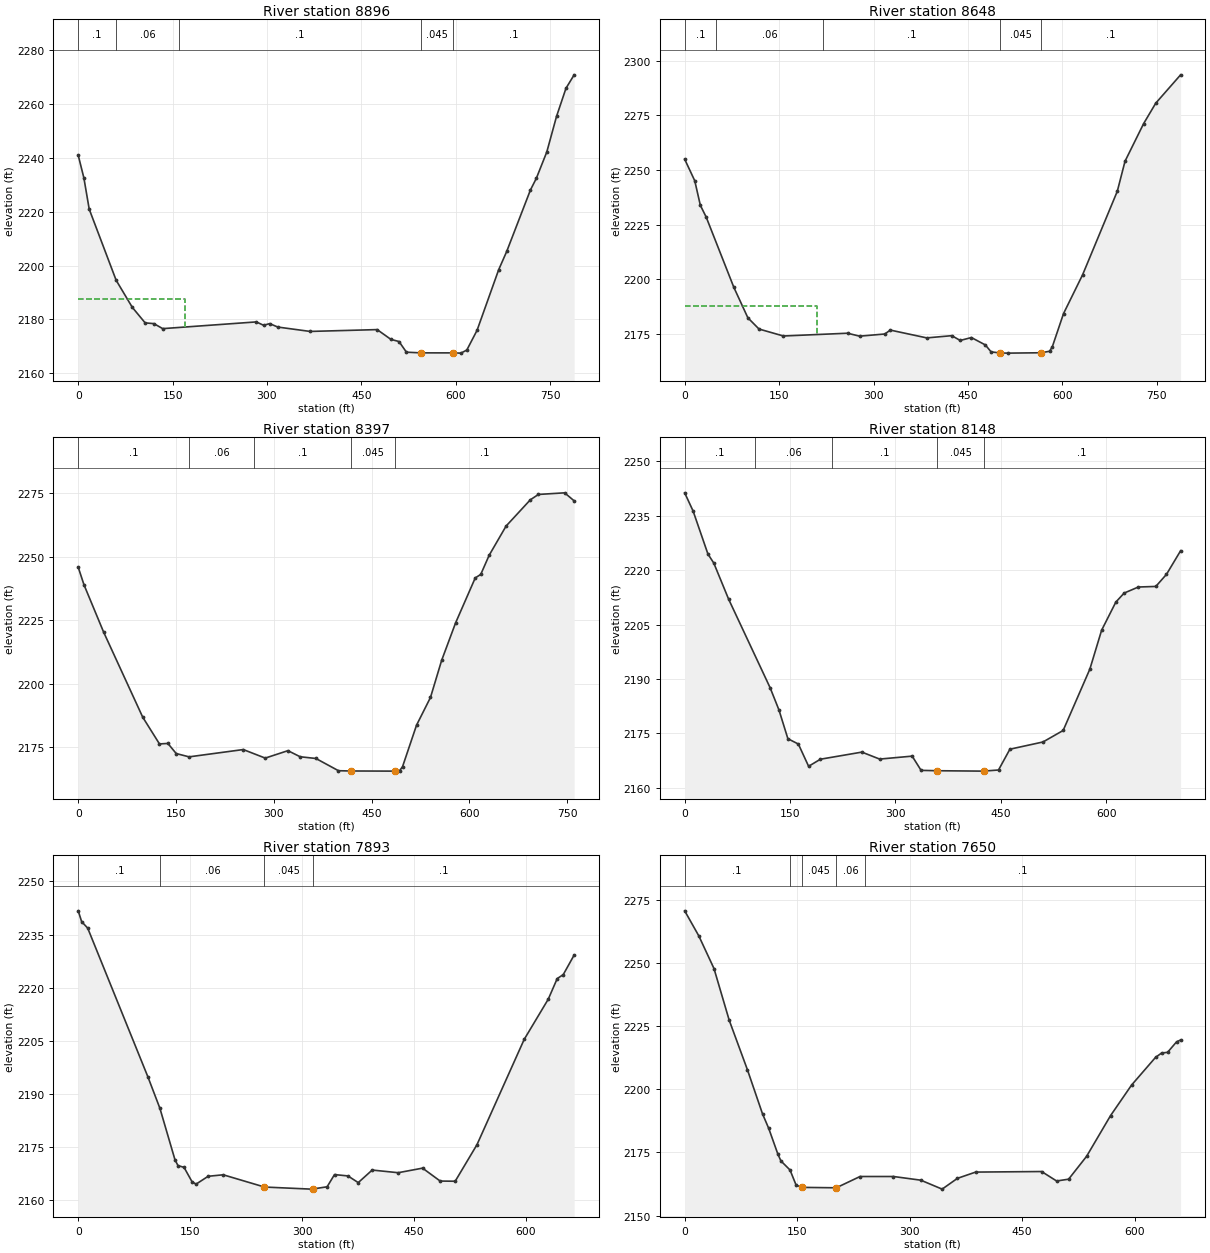
Type RM Length L Ch R = 1 ,8896    ,246.1,248.1,250.7
XS GIS Cut Line= 2
2373423.80148314724104.1777721632374160.31105766724385.184502135
#Sta/Elev= 30
       0 2240.99       9 2232.58    17.5 2220.95    60.3 2194.54      86 2184.47
   106.4 2178.71   120.3 2178.43   134.3 2176.57   283.1 2179.07   294.6 2177.82
   304.4 2178.43   317.2 2177.16   368.6 2175.53   475.2 2176.21     497 2172.58
   509.9 2171.78   521.7 2167.82   544.1 2167.57   595.5 2167.56   608.3 2167.47
   617.7 2168.62     634 2175.96   668.3 2198.44   681.1 2205.25   718.8 2228.08
   728.2 2232.42   744.8  2242.2   760.3 2255.43   775.3 2265.87   788.3 2270.87
#Mann= 5 ,-1,0
       0      .1       0      60     .06       0     160      .1       0
   544.1    .045       0   595.5      .1       0
#XS Ineff= 2 , 0
          170.49 2187.74
Permanent Ineff=
       F       F
Bank Sta=544.1,595.5
XS Rating Curve= 0 ,0
Exp/Cntr(USF)=0,0
Exp/Cntr=0.3,0.1

Type RM Length L Ch R = 1 ,8648    ,254,250.9,248.5
XS GIS Cut Line= 2
2373373.73269772724302.3515874322374083.72594341724643.915905631
#Sta/Elev= 30
       0 2254.92      16 2245.07    24.9 2233.84    34.2 2228.44    78.2 2196.29
   100.4 2182.43   118.1  2177.3   156.8 2174.12   258.7 2175.39   277.9 2174.04
   317.9 2175.03   326.7 2176.82   384.6 2173.25   424.4 2174.27   437.7 2172.08
   455.5 2173.41   477.7 2170.03   486.8 2166.87   501.5 2166.34   513.4 2166.29
   566.4 2166.46   579.8 2167.15   584.2 2169.31   601.9 2184.38   632.2  2202.1
   687.3 2240.26   699.6 2254.01   729.2 2271.22   748.4 2280.53   787.9 2293.48
#Mann= 5 ,-1,0
       0      .1       0      50     .06       0     220      .1       0
   501.5    .045       0   566.4      .1       0
#XS Ineff= 2 , 0
          210.74 2187.79
Permanent Ineff=
       F       F
Bank Sta=501.5,566.4
XS Rating Curve= 0 ,0
Exp/Cntr(USF)=0,0
Exp/Cntr=0.3,0.1

Type RM Length L Ch R = 1 ,8397    ,251,248.9,247.9
XS GIS Cut Line= 2
2373323.84128045724597.8622896942374033.83452615724870.346183987
#Sta/Elev= 30
       0 2245.89     8.9 2238.93    38.9 2220.34    98.9 2186.76   124.6  2176.2
   137.5 2176.39   150.3  2172.4     170  2171.1   253.1 2173.98   286.8 2170.61
   321.6 2173.54   340.3 2171.14   364.5 2170.46   399.1 2165.63   417.7 2165.53
   485.8 2165.47   493.1 2165.71   497.4 2167.27   518.8 2183.59   540.2 2194.54
   557.3 2209.15   578.7 2223.94   608.8 2241.66   617.3 2243.07   630.2 2250.62
   656.1 2262.11   693.3 2272.48   705.7 2274.59   745.9 2275.23   760.5 2272.06
#Mann= 5 ,-1,0
       0      .1       0     170     .06       0     270      .1       0
   417.7    .045       0   485.8      .1       0
Bank Sta=417.7,485.8
XS Rating Curve= 0 ,0
Exp/Cntr(USF)=0,0
Exp/Cntr=0.3,0.1

Type RM Length L Ch R = 1 ,8148    ,245.6,255.7,259.8
XS GIS Cut Line= 3
2373280.74801858724868.1297009762373846.11542982725055.361765735
 2373956.2519385725062.704199648
#Sta/Elev= 30
       0 2241.29      12 2236.27    33.1 2224.43    41.5 2221.91    62.6 2211.97
   121.6  2187.6   134.2 2181.47   146.9 2173.55   161.8 2172.08   176.4 2165.95
   193.2  2167.9   252.2 2169.86   277.5 2167.94   323.8 2168.75   336.5 2164.83
   359.6 2164.73     425 2164.62   425.8 2164.63   446.7 2164.93   462.9 2170.66
     510 2172.65   538.7 2175.82   576.7 2192.72   593.5 2203.46   613.7 2211.19
   625.5 2213.67   645.7 2215.34   670.6  2215.5   685.8 2218.84   705.9 2225.34
#Mann= 5 ,-1,0
       0      .1       0     100     .06       0     210      .1       0
   359.6    .045       0   425.8      .1       0
Bank Sta=359.6,425.8
XS Rating Curve= 0 ,0
Exp/Cntr(USF)=0,0
Exp/Cntr=0.3,0.1

Type RM Length L Ch R = 1 ,7893    ,251.5,242.3,236.6
XS GIS Cut Line= 4
2373271.56997619725159.9914489832373495.51421051725189.361184632
2373657.04775658 725284.812825492373906.69050959725310.511344182
#Sta/Elev= 30
       0 2241.71     4.6 2238.65    12.7 2236.83    93.4 2194.78   109.5 2185.88
   129.7 2171.33   133.7 2169.72   141.8 2169.22   152.5 2165.16   157.9 2164.48
   174.1  2166.7   194.3 2167.12   249.6 2163.66     312 2163.07   314.9 2163.13
   333.5 2163.73   343.4 2167.18   361.4  2166.8   375.2 2164.91   393.9 2168.46
   428.7 2167.71   461.4    2169     485 2165.35   505.1  2165.3   534.3 2175.63
   597.6  2205.4   629.8 2216.74   641.8 2222.56   649.9 2223.69   664.5 2229.22
#Mann= 4 ,-1,0
       0      .1       0     110     .06       0   249.6    .045       0
   314.9      .1       0
Bank Sta=249.6,314.9
XS Rating Curve= 0 ,0
Exp/Cntr(USF)=0,0
Exp/Cntr=0.3,0.1

Type RM Length L Ch R = 1 ,7650    ,273.1,258.1,249.7
XS GIS Cut Line= 3
2373241.64110767725391.9444734932373624.00125399725457.225474084
2373897.55973265725457.225474084
#Sta/Elev= 30
       0 2270.71    18.8 2260.81    39.1 2247.84    59.4 2227.37    83.7 2207.75
   103.8  2190.3   112.1 2184.53   124.3 2174.34   128.4 2171.63   140.5 2168.05
   148.7 2162.02   156.8 2161.16   202.2    2161   233.9 2165.47   278.5 2165.47
     315 2164.01   343.4 2160.47   363.8 2164.74   388.1 2167.22   476.1 2167.44
   496.1 2163.69   512.1 2164.41   536.1 2173.47     568 2189.57   596.1  2201.7
     628 2212.64   636.1 2214.38   644.1 2214.66   656.1 2218.82   661.5 2219.55
#Mann= 5 ,-1,0
       0      .1       0     140     .06       0   156.8    .045       0
   202.2     .06       0     240      .1       0
Bank Sta=156.8,202.2
XS Rating Curve= 0 ,0
Exp/Cntr(USF)=0,0
Exp/Cntr=0.3,0.1

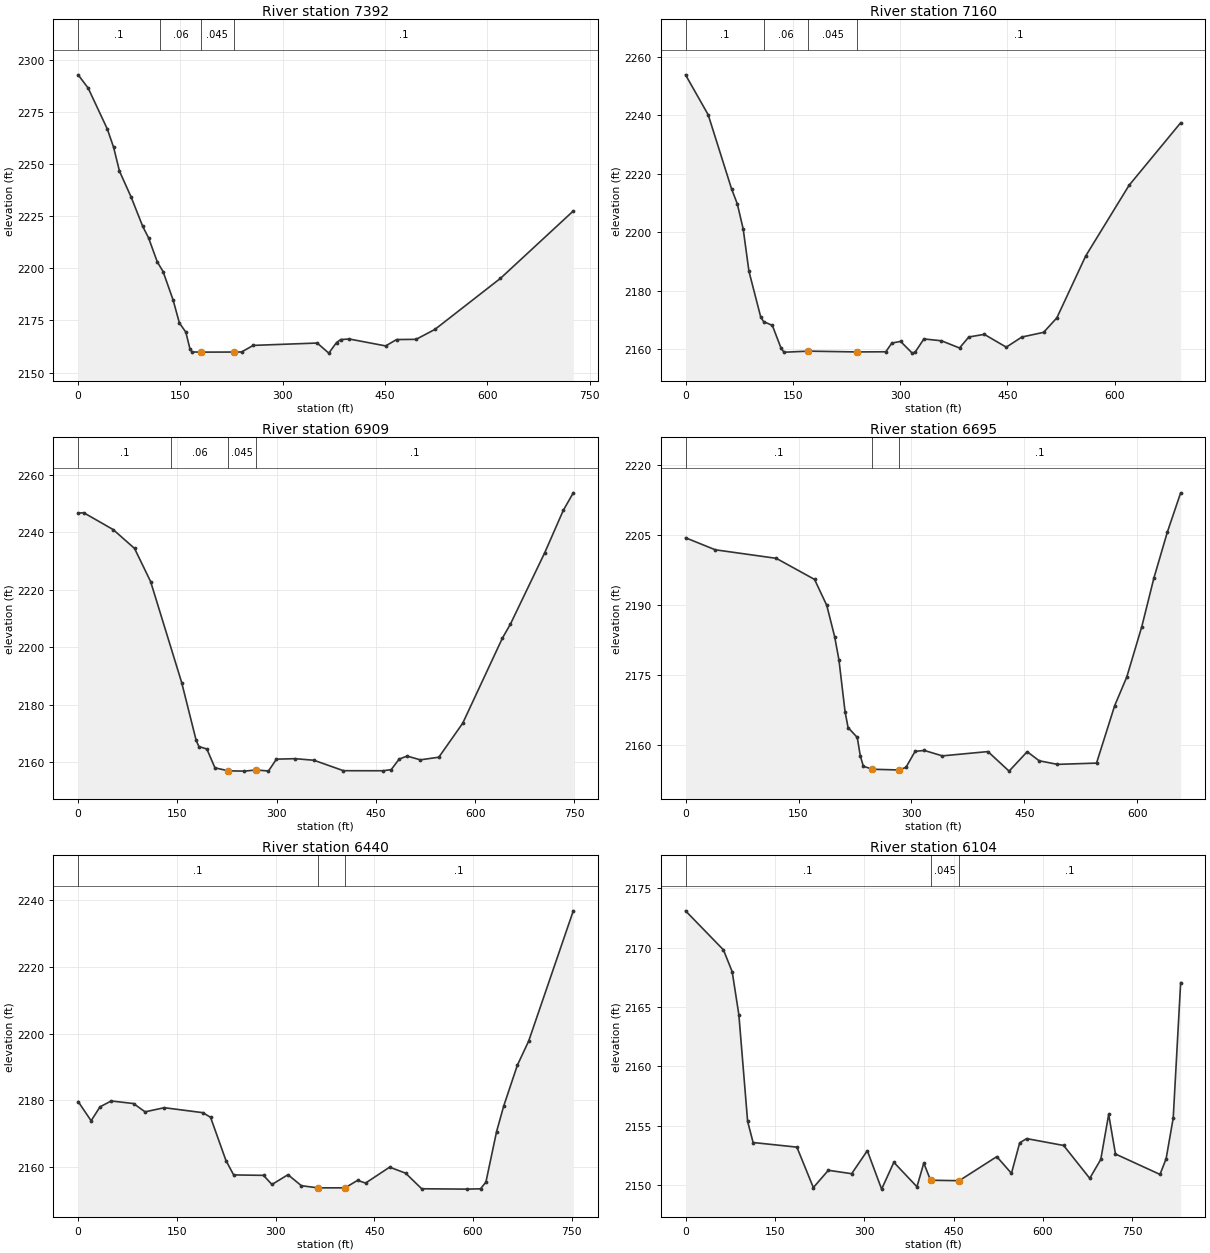
Type RM Length L Ch R = 1 ,7392    ,224.1,232.2,236.1
XS GIS Cut Line= 3
2373291.37901288725743.218429052 2373686.1736355725597.113332492
2373990.81830492725615.765046946
#Sta/Elev= 30
       0 2292.83    14.7 2286.44    42.7 2266.87      52 2258.04    60.6 2246.62
    77.6 2234.26    94.7 2220.12   103.2 2214.67     116 2203.13   124.5 2198.49
   139.2 2184.88   148.5 2173.77   157.9 2169.42   164.1 2161.19   167.2 2159.91
   179.7 2159.82   228.1 2159.86   239.7  2159.9   256.8 2163.05   350.6 2164.18
   367.6 2159.34   378.9  2164.4   385.1 2165.85   397.6 2166.12     451  2162.8
     467 2165.85   495.6 2165.95   523.2 2170.71   619.3 2195.19   726.2 2227.53
#Mann= 4 ,-1,0
       0      .1       0     120     .06       0   179.7    .045       0
   228.1      .1       0
Bank Sta=179.7,228.1
XS Rating Curve= 0 ,0
Exp/Cntr(USF)=0,0
Exp/Cntr=0.3,0.1

Type RM Length L Ch R = 1 ,7160    ,239.5,251,258
XS GIS Cut Line= 3
2373369.09448977725923.5183354452373732.80292164725852.020096703
2374028.12173383725724.566714598
#Sta/Elev= 30
       0 2253.87    31.7  2240.2    64.3 2214.92    72.4 2209.73    80.6 2201.17
    88.7 2186.65   105.1 2171.09   109.1 2169.51   121.4 2168.17   133.6 2160.38
   137.7 2159.02   171.6 2159.39   239.4 2159.12     280 2159.17   288.5 2162.16
   300.7 2162.71     317 2158.71   321.1 2159.07   333.3 2163.56   357.8 2162.93
   383.1 2160.47   396.1 2164.23   417.7 2165.13   448.5 2160.75   470.2 2164.21
   500.7 2165.82   519.2 2170.78   559.5 2191.92   620.1 2216.07   692.3 2237.47
#Mann= 4 ,-1,0
       0      .1       0     110     .06       0   171.6    .045       0
   239.4      .1       0
Bank Sta=171.6,239.4
XS Rating Curve= 0 ,0
Exp/Cntr(USF)=0,0
Exp/Cntr=0.3,0.1

Type RM Length L Ch R = 1 ,6909    ,215.1,214.2,214.1
XS GIS Cut Line= 3
2373335.92552424726086.9757436862373748.37088597 726150.42887626
2374079.23364868726159.493609485
#Sta/Elev= 30
       0 2246.63     8.3  2246.8    52.9 2240.93    85.2 2234.37   109.5 2222.83
   156.5 2187.67   178.3 2167.63   182.4 2165.47   194.5  2164.6   206.7 2158.06
   226.9 2157.02   251.2 2156.91   268.7 2157.31   287.6 2156.96   299.7 2161.08
   328.1 2161.24   356.4 2160.69   400.9 2157.06   461.1 2157.04   473.1 2157.44
   485.1 2161.09   497.1 2162.15   517.1 2160.84   545.1 2161.75   581.2 2173.59
   641.2 2203.19   653.2 2208.01   705.2 2232.91   733.2 2247.63   748.3 2253.71
#Mann= 4 ,-1,0
       0      .1       0     140     .06       0   226.9    .045       0
   268.7      .1       0
Bank Sta=226.9,268.7
XS Rating Curve= 0 ,0
Exp/Cntr(USF)=0,0
Exp/Cntr=0.3,0.1

Type RM Length L Ch R = 1 ,6695    ,254,255.2,255.8
XS GIS Cut Line= 4
2373324.59460771726252.4071250392373474.16270592726322.658807532
2373669.05447025726352.1191905132373963.65830006726367.982473657
#Sta/Elev= 30
       0  2204.4    39.5 2201.82   120.5 2199.99   171.3 2195.47   187.5 2189.91
     198  2183.2   203.7 2178.21   211.8 2167.14   215.8 2163.72     228  2161.6
     232 2157.69   236.1 2155.43   248.2 2154.78   283.8 2154.63   292.7  2155.2
   304.8 2158.62   317.1 2158.81     341 2157.65   401.5 2158.57   429.6 2154.38
   453.6 2158.54   469.6  2156.6   493.7 2155.83   545.7  2156.1   569.8 2168.42
   585.8 2174.53   605.8 2185.36   621.8 2195.72   639.7  2205.6   657.4 2214.03
#Mann= 3 ,-1,0
       0      .1       0   248.2    .045       0   283.8      .1       0
Bank Sta=248.2,283.8
XS Rating Curve= 0 ,0
Exp/Cntr(USF)=0,0
Exp/Cntr=0.3,0.1

Type RM Length L Ch R = 1 ,6440    ,327.4,335.9,351.9
XS GIS Cut Line= 3
2373254.64684564726387.7143173932373451.04939885726571.526963342
2373926.94789315726657.138332688
#Sta/Elev= 30
       0 2179.65    19.7 2173.89    33.2 2178.07    50.2 2179.83    84.1 2179.06
   101.7 2176.57   130.9 2177.81   189.5 2176.32   201.2 2174.93   224.6 2161.98
   236.3 2157.66   281.7 2157.53   294.5 2154.79   318.9 2157.73   339.2 2154.43
   364.4 2153.78   405.7 2153.79   424.6 2156.03   436.8 2155.22   473.4 2159.99
   497.7 2158.18   522.1 2153.51   591.2  2153.4   611.5  2153.5   619.7 2155.51
   635.9 2170.64   646.8 2178.35   667.5 2190.55   684.7  2197.8   752.5 2236.83
#Mann= 3 ,-1,0
       0      .1       0   364.4    .045       0   405.7      .1       0
Bank Sta=364.4,405.7
XS Rating Curve= 0 ,0
Exp/Cntr(USF)=0,0
Exp/Cntr=0.3,0.1

Type RM Length L Ch R = 1 ,6104    ,255,299.7,307.8
XS GIS Cut Line= 3
2373072.12646705726402.5054563482373213.13342833726651.785620032
2373592.29028856727042.675487403
#Sta/Elev= 30
       0 2173.11    63.6 2169.82    78.3 2167.98    89.5 2164.35   104.2 2155.36
   113.4 2153.58   186.9 2153.19   214.5 2149.78   239.7 2151.24   278.8 2150.95
   305.1 2152.89   329.1 2149.65   349.6 2151.91   388.4 2149.85   399.9 2151.85
   411.2  2150.4   459.3 2150.36   522.4 2152.39     547 2150.98   560.8 2153.55
   572.5 2153.91   634.6 2153.33   678.4 2150.56   696.9 2152.15   710.2 2155.95
   721.6 2152.61   796.3 2150.89   806.6 2152.21   818.5 2155.64     831 2167.06
#Mann= 3 ,-1,0
       0      .1       0   411.2    .045       0   459.3      .1       0
Bank Sta=411.2,459.3
XS Rating Curve= 0 ,0
Exp/Cntr(USF)=0,0
Exp/Cntr=0.3,0.1

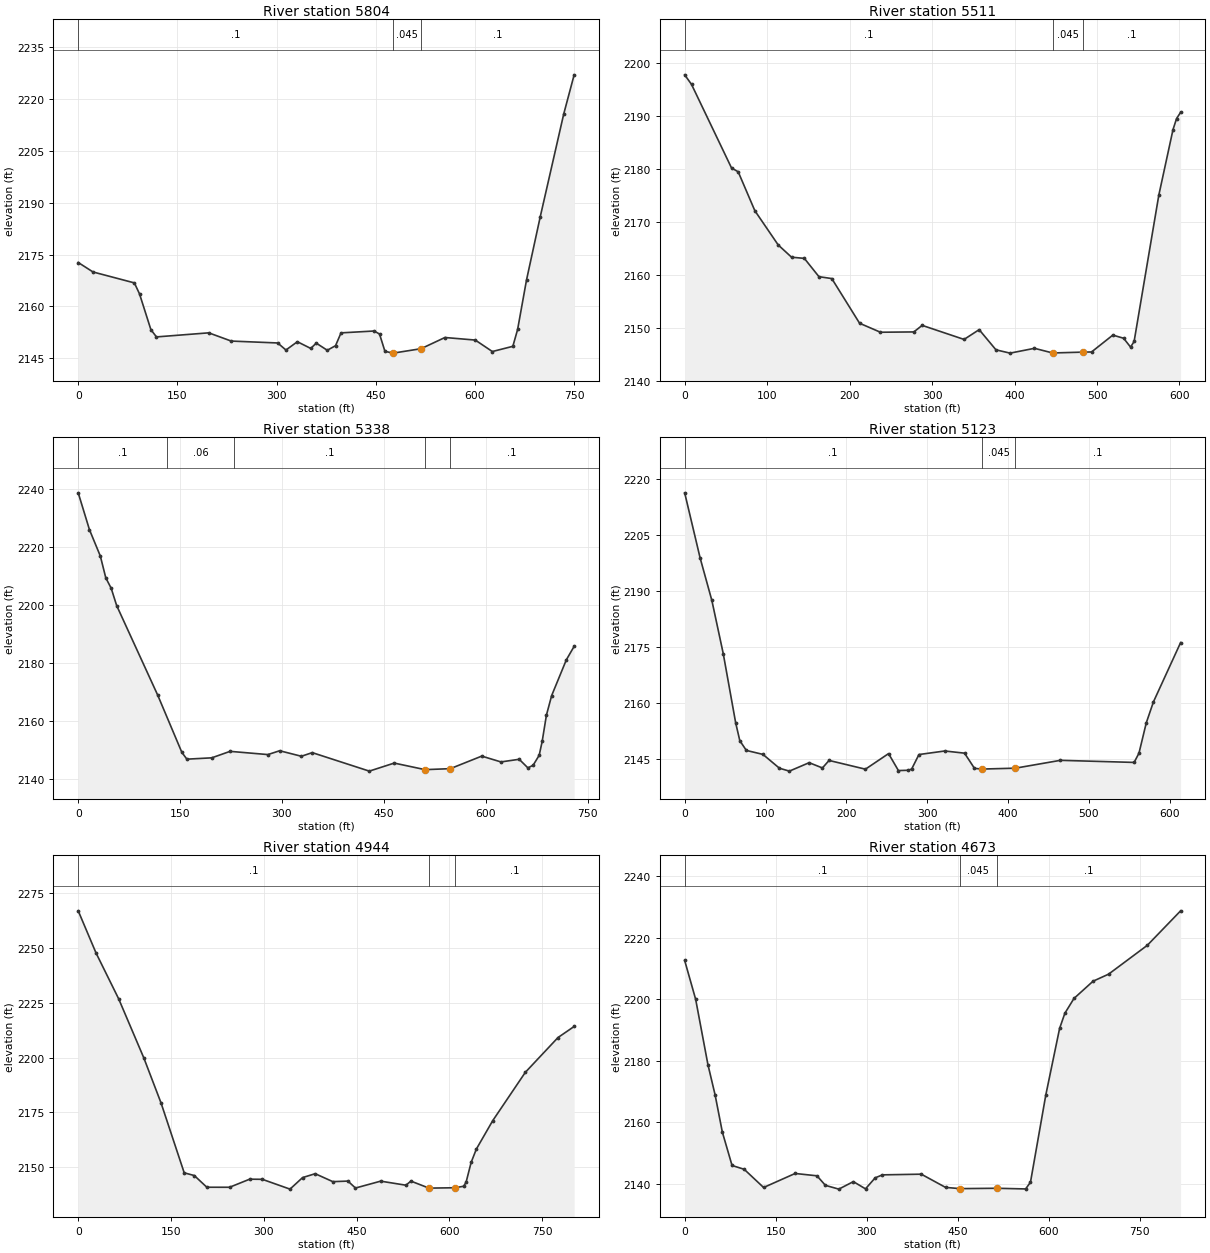
Type RM Length L Ch R = 1 ,5804    ,288.1,292.9,294.1
XS GIS Cut Line= 4
2373058.75302812726395.658176947 2373181.9788479726817.987377737
2373147.21185552726959.1087091392373070.62457691727104.792895862
#Sta/Elev= 30
       0  2172.7    22.4 2169.96    84.9  2166.8    92.7 2163.62   109.9 2153.27
   118.3 2151.17   197.4 2152.35   231.4 2149.97   301.6 2149.42   314.1 2147.38
   331.4 2149.78   351.6 2147.84   359.9 2149.37   376.6 2147.31   389.1 2148.63
   397.4 2152.34   447.4 2152.88   455.6 2152.01   463.8    2147   476.2 2146.48
   518.4 2147.76   554.5    2151   600.4 2150.26   626.2 2146.94   657.2 2148.45
   664.4 2153.32   677.9 2167.67   698.7 2185.99   734.2 2215.72   749.9    2227
#Mann= 3 ,-1,0
       0      .1       0   476.2    .045       0   518.4      .1       0
Bank Sta=476.2,518.4
XS Rating Curve= 0 ,0
Exp/Cntr(USF)=0,0
Exp/Cntr=0.3,0.1

Type RM Length L Ch R = 1 ,5511    ,182.5,172.9,160
XS GIS Cut Line= 4
2372984.04869665726296.9389983292373008.44841021 726466.22124457
2372959.07368325726614.4126319852372859.14766401726869.749178828
#Sta/Elev= 30
       0 2197.83     8.3 2196.02    56.8 2180.22    64.9 2179.49    85.1 2172.13
   113.4 2165.66   129.6 2163.34   145.1 2163.12   162.8 2159.66   178.4  2159.3
   212.1 2150.85   237.4 2149.15   277.9 2149.21     288 2150.45   338.8 2147.79
   357.1 2149.64   377.5 2145.82   394.6  2145.2   424.2 2146.11   446.2 2145.23
   482.9 2145.39   493.4 2145.42   519.2 2148.61   532.3 2148.01   540.7 2146.34
     545  2147.4     575 2175.11   592.2 2187.49   596.5 2189.56   601.4 2190.74
#Mann= 3 ,-1,0
       0      .1       0   446.2    .045       0   482.9      .1       0
Bank Sta=446.2,482.9
XS Rating Curve= 0 ,0
Exp/Cntr(USF)=0,0
Exp/Cntr=0.3,0.1

Type RM Length L Ch R = 1 ,5338    ,239,215.5,198.3
XS GIS Cut Line= 5
2372728.43536489726164.5504998542372725.97077755 726599.79199733
2372735.15435328726642.9662571682372762.28490127726744.714708697
2372826.03666807726875.535034283
#Sta/Elev= 30
       0 2238.65    16.6 2225.92    32.6 2216.85    40.6 2209.37    48.6 2205.75
    56.6 2199.82     117 2168.99   152.6 2149.25     160 2146.91   196.6 2147.37
   223.6  2149.6   279.3 2148.49   296.6 2149.81   328.6 2147.91   344.6 2149.16
   428.6 2142.79   465.3 2145.56   510.7  2143.3   547.9 2143.64   594.1 2147.96
   622.4 2145.96   649.3 2146.87   662.1 2143.91   669.8 2144.82   678.7 2148.24
   683.1    2153   689.4  2162.1   697.1 2168.82   718.7 2181.13   730.2 2185.78
#Mann= 5 ,-1,0
       0      .1       0     130     .06       0     230      .1       0
   510.7    .045       0   547.9      .1       0
Bank Sta=510.7,547.9
XS Rating Curve= 0 ,0
Exp/Cntr(USF)=0,0
Exp/Cntr=0.3,0.1

Type RM Length L Ch R = 1 ,5123    ,192.3,178.3,177.1
XS GIS Cut Line= 3
2372213.51488183726704.0415476532372679.39231355726803.164405468
2372802.32839387726863.993051081
#Sta/Elev= 30
       0 2216.25    19.1 2198.82    33.6 2187.46    47.7 2173.23    63.1 2154.67
    68.2 2149.91    76.3  2147.3    96.8 2146.24   117.2 2142.54   129.5 2141.76
     154 2144.02   170.4 2142.61   178.6 2144.62   223.6 2142.28   252.2 2146.45
   264.4 2141.91   276.7 2141.99   280.8 2142.33   289.8  2146.2   321.7 2147.15
   346.2 2146.57   358.5  2142.5   367.4 2142.31   409.1 2142.55   464.8 2144.65
     556 2144.09     562 2146.58     571 2154.67   579.9 2160.31   613.5 2176.17
#Mann= 3 ,-1,0
       0      .1       0   367.4    .045       0   409.1      .1       0
Bank Sta=367.4,409.1
XS Rating Curve= 0 ,0
Exp/Cntr(USF)=0,0
Exp/Cntr=0.3,0.1

Type RM Length L Ch R = 1 ,4944    ,268.5,270.8,275.3
XS GIS Cut Line= 4
2372083.88385005726865.0312340982372605.77304637 726963.95020219
2372712.01745132726946.0866829642372859.92639862727013.642546137
#Sta/Elev= 30
       0 2267.02    28.8 2247.78    65.4 2226.84   106.1 2199.84   133.9  2179.3
   171.3 2147.44   187.6  2146.2   207.9 2140.86   244.6 2140.85   277.1 2144.54
   297.5 2144.48   342.3    2140   362.6 2145.27     383 2147.04   411.5 2143.41
   435.9 2143.67   448.1  2140.5   488.8 2143.64   529.6 2141.79   537.7 2143.66
   566.9 2140.46   608.7 2140.63   622.9 2141.31   626.9 2143.18     635 2152.19
   643.5 2158.31   669.9 2171.25   722.6 2193.31   775.4 2209.19   801.5 2214.24
#Mann= 3 ,-1,0
       0      .1       0   566.9    .045       0   608.7      .1       0
Bank Sta=566.9,608.7
XS Rating Curve= 0 ,0
Exp/Cntr(USF)=0,0
Exp/Cntr=0.3,0.1

Type RM Length L Ch R = 1 ,4673    ,210,192.3,176.1
XS GIS Cut Line= 3
2372174.11718155727217.1187628632372795.21927289727222.714277199
2372979.87124599727155.568105163
#Sta/Elev= 30
       0 2212.59    18.1 2199.97    38.3 2178.76    50.1 2168.94    62.1 2156.79
    78.1 2145.94    98.1  2144.7   130.1 2138.78   182.1 2143.34   218.1 2142.58
     232 2139.48   254.1 2138.25   278.1 2140.69   298.1 2138.34   314.1 2141.93
   326.1 2142.89   390.1 2143.11   430.1 2138.81     454 2138.41   514.1 2138.53
   562.1 2138.31   570.1 2140.51   595.4 2168.91   618.1 2190.51   626.8 2195.45
   641.8 2200.25   673.2 2205.85   698.8 2208.14   762.6 2217.51   817.6 2228.74
#Mann= 3 ,-1,0
       0      .1       0     454    .045       0   514.1      .1       0
Bank Sta=454,514.1
XS Rating Curve= 0 ,0
Exp/Cntr(USF)=0,0
Exp/Cntr=0.3,0.1

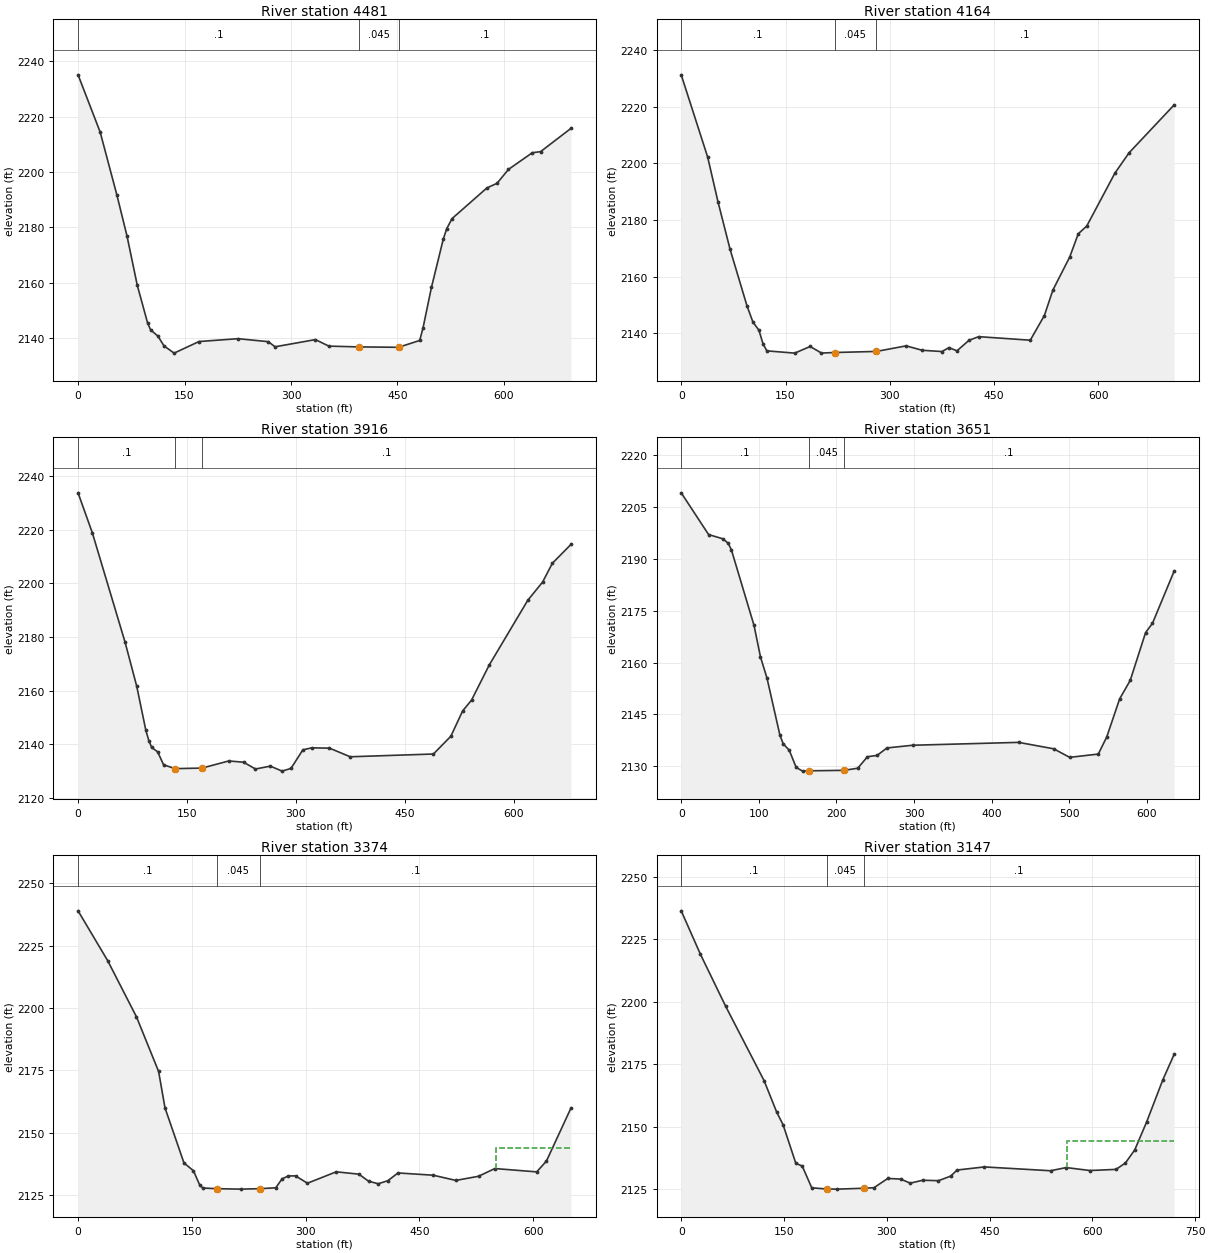
Type RM Length L Ch R = 1 ,4481    ,318.1,316.9,312.3
XS GIS Cut Line= 3
2372385.93297047727614.0869417352372874.93906902727303.501987252
 2372972.4098792727242.376224933
#Sta/Elev= 30
       0 2235.18    31.1 2214.51    54.8 2191.64      69 2176.86    83.4 2159.12
    97.9 2145.54   102.2 2142.99   112.4 2140.77   121.1 2137.21   135.3 2134.59
   170.4 2138.78   225.4 2139.81     268 2138.73   277.5 2136.88   334.4 2139.48
   353.3 2137.12     396 2136.84   451.5  2136.7   481.3 2139.17     486 2143.76
   497.8 2158.32   514.4 2175.69   519.2 2179.48   526.8 2183.21     576 2194.31
   590.2 2195.96   606.3 2200.99   639.9 2207.02   651.6 2207.42   694.4 2215.83
#Mann= 3 ,-1,0
       0      .1       0     396    .045       0   451.5      .1       0
Bank Sta=396,451.5
XS Rating Curve= 0 ,0
Exp/Cntr(USF)=0,0
Exp/Cntr=0.3,0.1

Type RM Length L Ch R = 1 ,4164    ,265.4,248.6,228.5
XS GIS Cut Line= 3
2372689.46102884727794.7016744082373002.80983167727565.285586618
2373055.96721786727249.139026615
#Sta/Elev= 30
       0 2231.31    38.1 2202.19    52.9 2186.42    70.3 2169.62    94.6 2149.65
   103.2 2143.88   111.8 2141.03   117.7 2136.19   123.2 2133.74   163.3 2132.94
   185.4 2135.29   201.7 2132.97   220.5 2133.16   280.6 2133.54   323.6 2135.51
   346.5 2133.95     375  2133.5   385.1 2134.89   396.6 2133.75   413.9 2137.48
   427.8 2138.76     502 2137.51   522.3 2146.24   534.5 2155.21   558.8 2166.95
     571 2175.12   583.2 2177.85   623.7 2196.55     644 2203.72   708.9 2220.67
#Mann= 3 ,-1,0
       0      .1       0   220.5    .045       0   280.6      .1       0
Bank Sta=220.5,280.6
XS Rating Curve= 0 ,0
Exp/Cntr(USF)=0,0
Exp/Cntr=0.3,0.1

Type RM Length L Ch R = 1 ,3916    ,271.4,264.3,251.4
XS GIS Cut Line= 3
2373064.36048937727920.600746976 2373114.7201184727671.600359009
2373195.85507627727254.734540951
#Sta/Elev= 30
       0 2233.83    19.8 2218.77    64.7 2178.08    80.8 2161.59    93.3  2145.2
    97.4 2141.34   101.4 2138.75   109.6 2137.12   117.8 2132.25   134.1 2130.85
   170.8 2131.06   207.5 2133.72   227.9 2133.25   244.3 2130.71   264.7 2131.79
     281 2129.92   293.2 2130.95   309.5 2137.86   321.7 2138.62   346.2  2138.5
   374.7 2135.28   489.3 2136.31   513.3 2142.95   529.5 2152.39   541.8 2156.45
   566.2 2169.57   619.2 2193.71   639.6  2200.5     653 2207.51   678.7 2214.57
#Mann= 3 ,-1,0
       0      .1       0   134.1    .045       0   170.8      .1       0
Bank Sta=134.1,170.8
XS Rating Curve= 0 ,0
Exp/Cntr(USF)=0,0
Exp/Cntr=0.3,0.1

Type RM Length L Ch R = 1 ,3651    ,277.3,276.8,276.8
XS GIS Cut Line= 3
  2373407.557399727935.0315055312373306.59893271727597.279545572
2373243.25872283727322.018379054
#Sta/Elev= 30
       0 2209.05    35.3 2196.99    53.7 2195.76    60.4 2194.51    64.6 2192.61
    93.8 2170.74   102.1 2161.64   110.5 2155.52   127.2 2138.98   131.4 2136.53
   139.2 2134.66   148.1  2129.7   156.4 2128.63   164.9 2128.72   209.9 2128.86
   227.4 2129.47   239.9 2132.79   252.4 2133.18     265 2135.33   298.3 2136.11
   434.7 2136.94   479.9 2135.08   500.4 2132.61   537.3 2133.56   548.2 2138.51
   564.8 2149.51   578.4 2154.83   598.2 2168.65   607.1 2171.35     635 2186.43
#Mann= 3 ,-1,0
       0      .1       0   164.9    .045       0   209.9      .1       0
Bank Sta=164.9,209.9
XS Rating Curve= 0 ,0
Exp/Cntr(USF)=0,0
Exp/Cntr=0.3,0.1

Type RM Length L Ch R = 1 ,3374    ,234.4,227.4,220.8
XS GIS Cut Line= 3
2373682.89867071727890.9769020582373591.11824681727582.594677748
2373477.64561793727274.775482136
#Sta/Elev= 30
       0 2238.93      39 2218.97      77 2196.43   106.2 2174.51   114.6 2159.92
   139.6 2137.85   152.1 2134.71   160.5 2128.89   164.6 2127.78   182.8 2127.52
   214.7 2127.34   239.8 2127.52   260.6 2127.87     269 2131.48   277.3 2132.63
   286.7 2132.65   302.4 2129.71   340.3 2134.28   370.2 2133.34   382.9 2130.53
   395.7 2129.49   408.5 2130.73   421.7 2133.83   468.2 2132.92     498 2130.83
   527.9 2132.49   549.4 2135.59   604.6 2134.26   617.4 2138.58   649.8 2159.87
#Mann= 3 ,-1,0
       0      .1       0   182.8    .045       0   239.8      .1       0
#XS Ineff= 2 , 0
                          550.42         2143.67
Permanent Ineff=
       F       F
Bank Sta=182.8,239.8
XS Rating Curve= 0 ,0
Exp/Cntr(USF)=0,0
Exp/Cntr=0.3,0.1

Type RM Length L Ch R = 1 ,3147    ,246.7,248.5,251
XS GIS Cut Line= 3
2373949.06190003727797.360869678  2373783.857137727516.512772539
2373596.03641839 727170.71250691
#Sta/Elev= 30
       0 2236.35    28.1 2218.95    64.9 2198.17   120.9 2168.48   139.4 2155.84
   148.7 2150.79   167.3 2135.37   176.6 2134.32   190.5  2125.6   212.1 2125.12
   227.6 2125.07   266.7 2125.42   281.3 2125.64   301.5 2129.34   320.4 2129.09
   334.2 2127.45   352.4 2128.62   375.5 2128.45   393.4 2130.28   402.5  2132.7
   442.5 2133.95     539 2132.42   561.8 2133.69   596.5 2132.51   634.6 2132.96
   648.3 2135.53   661.9 2140.74   679.1 2151.81   702.9 2168.78   719.4 2178.96
#Mann= 3 ,-1,0
       0      .1       0   212.1    .045       0   266.7      .1       0
#XS Ineff= 2 , 0
                          563.48         2144.27
Permanent Ineff=
       F       F
Bank Sta=212.1,266.7
XS Rating Curve= 0 ,0
Exp/Cntr(USF)=0,0
Exp/Cntr=0.3,0.1