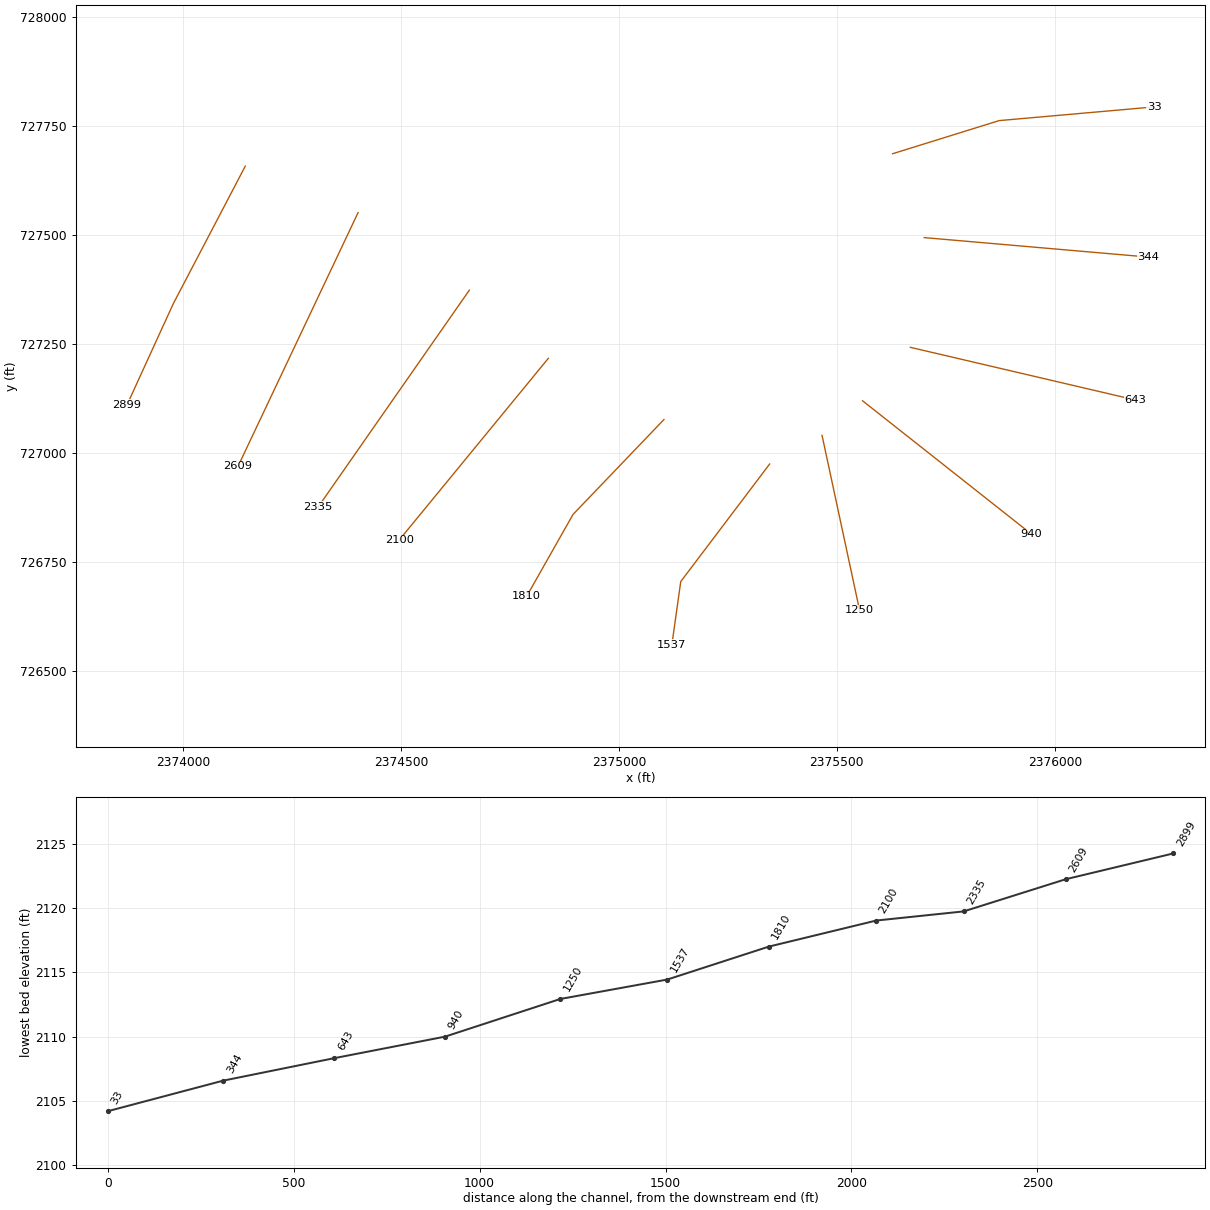
HEC-RAS study GLADYFK.prj: GLADYFK

--- GLADYFK.g01 (geometry) --- (continued)

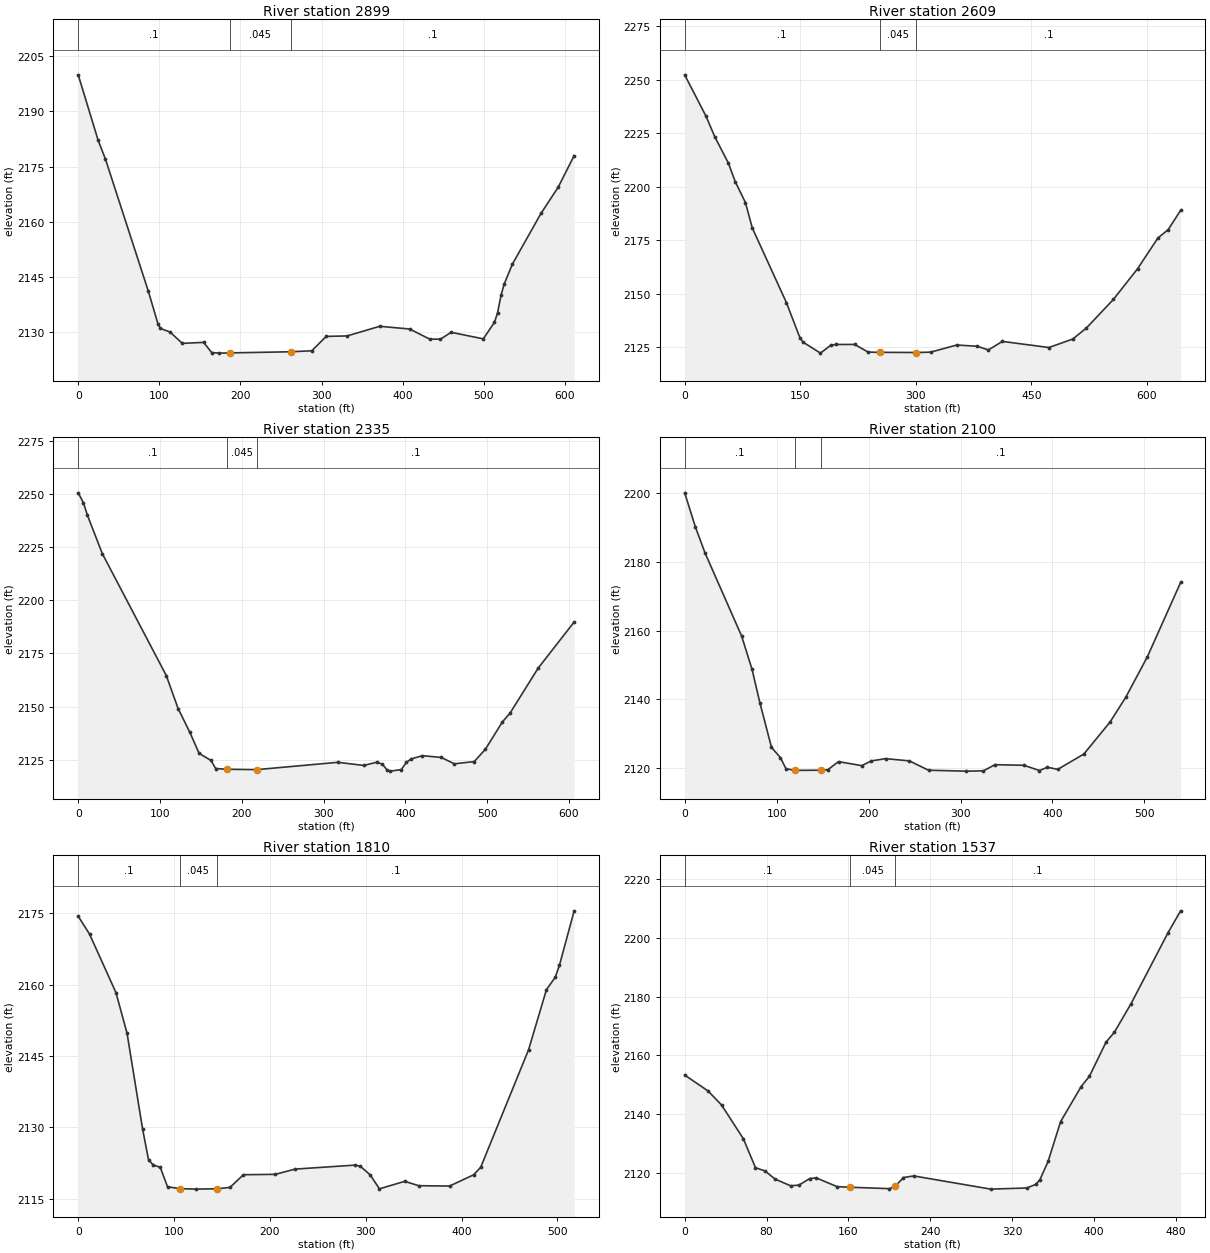
Type RM Length L Ch R = 1 ,2899    ,291.8,289.9,291
XS GIS Cut Line= 3
2374143.06675373 727658.91936648 2373977.8619907727343.194708257
2373871.83587361727111.273109368
#Sta/Elev= 30
       0 2199.94    24.5 2182.18    33.6 2176.99    86.4 2141.11    98.3 2132.23
   101.2 2130.98   113.1 2129.99   128.4 2126.91   154.6 2127.17   164.5 2124.41
   173.5 2124.25   186.7 2124.31   262.4 2124.62   287.9 2124.89   305.7  2128.8
   331.5 2128.93   371.7 2131.55   408.5 2130.81   433.3 2128.06   446.5 2128.05
   459.7 2129.91   499.3 2128.13   513.1 2132.64   516.9 2135.22   521.3 2140.13
   525.1 2143.06   535.2 2148.47   570.4 2162.24   591.7 2169.41   611.3 2177.97
#Mann= 3 ,-1,0
       0      .1       0   186.7    .045       0   262.4      .1       0
Bank Sta=186.7,262.4
XS Rating Curve= 0 ,0
Exp/Cntr(USF)=0,0
Exp/Cntr=0.3,0.1

Type RM Length L Ch R = 1 ,2609    ,279.9,274.1,275.2
XS GIS Cut Line= 2
2374401.88754913727552.4540747532374126.54627742726970.566187214
#Sta/Elev= 30
       0 2252.25    27.8 2232.84      39 2223.37    56.7 2211.01    65.6 2202.36
    78.9 2192.55    87.7 2180.76     132 2145.87   149.7  2129.3   153.9 2127.33
   176.2 2122.24   189.5 2125.88     196 2126.28   220.5  2126.3   238.2 2122.72
   253.1 2122.61   300.1 2122.53   319.1 2122.69   353.2 2126.03   379.8 2125.44
   394.2 2123.73   412.3 2127.72   472.7 2124.86   503.7 2128.82   521.4 2133.97
   556.5 2147.36   587.8 2161.65   614.3 2176.06   627.6 2179.94   643.7 2188.94
#Mann= 3 ,-1,0
       0      .1       0   253.1    .045       0   300.1      .1       0
Bank Sta=253.1,300.1
XS Rating Curve= 0 ,0
Exp/Cntr(USF)=0,0
Exp/Cntr=0.3,0.1

Type RM Length L Ch R = 1 ,2335    ,232.2,235,231.4
XS GIS Cut Line= 2
2374657.03712758727374.4000523832374310.10712523726876.950154834
#Sta/Elev= 30
       0 2250.47     6.4 2245.77    11.2    2240    29.5 2221.89   107.8 2164.57
   122.2  2149.1   136.5 2137.99   147.8 2128.12   162.4 2124.75   168.1 2120.96
   182.5 2120.62   218.3 2120.44   317.5 2123.88   349.1 2122.41   365.1 2123.91
   372.1    2123   377.9 2120.15   381.9 2119.74   395.1 2120.48   401.4 2123.85
   407.1 2125.47   420.9    2127   443.9 2126.16   459.9 2123.19   484.3 2124.22
     498 2130.05   518.6 2142.77   528.2 2147.04   562.3 2168.03   606.5 2189.79
#Mann= 3 ,-1,0
       0      .1       0   182.5    .045       0   218.3      .1       0
Bank Sta=182.5,218.3
XS Rating Curve= 0 ,0
Exp/Cntr(USF)=0,0
Exp/Cntr=0.3,0.1

Type RM Length L Ch R = 1 ,2100    ,295.6,289.2,290.2
XS GIS Cut Line= 2
2374838.28965686727218.1876616082374496.09597762726801.209933263
#Sta/Elev= 30
       0 2200.14    11.7 2190.16    22.2 2182.58    61.9 2158.43    73.3 2148.65
    81.8 2138.94    94.4 2125.98   104.2 2122.93   110.2 2119.72   120.3 2119.25
   148.4  2119.3   155.7 2119.44   167.3  2121.8   192.6 2120.63   203.1 2122.01
   218.6 2122.67   244.5 2122.01   265.2 2119.29     306 2119.03   324.9 2119.11
   337.5 2120.91     369 2120.73   385.9  2119.2   394.4 2120.16   405.8 2119.55
   434.2 2124.02   462.6 2133.32   479.7 2140.54   503.2 2152.33   539.4 2174.02
#Mann= 3 ,-1,0
       0      .1       0   120.3    .045       0   148.4      .1       0
Bank Sta=120.3,148.4
XS Rating Curve= 0 ,0
Exp/Cntr(USF)=0,0
Exp/Cntr=0.3,0.1

Type RM Length L Ch R = 1 ,1810    ,267.6,272.9,272
XS GIS Cut Line= 3
2375103.43310368727077.6842966222374894.94423951726860.130699224
2374788.43362412726672.037484808
#Sta/Elev= 30
       0 2174.41    11.8 2170.66    39.4 2158.34      51 2149.75    67.2 2129.62
    73.4 2123.16    78.3 2122.07    85.6  2121.6    93.2 2117.49     106 2117.11
   122.6    2117   144.7 2117.08   158.3 2117.35   172.4 2120.03   205.7 2120.11
   226.2 2121.21   288.4 2122.05   294.3 2121.83   304.7    2120   314.3 2117.06
   340.7 2118.64   355.3 2117.72   387.5 2117.65   412.5    2120     420  2121.6
   469.9  2146.3   488.6 2158.97   497.8 2161.58   502.2 2164.13   517.5 2175.55
#Mann= 3 ,-1,0
       0      .1       0     106    .045       0   144.7      .1       0
Bank Sta=106,144.7
XS Rating Curve= 0 ,0
Exp/Cntr(USF)=0,0
Exp/Cntr=0.3,0.1

Type RM Length L Ch R = 1 ,1537    ,277.5,287.5,314.1
XS GIS Cut Line= 3
2375345.91471745726975.7060478422375141.95821989726706.030234401
2375121.56257013726560.994502803
#Sta/Elev= 30
       0 2153.32    22.8 2147.91      36 2143.13    57.3 2131.64    69.2 2121.74
    78.4 2120.65    88.4 2117.85   103.5 2115.58   111.6 2115.81   122.2 2118.04
   128.5 2118.28   148.8  2115.3     162 2115.08   200.1  2114.6   205.8 2115.46
   213.8 2118.39   223.8 2118.94   299.1 2114.44   334.2 2114.83     343 2116.04
   347.1 2117.64   355.1 2123.88   367.3 2137.43   387.4 2149.39   395.5 2152.91
   411.7 2164.52   419.8 2167.87   436.1  2177.6   472.3 2201.83   484.6 2209.29
#Mann= 3 ,-1,0
       0      .1       0     162    .045       0   205.8      .1       0
Bank Sta=162,205.8
XS Rating Curve= 0 ,0
Exp/Cntr(USF)=0,0
Exp/Cntr=0.3,0.1

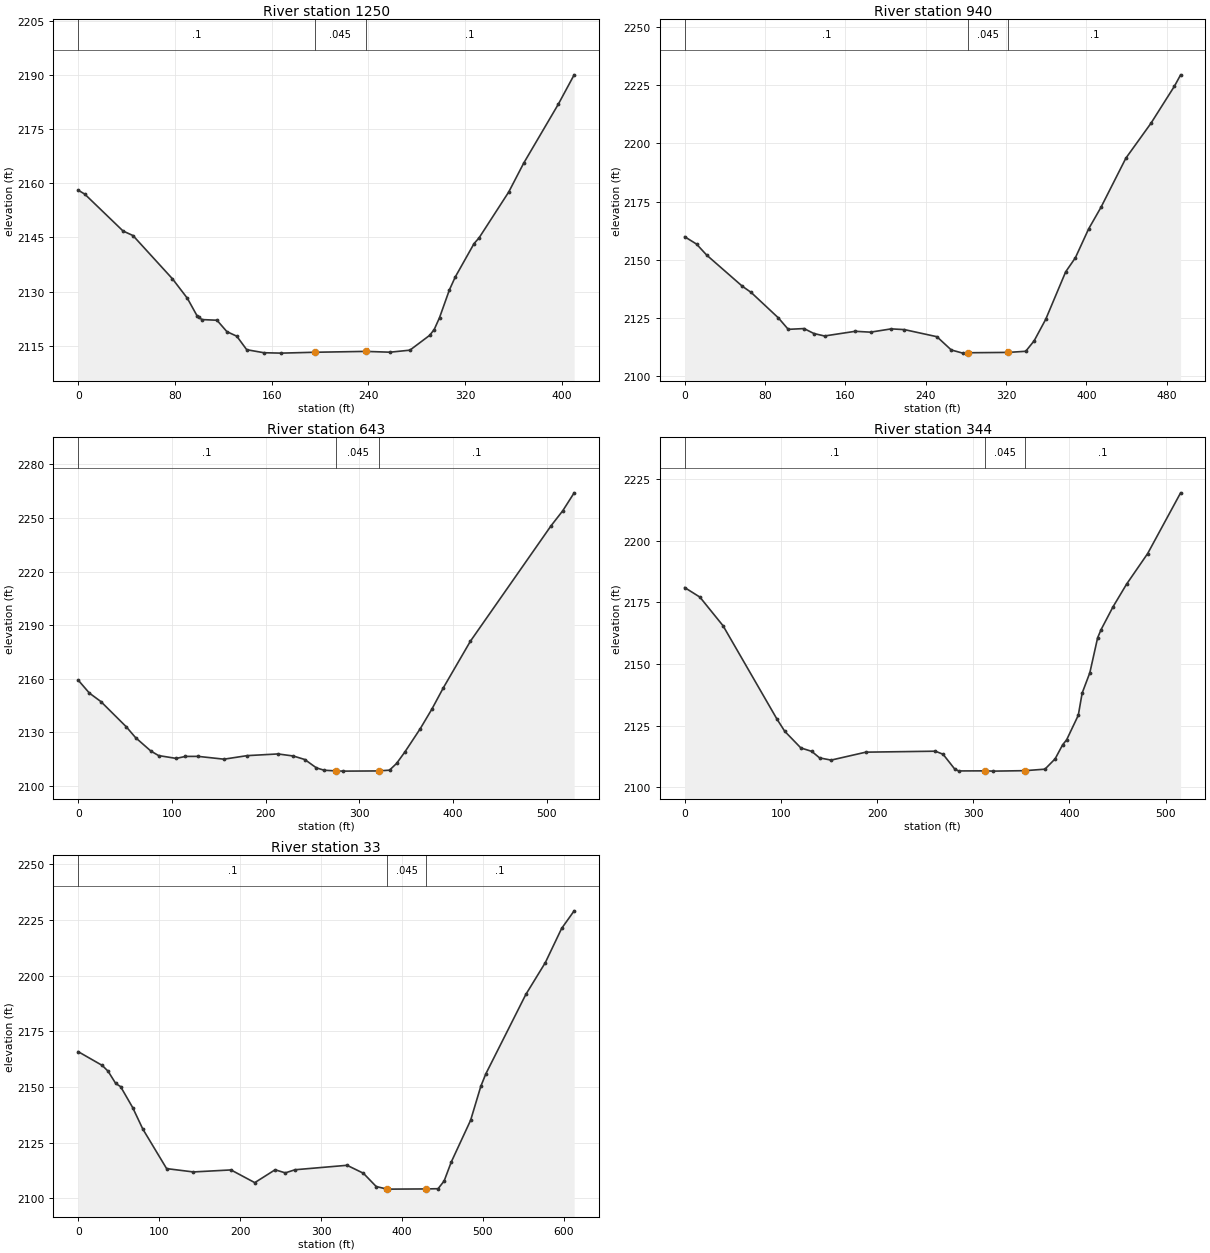
Type RM Length L Ch R = 1 ,1250    ,294.8,310,322.6
XS GIS Cut Line= 2
2375466.02243268727041.4253637222375552.13739832726640.310918521
#Sta/Elev= 30
       0 2158.11     5.4 2157.02    37.1 2146.79    45.3 2145.53      78 2133.52
    90.3 2128.14    98.4 2123.23    99.7 2122.82   102.5 2122.23   114.8 2122.05
     123 2118.89   131.2 2117.62   139.4 2113.88   153.6 2113.04     168 2112.93
   195.5 2113.17   237.8 2113.41     258 2113.19   274.4 2113.75   290.7 2117.85
   294.5 2119.46   298.9 2122.75   307.1 2130.47   311.9 2134.02   327.5 2143.31
   331.6 2144.87   356.2 2157.62   368.5 2165.57   397.1 2181.89   410.3 2190.09
#Mann= 3 ,-1,0
       0      .1       0   195.5    .045       0   237.8      .1       0
Bank Sta=195.5,237.8
XS Rating Curve= 0 ,0
Exp/Cntr(USF)=0,0
Exp/Cntr=0.3,0.1

Type RM Length L Ch R = 1 ,940     ,288.6,297.3,308.1
XS GIS Cut Line= 2
2375558.93594824 727120.74177944 2375946.4532936  726814.8070331
#Sta/Elev= 30
       0 2159.91    11.8 2156.76      22    2152    57.5 2138.64    66.1 2136.05
    93.3  2125.1   103.1  2120.2   118.8 2120.53   128.7  2118.4   139.2 2117.35
   169.8 2119.36     185 2118.99   205.6  2120.4   218.8 2120.08   251.1 2117.04
   265.4 2111.35   276.8    2110   281.9 2110.16   322.1 2110.31   339.5 2110.79
   347.9 2115.29   359.4  2124.5   379.3 2144.88   388.9 2150.87   402.1 2163.24
   414.4 2172.51   439.2  2193.6   464.1 2208.52   487.6  2224.5   493.7 2229.33
#Mann= 3 ,-1,0
       0      .1       0   281.9    .045       0   322.1      .1       0
Bank Sta=281.9,322.1
XS Rating Curve= 0 ,0
Exp/Cntr(USF)=0,0
Exp/Cntr=0.3,0.1

Type RM Length L Ch R = 1 ,643     ,297,299,302.9
XS GIS Cut Line= 2
2375668.61993835727243.3163020342376184.05879898727122.716825027
#Sta/Elev= 30
       0 2159.27    11.9 2152.02    24.2 2147.27    51.3 2133.15    61.2  2127.1
    77.6 2119.55    85.8 2117.04   104.6 2115.45   114.5 2116.56   127.9 2116.59
   155.6 2115.02   180.3    2117   213.2 2117.95   229.6  2116.8   241.9 2114.82
   254.2 2110.17   262.5 2108.83   275.4 2108.45     283 2108.33     321 2108.44
   332.3 2108.87   339.8 2112.61   348.7 2119.05   365.2 2132.16   377.5 2143.02
   389.8 2155.01   418.6 2181.02   504.8 2245.71   517.2 2254.05   529.4 2264.11
#Mann= 3 ,-1,0
       0      .1       0   275.4    .045       0     321      .1       0
Bank Sta=275.4,321
XS Rating Curve= 0 ,0
Exp/Cntr(USF)=0,0
Exp/Cntr=0.3,0.1

Type RM Length L Ch R = 1 ,344     ,307.4,310.8,314.9
XS GIS Cut Line= 2
 2375700.4326196727494.998620024 2376214.2194326727450.393334007
#Sta/Elev= 30
       0 2180.99    15.8 2177.13    39.9 2165.51    96.1 2127.58   104.1 2122.71
   120.8 2115.98   132.2 2114.58   140.3 2111.94   152.3 2111.05   188.4 2114.27
   260.7 2114.66   268.7 2113.41   280.8 2107.43   284.8 2106.66   311.8 2106.69
   320.9 2106.58   353.9 2106.77   374.6 2107.37   385.2 2111.56     393 2117.24
   397.2 2119.29   409.3 2129.23   413.3  2138.2   421.3 2146.46   429.4 2160.63
     433 2163.95   445.4 2173.18   459.5 2182.37   481.4 2194.76   515.7 2219.39
#Mann= 3 ,-1,0
       0      .1       0   311.8    .045       0   353.9      .1       0
Bank Sta=311.8,353.9
XS Rating Curve= 0 ,0
Exp/Cntr(USF)=0,0
Exp/Cntr=0.3,0.1

Type RM Length L Ch R = 1 ,33      ,,,
XS GIS Cut Line= 3
2375627.93288327727687.3975827222375872.43593254727763.391773713
2376227.62617304727794.780678688
#Sta/Elev= 30
       0 2165.85    29.6  2159.7    36.8 2157.13    46.3 2151.61    52.4 2150.15
    67.3 2140.76    79.8 2131.14   109.2  2113.4   142.2 2111.91   188.7 2112.81
   218.1 2107.11   243.2 2112.88   255.8 2111.49   267.8 2112.89   332.1 2114.89
   352.2 2111.34   368.1 2105.36   381.5 2104.22   384.3  2104.2     430 2104.29
   444.5 2104.39     452 2107.85   460.8 2116.36   484.7 2135.08   497.3 2150.31
   503.5 2155.91   552.9 2191.51     577  2205.8   597.1 2221.11   612.6 2229.02
#Mann= 3 ,-1,0
       0      .1       0   381.5    .045       0     430      .1       0
Bank Sta=381.5,430
XS Rating Curve= 0 ,0
Exp/Cntr(USF)=0,0
Exp/Cntr=0.3,0.1
LCMann Table=0

Chan Stop Cuts=-1
Use User Specified Reach Order=0
Composite Channel Slope=5